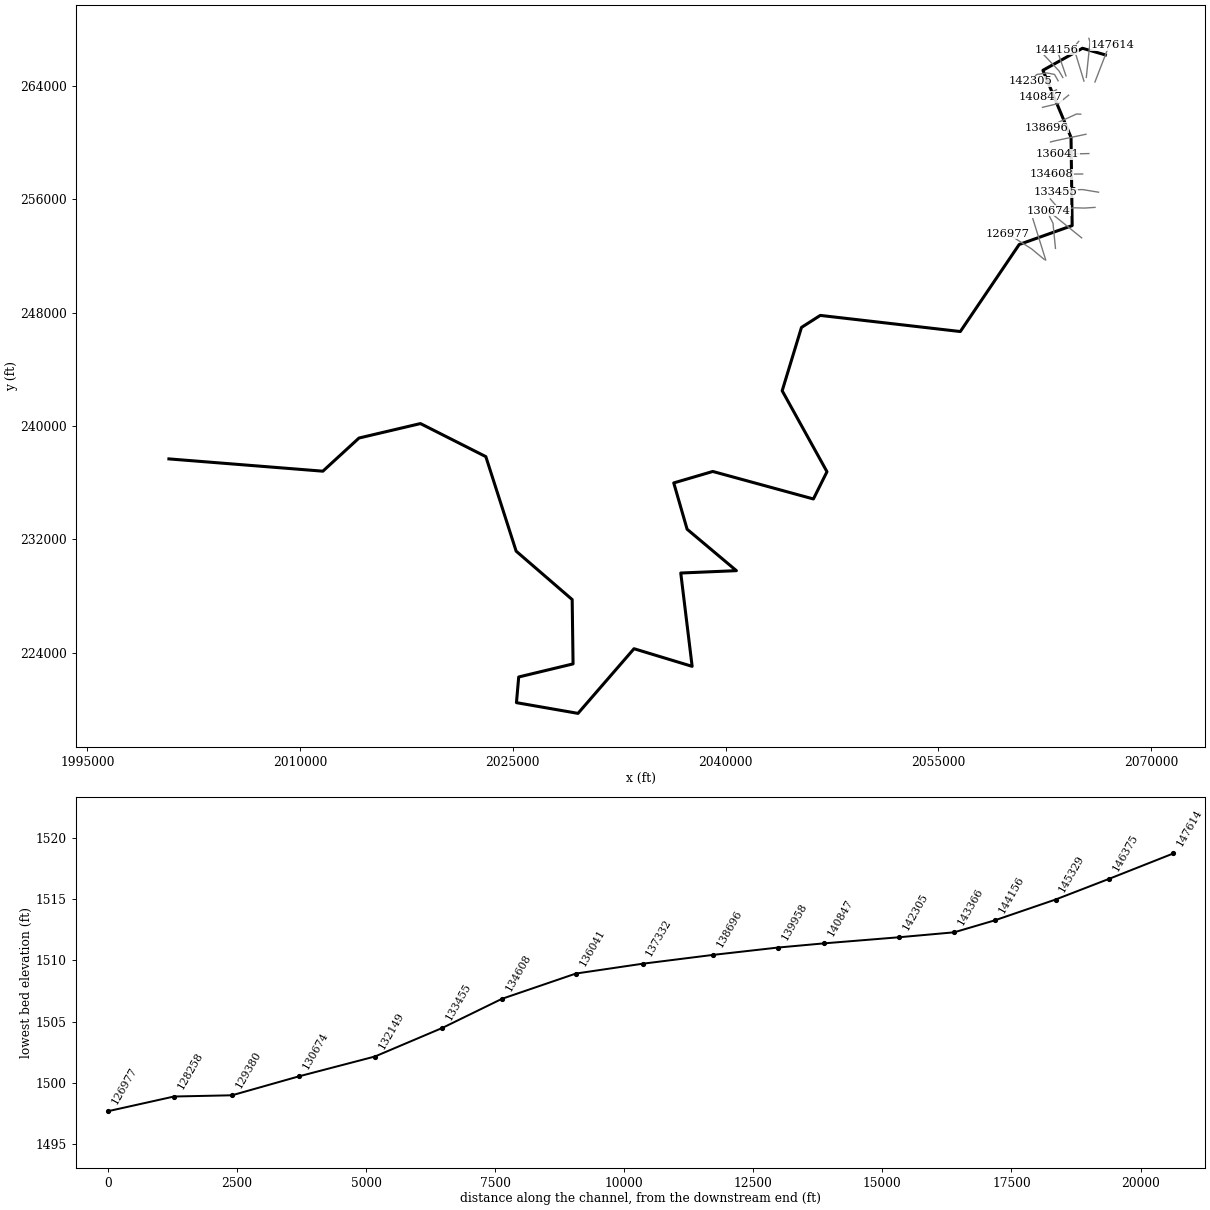
--- GREENBRRV.prj (project) ---

Proj Title=GREENBRRV
Current Plan=p01
Default Exp/Contr=0,0
English Units
Geom File=g01
Flow File=f01
Plan File=p01
BEGIN DESCRIPTION:
Stream Name: Greenbrier River
Flood Zone: Detailed
Summers County, West Virginia
HEC-RAS Version: 5.0.7
Hydrology Method: Gage-weighting
Model Notes:
END DESCRIPTION:
DSS Export Rating Curves= 0
DSS Export Rating Curve Sorted= 0
DSS Export Volume Flow Curves= 0
DXF OffsetX= 0
DXF OffsetY= 0
DXF ScaleX= 0
DXF ScaleY= 0

--- GREENBRRV.p01 (plan) ---

Plan Title=Floodplain
Program Version=5.07
Short Identifier=Floodplain
Geom File=g01
Flow File=f01
Subcritical Flow
K Sum by GR= 0
Std Step Tol= 0.01
Critical Tol= 0.01
Num of Std Step Trials= 20
Max Error Tol= 0.3
Flow Tol Ratio= 0.001
Split Flow NTrial= 30
Split Flow Tol= 0.02
Split Flow Ratio= 0.02
Log Output Level= 0
Friction Slope Method= 1
Unsteady Friction Slope Method= 2
Unsteady Bridges Friction Slope Method= 1
Parabolic Critical Depth
Global Vel Dist= 0 , 0 , 0
Global Log Level= 0
CheckData=True
Encroach Param=-1 ,10,10, 2
Encroach River=GREENBRRV
Encroach Reach=Main
Encroach Node=147614
       1    1900    2200
Encroach Node=146375
       1    1872    2146
Encroach Node=145329
       1    2010    2462
Encroach Node=144156
       1    1320    1752
Encroach Node=143366
       1    1200    1714
Encroach Node=142305
       1     950    1628
Encroach Node=140847
       1     350  787.03
Encroach Node=139958
       1     800 1356.21
Encroach Node=138696
       1     800    2178
Encroach Node=137332
       1     750 1979.95
Encroach Node=136041
       1     877 1857.76
Encroach Node=134608
       1     450  1402.4
Encroach Node=133455
       1    1888 2444.98
Encroach Node=132149
       1 1452.59  1900.8
Encroach Node=130674
       1  892.21    1310
Encroach Node=129380
       1     815    1150
Encroach Node=128258
       1    1475    2100
Encroach Node=126977
       1    1640    2172
Encroach Node=125941
       1    1350  1841.5
Encroach Node=124755
       1    1290  1853.1
Encroach Node=123435
       1    1610  2332.1
Encroach Node=122335
       1    1600    2216
Encroach Node=120963
       1    1500    2040
Encroach Node=119692
       1    1030    1890
Encroach Node=118814
       1  317.73    1250
Encroach Node=117807
       1     258     850
Encroach Node=116407
       1     525    1100
Encroach Node=115039
       1     370     940
Encroach Node=113850
       1     508    1550
Encroach Node=112628
       1     449    1550
Encroach Node=112231
       1   502.4    1700
Encroach Node=111725
       1  547.51    1700
Encroach Node=110748
       1     850    2000
Encroach Node=110587
       1     850    1850
Encroach Node=109351
       1    1050    1980
Encroach Node=108261
       1     390    1100
Encroach Node=107406
       1     400    1140
Encroach Node=106382
       1     490    1210
Encroach Node=105529
       1     450 1069.68
Encroach Node=104771
       1     370  997.33
Encroach Node=103371
       1     420 1113.71
Encroach Node=102646
       1     530 1238.83
Encroach Node=101674
       1     705    1295
Encroach Node=100771
       1  710.87 1205.24
Encroach Node=100019
       1   633.3    1136
Encroach Node=98917
       1     954  1466.1
Encroach Node=98167
       1    1250 1727.93
Encroach Node=97740
       1    1070 1627.07
Encroach Node=97308
       1    1270    1980
Encroach Node=97161
       1    1335    1975
Encroach Node=97035
       1    1434 2070.12
Encroach Node=96829
       1    1616    2301
Encroach Node=96654
       1 1613.33    2301
Encroach Node=95769
       1     612 1072.37
Encroach Node=95198
       1     620    1066
Encroach Node=94608
       1     895  1387.2
Encroach Node=93356
       1     465  970.43
Encroach Node=91891
       1  632.05     985
Encroach Node=90459
       1     440  937.74
Encroach Node=89307
       1     610    1376
Encroach Node=88523
       1  1040.3 1646.36
Encroach Node=87828
       1     935    1460
Encroach Node=87668
       1     935  1472.5
Encroach Node=86785
       1     457 1035.98
Encroach Node=85514
       1     550  1398.8
Encroach Node=84919
       1     816    1494
Encroach Node=84439
       1   835.3    1329
Encroach Node=83640
       1    1213    1743
Encroach Node=82438
       1    1065  1471.4
Encroach Node=81626
       1   657.4    1063
Encroach Node=80707
       1     650    1112
Encroach Node=79814
       1   529.2  1016.3
Encroach Node=79090
       1   482.3    1000
Encroach Node=78243
       1     414    1115
Encroach Node=77444
       1   606.2    1310
Encroach Node=76523
       1     330   977.1
Encroach Node=75868
       1     430   829.5
Encroach Node=75025
       1   424.7     720
Encroach Node=74161
       1   199.5     501
Encroach Node=73507
       1     320     688
Encroach Node=72797
       1     690  1192.4
Encroach Node=72129
       1    1250    1729
Encroach Node=71117
       1    2100    2527
Encroach Node=70278
       1    2075    2410
Encroach Node=69087
       1    2005    2424
Encroach Node=67918
       1 1737.87    2152
Encroach Node=66872
       1 1054.69    1498
Encroach Node=65897
       1   794.8    1335
Encroach Node=65083
       1     635    1210
Encroach Node=64464
       1     523    1000
Encroach Node=64199
       1   937.4    1377
Encroach Node=63421
       1     750    1120
Encroach Node=63140
       1     312     700
Encroach Node=62786
       1     830    1320
Encroach Node=62506
       1   709.1    1270
Encroach Node=62045
       1  1005.1    1330
Encroach Node=61324
       1     850    1325
Encroach Node=60276
       1 1045.35    1640
Encroach Node=59308
       1  1312.3    1958
Encroach Node=58246
       1    1600    2086
Encroach Node=57448
       1    1430    2020
Encroach Node=56529
       1     720    1452
Encroach Node=55302
       1     940    1613
Encroach Node=54612
       1     850    1532
Encroach Node=54050
       1     590    1350
Encroach Node=52945
       1     385    1030
Encroach Node=51625
       1     535     995
Encroach Node=51395
       1     502     960
Encroach Node=50086
       1   434.3     940
Encroach Node=49327
       1     310     895
Encroach Node=47944
       1     750    1400
Encroach Node=47512
       1     530    1073
Encroach Node=46599
       1   534.6  987.04
Encroach Node=45725
       1     231     735
Encroach Node=44910
       1     405     962
Encroach Node=44086
       1     480     990
Encroach Node=43140
       1     745    1220
Encroach Node=42125
       1  872.23    1261
Encroach Node=41364
       1     723    1140
Encroach Node=40490
       1     566    1020
Encroach Node=39507
       1     671    1110
Encroach Node=38515
       1     645    1240
Encroach Node=37595
       1     520    1390
Encroach Node=36960
       1     445    1350
Encroach Node=36102
       1     509    1313
Encroach Node=34924
       1  308.47     855
Encroach Node=33767
       1     609     980
Encroach Node=32872
       1     603    1042
Encroach Node=31920
       1     410     925
Encroach Node=31025
       1     360     785
Encroach Node=30473
       1     506     913
Encroach Node=29952
       1     375     764
Encroach Node=29800
       1     410     760
Encroach Node=29260
       1     555  951.28
Encroach Node=28570
       1  592.19 1173.41
Encroach Node=27973
       1  586.97    1150
Encroach Node=27123
       1   274.3     850
Encroach Node=26086
       1     200     840
Encroach Node=25092
       1     185     635
Encroach Node=24792
       1  259.45  774.97
Encroach Node=23757
       1  449.23  778.51
Encroach Node=22832
       1   382.1  721.75
Encroach Node=22176
       1     429     760
Encroach Node=21462
       1   405.2     715
Encroach Node=20618
       1   362.2  690.27
Encroach Node=19896
       1   402.4   745.4
Encroach Node=19172
       1     424     777
Encroach Node=18262
       1  482.82     823
Encroach Node=17385
       1     400     860
Encroach Node=16981
       1     320     804
Encroach Node=16793
       1   301.3     800
Encroach Node=15774
       1  530.15     930
Encroach Node=14909
       1  569.63 1003.08
Encroach Node=14150
       1     465   820.2
Encroach Node=13407
       1     404  827.96
Encroach Node=12888
       1     353     746
Encroach Node=12383
       1     429   921.6
Encroach Node=11787
       1     441   926.8
Encroach Node=11047
       1     320  822.83
Encroach Node=10254
       1     366  774.06
Encroach Node=9493
       1     409     787
Encroach Node=8902
       1     381     700
Encroach Node=8195
       1  644.11  1073.1
Encroach Node=8115
       1     645  1082.5
Encroach Node=7562
       1     585   902.5
Encroach Node=6740
       1     643   942.5
Encroach Node=5895
       1   653.5   944.2
Encroach Node=5119
       1   542.9   871.7
Encroach Node=4405
       1   496.7     843
Encroach Node=3604
       1   498.2   872.5
Encroach Node=2848
       1   566.6   957.4
Encroach Node=1994
       1     283     688
Encroach Node=1538
       1   125.7     643
Encroach Node=1230
       1  1673.8    2388
Encroach Node=1135
       1  1582.8    2287
Encroach Node=126
       1     546  2091.2
Mapping Interval=1HOUR
Computation Time Step Use Courant=        0
Computation Time Step Use Time Series=    0
Computation Time Step Count To Double=0
Computation Time Step Max Doubling=0
Computation Time Step Max Halving=0
Computation Time Step Residence Courant=0
Run HTab= 0
Run UNet= 0
Run Sediment= 0
Run PostProcess= 0
Run WQNet= 0
Run RASMapper= 0
UNET Theta= 0
UNET Theta Warmup= 0
UNET ZTol= 0
UNET ZSATol= 0
UNET MxIter= 0
UNET Max Iter WO Improvement= 0
UNET MaxInSteps= 0
UNET DtIC= 0
UNET DtMin= 0
UNET MaxCRTS= 0
UNET WFStab= 0
UNET SFStab= 0
UNET WFX= 1
UNET SFX= 1
UNET 1D Methodology=Finite Difference
UNET DSS MLevel= 1
UNET Pardiso=0
UNET DZMax Abort= 0
UNET Use Existing IB Tables= 0
UNET Froude Reduction=False
UNET Froude Limit= 0
UNET Froude Power= 0
UNET D1 Cores= 0
UNET D2 Coriolis=0
UNET D2 Cores= 0
UNET D2 Theta= 1
UNET D2 Theta Warmup= 1
UNET D2 Z Tol= 0.01
UNET D2 Volume Tol= 0.01
UNET D2 Max Iterations= 20
UNET D2 Equation= 0
UNET D2 RampUpFraction=0.1
UNET D2 TimeSlices= 1
UNET D2 BCVolumeCheck=0
UNET D1D2 MaxIter= 0
UNET D1D2 ZTol=0.01
UNET D1D2 QTol=0.1
UNET D1D2 MinQTol=1
Write IC File= 0
Write IC File at Fixed DateTime=0
Write IC File at Sim End=0
Echo Input=False
Echo Parameters=False
Echo Output=False
Write Detailed= 0
HDF Write Warmup=0
HDF Write Time Slices=0
HDF Flush=0
HDF Face Node Velocities=0
HDF Compression= 1
HDF Chunk Size= 1
HDF Spatial Parts= 1
HDF Use Max Rows=0
HDF Fixed Rows= 1
Calibration Method= 0
Calibration Iterations= 20
Calibration Max Change=0.05
Calibration Tolerance=0.2
Calibration Maximum=1.5
Calibration Minimum=0.5
Calibration Optimization Method= 1
WQ AD Non Conservative
WQ ULTIMATE=-1
WQ Max Comp Step=1HOUR
WQ Output Interval=15MIN
WQ Output Selected Increments= 0
WQ Output face flow=0
WQ Output face velocity=0
WQ Output face area=0
WQ Output face dispersion=0
WQ Output cell volume=0
WQ Output cell surface area=0
WQ Output cell continuity=0
WQ Output cumulative cell continuity=0
WQ Output face conc=0
WQ Output face dconc_dx=0
WQ Output face courant=0
WQ Output face peclet=0
WQ Output face adv mass=0
WQ Output face disp mass=0
WQ Output cell mass=0
WQ Output cell source sink temp=0
WQ Output nsm pathways=0
WQ Output nsm derived pathways=0
WQ Output MaxMinRange=-1
WQ Daily Max Min Mean=-1
WQ Daily Range=0
WQ Daily Time=0
WQ Create Restart=0
WQ Fixed Restart=0
WQ System Summary=0
WQ Write To DSS=0
WQ Use Fixed Temperature=0
Sorting and Armoring Iterations= 10
XS Update Threshold= 0.02
Bed Roughness Predictor= 0
Hydraulics Update Threshold= 0.02
Energy Slope Method= 1
Volume Change Method= 1
Sediment Retention Method= 0
XS Weighting Method= 0
Number of US Weighted Cross Sections= 1
Number of DS Weighted Cross Sections= 1
Upstream XS Weight=0
Main XS Weight=1
Downstream XS Weight=0
Number of DS XS's Weighted with US Boundary= 1
Upstream Boundary Weight= 1
Weight of XSs Associated with US Boundary= 0
Number of US XS's Weighted with DS Boundary= 1
Downstream Boundary Weight= 0.5
Weight of XSs Associated with DS Boundary= 0.5
Percentile Method= 0
Sediment Output Level= 3
Mass or Volume Output= 0
Output Increment Type= 1
Profile and TS Output Increment= 1
XS Output Flag= 0
XS Output Increment= 10
Write Gradation File= 0
Read Gradation Hotstart= 0
Write HDF5 File= 1
Write Binary Output= 1
Write DSS Sediment File= 0
SV Curve= 0
Specific Gage Flag= 0

--- GREENBRRV.f01 (steady flow) ---

Flow Title=Flows
Program Version=5.07
Number of Profiles= 7
Profile Names=01pct,FW,10pct,04pct,02pct,0_2pct,01plus
River Rch & RM=GREENBRRV,Main            ,147614
   85078   85078   57252   68299   76615  105420   93929
River Rch & RM=GREENBRRV,Main            ,130674
   89197   89197   59523   71138   80047  111661  102712
Boundary for River Rch & Prof#=GREENBRRV,Main            , 1
Up Type= 0
Dn Type= 3
Dn Slope=0.0014
Boundary for River Rch & Prof#=GREENBRRV,Main            , 2
Up Type= 0
Dn Type= 3
Dn Slope=0.0014
Boundary for River Rch & Prof#=GREENBRRV,Main            , 3
Up Type= 0
Dn Type= 3
Dn Slope=0.0014
Boundary for River Rch & Prof#=GREENBRRV,Main            , 4
Up Type= 0
Dn Type= 3
Dn Slope=0.0014
Boundary for River Rch & Prof#=GREENBRRV,Main            , 5
Up Type= 0
Dn Type= 3
Dn Slope=0.0014
Boundary for River Rch & Prof#=GREENBRRV,Main            , 6
Up Type= 0
Dn Type= 3
Dn Slope=0.0014
Boundary for River Rch & Prof#=GREENBRRV,Main            , 7
Up Type= 0
Dn Type= 3
Dn Slope=0.0014
DSS Import GetInterval= 0
DSS Import GetPeak= 0
DSS Import FillOption= 0

--- GREENBRRV.g01 (geometry) ---

Geom Title=Geometry
Program Version=5.07

River Reach=GREENBRRV       ,Main
Reach XY= 30
2066788.49058683266204.2297717942065171.48111689266674.004116565
2062383.14286156265117.8687773942064365.43450063260381.670900732
2064445.38250346254155.8027750552060709.27153739252822.469483733
2056556.49375372246676.6359748992046681.49349064247815.524773225
2045355.10473922246968.302714393 2043993.9936163242496.080359638
2047153.71597138236780.8027482332046195.38258623234857.191437975
 2039099.3805592236799.1889619592036346.71363531235989.714763477
2037288.55394322232721.4854075612040765.11621581 229796.13823989
2036841.50529663229629.4715784792037643.58866622223040.929965556
2033544.63032871224285.7217673062029593.24124989219721.485488981
2025252.96351314 220478.429841222025412.68563464222290.930153221
2029246.01917531223214.5411668872029183.51897222227756.207936555
2025232.13022147231172.8743315642023093.24145463237846.485656232
2018482.13027005240179.8189160672014148.79674514239158.985655889
2011600.18570064236818.7078561482000742.78549947237686.057499394

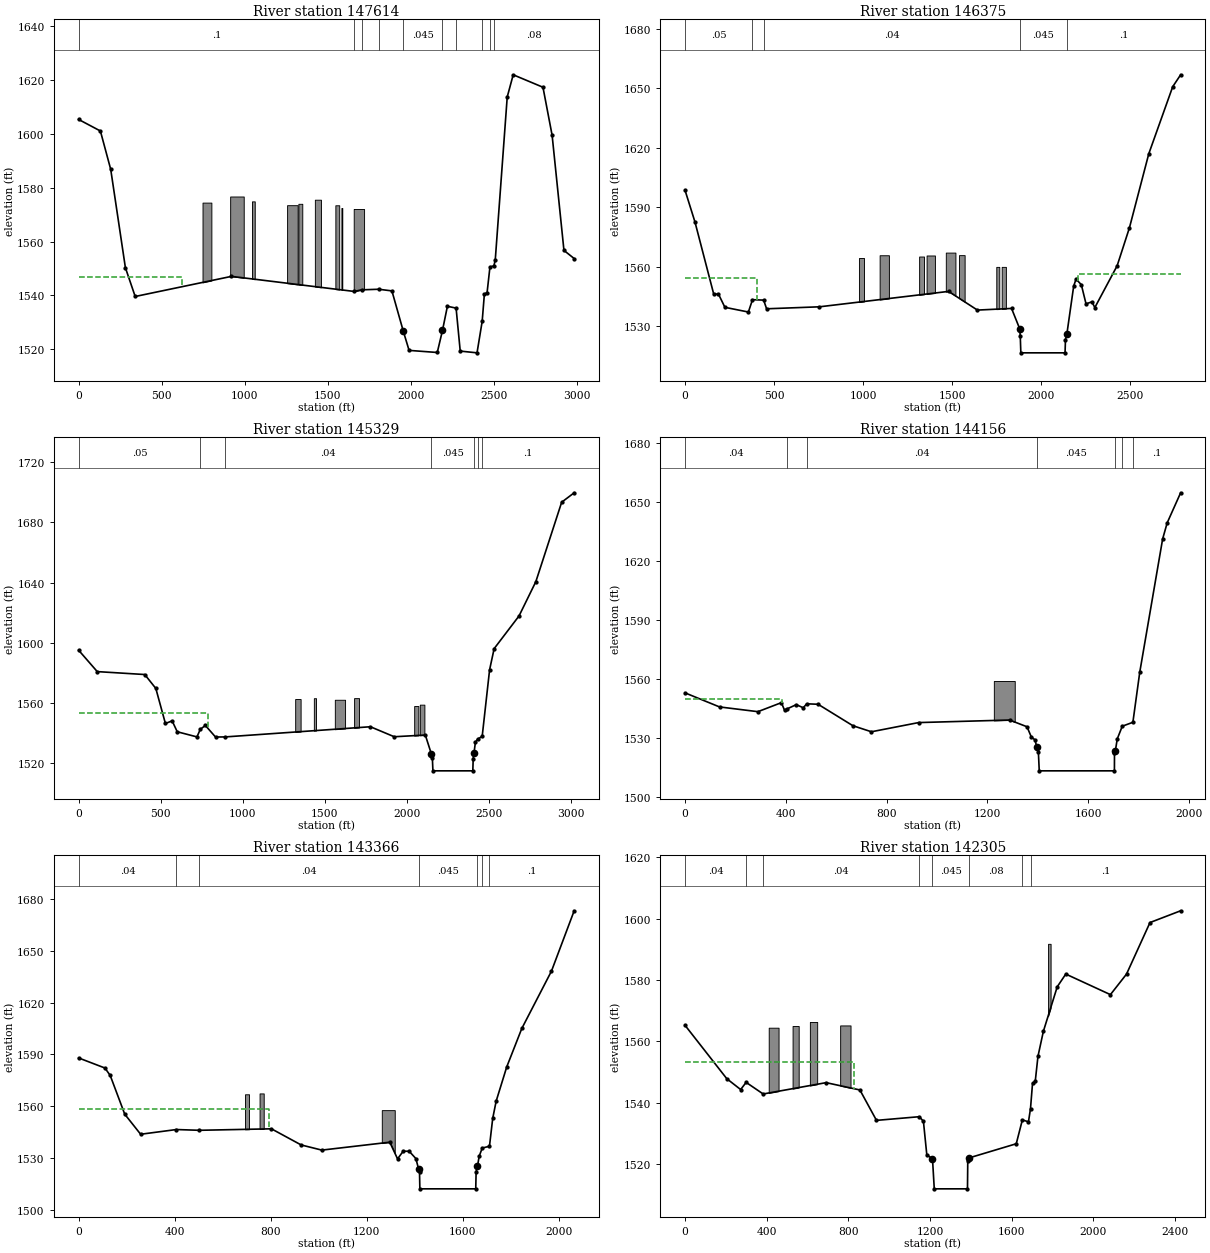
Type RM Length L Ch R = 1 ,147614  ,1238.7,1238.7,1238.7
BEGIN DESCRIPTION:
Channel burn based on the PMR model XS 20212
END DESCRIPTION:
XS GIS Cut Line= 3
     2066051.734      264291.984     2067028.239      266827.285
     2067284.315       266909.75
#Sta/Elev= 30
       0 1605.36   131.1 1601.08   193.4 1586.81   281.8 1550.32   340.8 1539.63
   920.9  1547.1  1659.9 1541.51  1704.8  1542.1  1807.8 1542.32  1887.7 1541.71
  1956.5  1526.7 1991.17 1519.62 2161.01 1518.84  2192.5 1527.07    2222 1535.99
  2274.4 1535.32 2299.33 1519.36 2400.57 1518.71  2431.6 1530.41  2444.8 1540.48
  2461.2  1541.1  2478.4 1550.59  2502.1 1550.99  2510.4 1553.18  2582.5 1613.71
  2618.5 1621.95  2797.9 1617.32    2853  1599.5  2924.3 1556.74  2985.9 1553.72
#Mann= 10 ,-1 , 0
       0      .1       0  1659.9    .016       0  1704.8     .06       0
  1807.8     .12       0  1956.5    .045       0  2192.5      .1       0
  2274.4    .045       0  2431.6     .08       0  2478.4    .016       0
  2502.1     .08       0
#XS Ineff= 2 , 0
          623.15 1546.88
Permanent Ineff=
       F       F
#Block Obstruct= 9 ,-1
  746.51  799.881574.491  913.06  994.791576.758 1044.43 1061.221574.947
 1256.06 1319.751573.534 1324.22 1347.631574.045 1423.42 1460.091575.569
 1546.93 1570.211573.499  1583.4 1588.751572.498 1657.52 1719.971572.112
Bank Sta=1956.5,2192.5
XS Rating Curve= 0 ,0
Exp/Cntr(USF)=0,0
Exp/Cntr=0.3,0.1

Type RM Length L Ch R = 1 ,146375  ,909,1045.3,1087.9
BEGIN DESCRIPTION:
Channel burn based on the PMR model XS 18976
END DESCRIPTION:
XS GIS Cut Line= 3
2065442.81325139264616.5751605632065702.84160273 267115.05966489
2065623.94346656267375.118527979
#Sta/Elev= 30
       0 1598.49    55.4 1582.62   160.9 1546.22   187.3 1546.28   223.6 1539.59
   355.5 1537.22   378.6 1543.44   441.3 1543.22   457.8 1538.85   754.6 1539.85
  1480.3 1547.62    1642  1538.2  1833.9 1539.03 1879.061528.905  1882.7 1525.36
    1886 1516.65  2134.4 1516.65  2136.7 1523.31 2144.691526.168  2182.9 1550.29
  2196.1 1553.81  2225.8 1551.01  2252.2 1541.35  2285.2 1542.35  2301.7 1539.48
    2427 1560.53  2496.3 1579.75  2604.7 1616.98  2739.1 1650.78  2783.7  1656.8
#Mann= 5 ,-1 , 0
       0     .05       0   378.6    .016       0   441.3     .04       0
 1879.06    .045       0 2144.69      .1       0
#XS Ineff= 2 , 0
          403.94 1554.12 2207.32         1556.23
Permanent Ineff=
       F       F
#Block Obstruct= 8 ,-1
  976.59 1005.12 1564.43 1092.78 1144.88 1565.84 1314.64 1341.84  1565.2
 1356.55  1403.4 1565.72 1464.51 1518.59 1567.18  1538.7 1570.29  1565.9
 1748.09 1765.03 1559.97 1778.52 1802.07 1559.98
Bank Sta=1879.06,2144.69
XS Rating Curve= 0 ,0
Exp/Cntr=0.3,0.1

Type RM Length L Ch R = 1 ,145329  ,1148.1,1173,1206.8
BEGIN DESCRIPTION:
Channel burn based on the PMR model XS 17934
END DESCRIPTION:
XS GIS Cut Line= 4
2065277.30570839264356.4864418952064646.67245522266421.412102059
2064591.46160764266783.9871643042064906.77593763 267162.30038406
#Sta/Elev= 30
       0 1595.06   113.4 1580.85   402.8 1578.91   470.2 1569.67   528.5 1546.39
   569.6 1548.14   600.6  1540.9   720.6 1537.49   741.2 1542.55     772 1545.08
   833.8 1537.41   892.1 1537.47  1777.2 1544.23  1922.4 1537.59  2111.6 1538.73
 2149.251525.939  2154.5 1523.74  2157.9 1514.95  2400.9 1514.95  2403.3 1522.99
 2407.951526.637  2416.8 1533.99  2429.7 1535.95  2458.1 1537.89  2503.1 1582.03
  2530.8  1596.1  2682.4 1617.81  2784.8 1640.58  2942.1 1693.33  3018.3 1699.61
#Mann= 7 ,-1 , 0
       0     .05       0   741.2    .016       0   892.1     .04       0
 2149.25    .045       0 2407.95      .1       0  2429.7    .016       0
  2458.1      .1       0
#XS Ineff= 2 , 0
          790.72 1553.37
Permanent Ineff=
       F       F
#Block Obstruct= 6 ,-1
 1318.94 1352.07 1562.63 1432.66 1446.04 1563.18 1560.45 1622.83 1562.15
 1677.75 1707.79 1563.24 2043.78 2069.31 1557.99 2078.16 2105.97 1558.91
Bank Sta=2149.25,2407.95
XS Rating Curve= 0 ,0
Exp/Cntr=0.3,0.1

Type RM Length L Ch R = 1 ,144156  ,625.3,790.1,863.3
BEGIN DESCRIPTION:
Channel burn based on the PMR model XS 16755
END DESCRIPTION:
XS GIS Cut Line= 2
2064008.34630406264726.8570922322063369.86660989266586.865183234
#Sta/Elev= 30
       0 1552.86   136.6 1545.73   288.9 1543.32   382.1  1547.9   394.8 1543.99
   405.1 1544.76   441.3  1546.9   468.9 1545.29   482.6 1547.32   527.8 1547.08
   665.9 1536.18   739.4 1533.11   926.7 1537.78  1287.5 1539.08  1356.9 1535.65
  1374.2 1530.38  1388.1 1529.05 1396.251525.255    1402 1522.75  1405.4 1513.26
  1703.7 1513.26    1704 1522.55 1707.621523.538    1715 1529.49  1734.9 1535.94
    1777 1537.92  1804.3 1563.43  1895.1 1631.09  1913.2 1639.28  1966.5 1654.53
#Mann= 7 ,-1 , 0
       0     .04       0   405.1    .016       0   482.6     .04       0
 1396.25    .045       0 1707.62      .1       0  1734.9    .016       0
    1777      .1       0
#XS Ineff= 2 , 0
           383.1 1549.55
Permanent Ineff=
       F       F
#Block Obstruct= 1 ,-1
 1225.18 1308.16 1558.91
Bank Sta=1396.25,1707.62
XS Rating Curve= 0 ,0
Exp/Cntr=0.3,0.1

Type RM Length L Ch R = 1 ,143366  ,727.3,1060.7,1196.7
BEGIN DESCRIPTION:
Channel burn based on the PMR model XS 15974
END DESCRIPTION:
Node Name=AP
XS GIS Cut Line= 3
2063785.88021356264606.972817555 2063511.7734783265081.517800227
2062471.37365621266184.911262721
#Sta/Elev= 30
       0 1587.99   109.6 1582.16   131.5 1577.87   192.1 1555.46   258.3 1543.85
   407.4 1546.58   502.8 1546.14   803.2    1547   927.1 1537.67  1013.2 1534.68
  1296.4 1539.26  1328.8  1529.6  1352.1 1534.03  1377.1 1534.04  1405.1 1529.78
 1416.031523.973  1420.2 1522.23  1421.7 1512.28  1654.5 1512.28  1656.1 1522.22
 1661.691525.231  1668.8 1531.13  1681.6 1535.87  1711.7 1536.92  1725.2 1553.01
  1739.6 1563.02  1783.7 1582.83  1846.4 1605.03  1970.1 1638.24  2064.6 1673.11
#Mann= 7 ,-1 , 0
       0     .04       0   407.4    .016       0   502.8     .04       0
 1416.03    .045       0 1661.69      .1       0  1681.6    .016       0
  1711.7      .1       0
#XS Ineff= 2 , 0
          794.37 1558.19
Permanent Ineff=
       F       F
#Block Obstruct= 3 ,-1
  693.25   709.9 1566.97  753.81  771.13 1567.47 1263.08 1317.05  1557.8
Bank Sta=1416.03,1661.69
XS Rating Curve= 0 ,0
Exp/Cntr=0.3,0.1

Type RM Length L Ch R = 1 ,142305  ,1322.7,1458.5,1503.3
BEGIN DESCRIPTION:
Channel burn based on the PMR model XS 14902
END DESCRIPTION:
XS GIS Cut Line= 5
2063456.66007148264380.0697280622063196.55166781264829.275194481
2062660.58817281264931.7074043152061943.41080138264821.397257477
2061525.64392039264340.580305725
#Sta/Elev= 30
       0 1565.21   204.2 1547.82   272.1 1544.28     299 1546.62   382.4 1542.83
   690.8 1546.53   856.2 1544.14   937.5 1534.22  1147.5 1535.42  1167.4  1533.9
    1184 1522.96 1211.831521.672  1220.5 1511.88  1383.2 1511.88  1384.6 1521.02
  1391.61521.985  1622.1 1526.59    1652 1534.38  1681.9 1533.75  1691.9 1538.07
  1701.8 1546.28  1715.1 1546.94  1728.4  1555.1  1754.9 1563.27  1822.9 1577.82
  1864.7 1581.96  2083.3 1575.25  2162.2 1581.95  2277.2 1598.77  2427.3 1602.61
#Mann= 8 ,-1 , 0
       0     .04       0     299    .016       0   382.4     .04       0
  1147.5     .08       0 1211.83    .045       0  1391.6     .08       0
    1652    .016       0  1691.9      .1       0
#XS Ineff= 2 , 0
          829.58 1553.17
Permanent Ineff=
       F       F
#Block Obstruct= 5 ,-1
  409.61  457.81 1564.46  526.48  556.42 1565.01  611.21  646.99 1566.33
  759.52  810.35  1565.2 1777.96 1790.35 1591.83
Bank Sta=1211.83,1391.6
XS Rating Curve= 0 ,0
Exp/Cntr=0.3,0.1

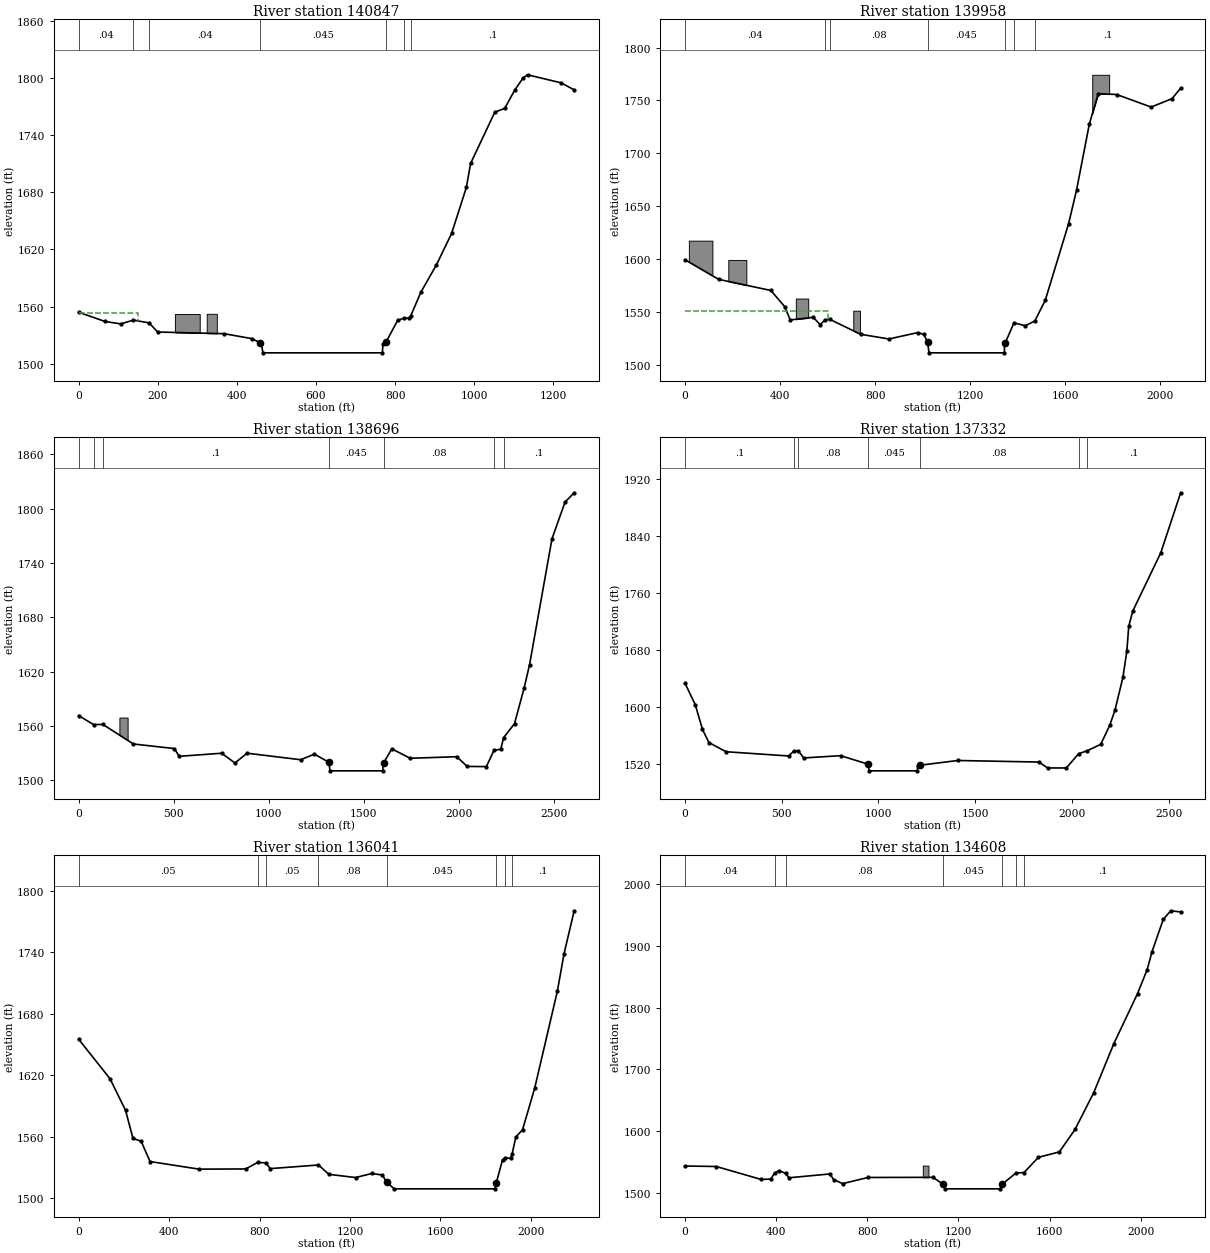
Type RM Length L Ch R = 1 ,140847  ,910.4,888.8,859.7
BEGIN DESCRIPTION:
Channel burn based on the PMR model XS 13447
END DESCRIPTION:
XS GIS Cut Line= 2
2063338.43360189 263741.637605982062195.61436522263229.260021806
#Sta/Elev= 30
       0 1553.95    66.6 1544.31   106.2 1541.76   138.5 1545.73   178.1 1542.83
   199.7 1533.25   367.6 1531.49     437 1526.35     4591522.033   462.1 1520.44
   465.7 1511.38   767.7 1511.38     769 1520.25  777.031522.819   806.3 1545.52
   821.2  1547.6   836.1 1547.86   839.7 1550.53   864.8 1574.92   904.4 1603.82
   942.6 1636.69   979.9 1684.99   990.7 1710.27  1051.8 1764.03    1077 1768.08
  1102.1 1787.15  1123.7 1800.19  1134.5 1803.29  1219.1 1794.85  1252.4 1787.47
#Mann= 7 ,-1 , 0
       0     .04       0   138.5    .016       0   178.1     .04       0
     459    .045       0  777.03      .1       0   821.2    .016       0
   839.7      .1       0
#XS Ineff= 2 , 0
          149.07 1552.76
Permanent Ineff=
       F       F
#Block Obstruct= 2 ,-1
   243.3  306.03 1552.16  323.68  349.24 1552.37
Bank Sta=459,777.03
XS Rating Curve= 0 ,0
Exp/Cntr=0.3,0.1

Type RM Length L Ch R = 1 ,139958  ,1245.4,1261.6,1318.8
BEGIN DESCRIPTION:
Channel burn based on the PMR model XS 12545
END DESCRIPTION:
Node Name=AO
XS GIS Cut Line= 3
2064197.55097814 263363.360803472063464.58623672262772.185148567
2062353.26267198 262504.20307298
#Sta/Elev= 30
       0 1599.15   140.7 1580.62   360.8 1570.07   419.1 1554.72   442.4 1542.21
   539.5 1544.65   568.4 1537.59   586.6 1541.93   608.6 1542.75   738.7 1528.58
   857.3 1524.16   979.8 1530.24  1004.3 1528.47 1020.271521.177    1026 1511.04
  1343.2 1511.04  1344.2 1519.66 1346.21 1520.12  1383.7 1539.49    1431 1536.66
  1471.5 1541.23  1515.3 1560.84  1613.4 1633.27    1647  1665.2  1700.9 1727.82
  1738.1 1756.34  1815.7 1755.54  1960.8 1743.64  2048.6 1751.64  2084.8 1761.51
#Mann= 7 ,-1 , 0
       0     .04       0   586.6    .016       0   608.6     .08       0
 1020.27    .045       0 1346.21     .08       0  1383.7    .016       0
  1471.5      .1       0
#XS Ineff= 2 , 0
             600 1550.88
Permanent Ineff=
       F       F
#Block Obstruct= 5 ,-1
   15.81  114.85 1617.23  181.75  257.64 1598.98  465.88  518.04 1562.43
   707.5  735.63 1550.96  1712.9 1784.08 1774.21
Bank Sta=1020.27,1346.21
XS Rating Curve= 0 ,0
Exp/Cntr=0.3,0.1

Type RM Length L Ch R = 1 ,138696  ,1421.8,1364,1197.3
BEGIN DESCRIPTION:
Channel burn based on the PMR model XS 11287
END DESCRIPTION:
XS GIS Cut Line= 5
2065048.81010239262023.4852023872064749.31234181262031.380855888
2062941.09571609261206.9029931342062660.48015124261081.910350288
2062650.86328117261075.504229063
#Sta/Elev= 30
       0 1571.49    78.3 1561.59   127.5  1561.7   288.3 1540.08   503.6 1535.04
   528.8 1526.48   752.4 1529.88   821.7 1519.11   885.8 1529.92    1167 1522.72
  1240.2 1528.86 1316.131519.856  1321.7 1510.44  1599.7 1510.44  1600.8 1518.81
  1604.71519.517  1646.6 1534.79    1743 1524.32  1988.2 1526.04  2043.2 1515.31
  2144.2 1515.12  2183.7 1533.04  2219.9 1534.29  2234.4 1547.05    2292 1562.59
    2343  1602.3    2371 1627.56  2489.1 1766.82  2557.8 1807.37  2605.7 1817.58
#Mann= 7 ,-1 , 0
       0      .1       0    78.3    .016       0   127.5      .1       0
 1316.13    .045       0  1604.7     .08       0  2183.7    .016       0
  2234.4      .1       0
#Block Obstruct= 1 ,-1
  214.38  257.59 1569.33
Bank Sta=1316.13,1604.7
XS Rating Curve= 0 ,0
Exp/Cntr=0.3,0.1

Type RM Length L Ch R = 1 ,137332  ,1225.7,1291.8,1044.6
BEGIN DESCRIPTION:
Channel burn based on the PMR model XS 9946
END DESCRIPTION:
XS GIS Cut Line= 4
2065419.30476822  260604.85811842063295.11672676260152.875744342
2062926.46059397260064.3017475152062916.99979273260057.351466272
#Sta/Elev= 30
       0 1632.54    52.9 1602.43    89.8 1567.85   123.4 1549.42     212 1536.56
     536  1530.6   562.8 1537.74   586.3 1537.65   613.1 1527.82   804.3 1531.04
   944.71519.223   952.1 1509.72    1201 1509.72  1203.5 1516.55 1213.671517.564
    1410 1524.26  1830.7 1522.05  1874.3 1513.77  1971.6 1513.76  2035.3 1533.83
  2078.9 1537.86  2149.4 1546.96  2196.5 1573.93  2223.5  1595.5    2264 1640.92
  2284.2 1677.53  2294.3 1712.74  2314.6 1733.93  2459.7 1815.96  2562.6 1900.38
#Mann= 7 ,-1 , 0
       0      .1       0   562.8    .016       0   586.3     .08       0
   944.7    .045       0 1213.67     .08       0  2035.3    .016       0
  2078.9      .1       0
Bank Sta=944.7,1213.67
XS Rating Curve= 0 ,0
Exp/Cntr=0.3,0.1

Type RM Length L Ch R = 1 ,136041  ,1430,1432.3,1418.9
BEGIN DESCRIPTION:
Channel burn based on the PMR model XS 8724
END DESCRIPTION:
Node Name=AN
XS GIS Cut Line= 2
2065624.27253413259241.367735147 2063433.2086748259186.090942815
#Sta/Elev= 30
       0 1655.07   138.7 1616.45   207.6 1585.55   240.4 1558.17   276.5 1555.39
   315.9 1535.58   532.5 1528.16   739.3 1528.35   791.8 1534.71   827.9 1534.28
   847.6 1528.67  1060.9 1532.21  1106.8 1523.07    1225 1519.96  1297.2 1523.93
  1343.1 1522.41 1362.891515.359    1396 1508.92    1842 1508.92 1847.761515.109
  1874.8 1537.14  1885.8 1539.19  1910.9  1538.7  1917.5  1543.2  1933.8 1559.47
  1963.4  1566.6  2017.1 1607.18  2117.7 1702.23  2147.2 1738.73  2191.8 1780.48
#Mann= 8 ,-1 , 0
       0     .05       0   791.8    .016       0   827.9     .05       0
  1060.9     .08       0 1362.89    .045       0 1847.76     .08       0
  1885.8    .016       0  1917.5      .1       0
Bank Sta=1362.89,1847.76
XS Rating Curve= 0 ,0
Exp/Cntr=0.3,0.1

Type RM Length L Ch R = 1 ,134608  ,1102.3,1153.8,1180.4
BEGIN DESCRIPTION:
Channel burn based on the PMR model XS 7288
END DESCRIPTION:
XS GIS Cut Line= 2
2065182.93877114257798.9943075632063007.64948656257775.245667398
#Sta/Elev= 30
       0 1543.78   136.9 1542.98   333.8 1522.07   376.5 1522.63   392.9 1532.43
   412.5 1536.34   442.1  1531.8   455.2 1524.72   635.7 1530.94   652.1 1521.81
   691.4 1515.28     803 1525.24  1088.4 1525.48 1133.58 1513.98  1140.9 1506.86
  1383.7 1506.86  1392.41514.346  1451.4 1532.24  1487.9 1533.22  1551.1 1557.89
  1642.9 1566.54  1711.8 1602.91  1793.9  1662.4  1882.4 1741.81  1986.2 1822.55
  2028.6  1861.5  2049.8 1890.27    2099 1942.51  2131.8 1956.47  2175.4 1954.57
#Mann= 7 ,-1 , 0
       0     .04       0   392.9    .016       0   442.1     .08       0
 1133.58    .045       0  1392.4     .08       0  1451.4    .016       0
  1487.9      .1       0
#Block Obstruct= 1 ,-1
 1043.51 1068.32 1544.52
Bank Sta=1133.58,1392.4
XS Rating Curve= 0 ,0
Exp/Cntr=0.3,0.1

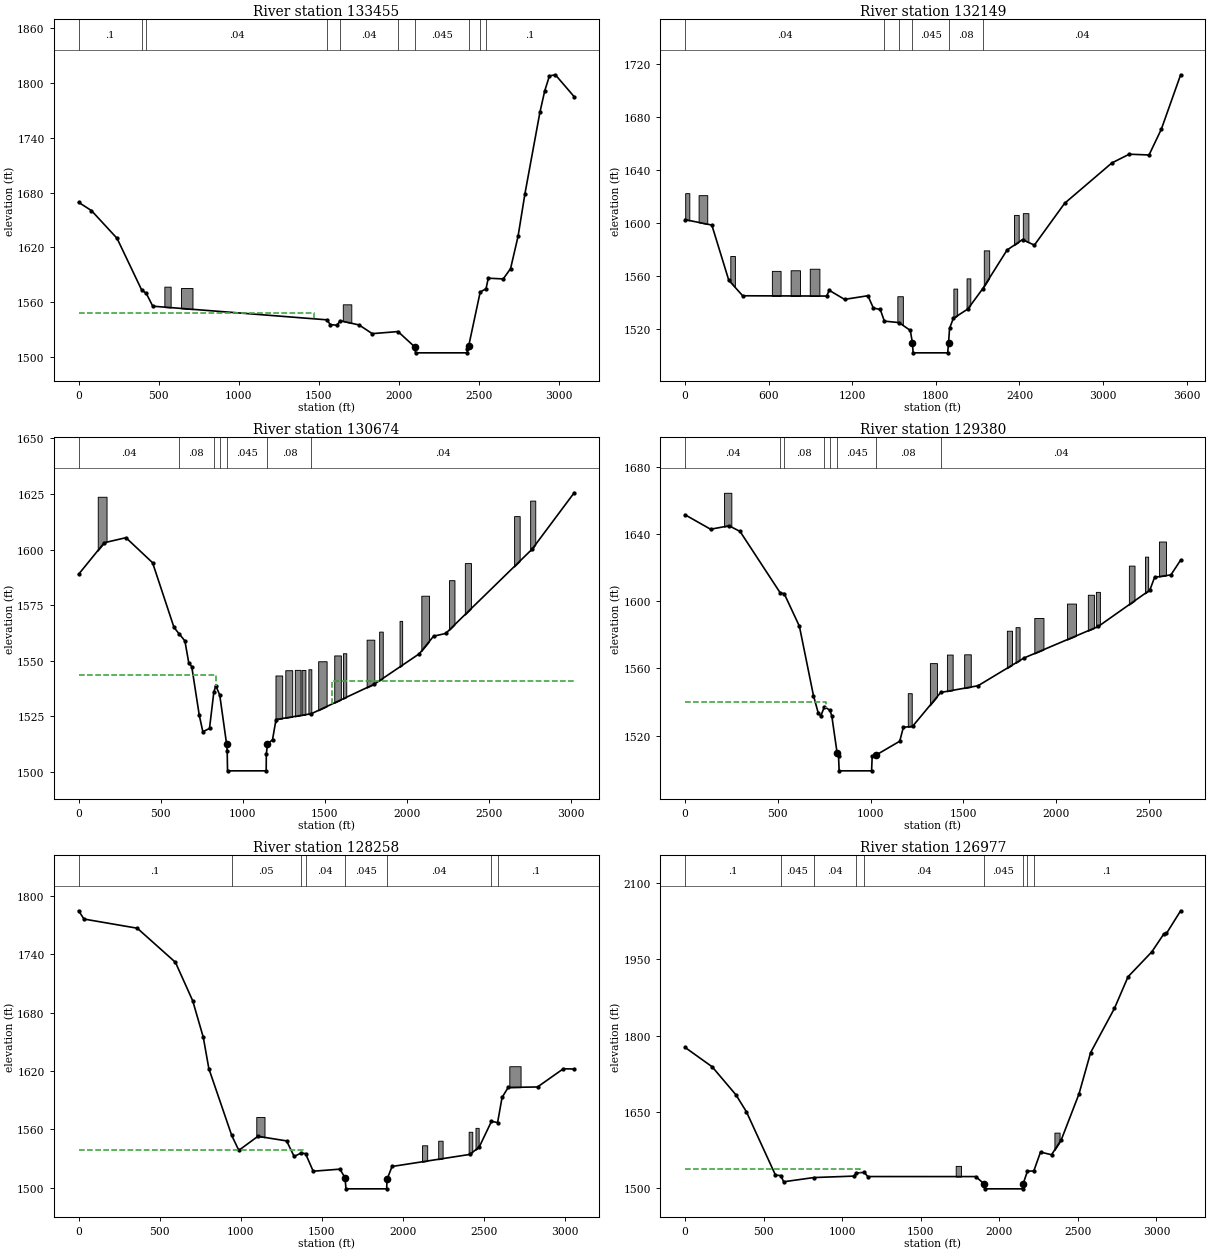
Type RM Length L Ch R = 1 ,133455  ,1276.6,1305.9,1311.4
BEGIN DESCRIPTION:
Channel burn based on the PMR model XS 6138
END DESCRIPTION:
XS GIS Cut Line= 4
2066306.18422805256512.1245059822065200.19890723256696.458782971
2064316.00415331256687.6615564822063244.12079839256498.467709139
#Sta/Elev= 30
       0  1669.3    80.2 1660.22   239.8 1629.88   392.8 1573.58   422.8 1569.49
   462.7 1555.57    1551 1540.62  1570.7  1535.4  1613.4 1534.72  1633.1 1539.71
  1751.2    1535  1833.2  1525.5    1994 1527.78 2097.291511.198  2103.7 1504.49
  2426.9 1504.49  2427.3  1509.1 2434.981511.742  2507.2 1571.08  2543.6 1574.69
  2557.6 1586.22  2651.1 1585.42  2696.8 1596.77  2743.4 1631.92  2786.7 1678.87
    2880 1767.88    2910  1791.3  2939.4 1807.71  2976.5 1808.96  3093.9 1784.96
#Mann= 10 ,-1 , 0
       0      .1       0   392.8    .016       0   422.8     .04       0
    1551    .016       0  1633.1     .04       0    1994     .08       0
 2097.29    .045       0 2434.98     .08       0  2507.2    .016       0
  2543.6      .1       0
#XS Ineff= 2 , 0
         1469.01 1548.37
Permanent Ineff=
       F       F
#Block Obstruct= 3 ,-1
  535.23   574.4 1576.95     639  710.76  1575.5  1649.3 1702.43 1557.62
Bank Sta=2097.29,2434.98
XS Rating Curve= 0 ,0
Exp/Cntr=0.3,0.1

Type RM Length L Ch R = 1 ,132149  ,1608.3,1474.8,1148.8
BEGIN DESCRIPTION:
Channel burn based on the PMR model XS 4840
END DESCRIPTION:
Node Name=AM
XS GIS Cut Line= 5
2066057.66832089255441.1830783042065314.81941289 255392.65233548
2064545.53059714255414.7809001512063617.00555131 255213.55820547
2062900.36295572256038.336411566
#Sta/Elev= 30
       0 1602.56   191.9 1598.47   313.5 1556.89   413.3 1545.17  1016.6 1544.96
    1034 1549.33  1144.6 1542.45    1312 1545.21  1351.4 1535.91  1400.7 1534.88
  1430.2 1526.07    1536 1524.94  1616.3 1519.06 1631.991509.451  1636.4 1502.16
  1884.8 1502.16  1890.81509.708  1898.3 1520.64    1925 1528.11  2029.2 1535.19
  2135.3 1550.38    2311 1579.66  2421.7 1587.53  2506.8 1583.34  2724.1 1614.88
  3063.1 1645.29    3188 1651.88  3329.9  1651.3  3418.2 1670.75  3556.7 1711.75
#Mann= 6 ,-1 , 0
       0     .04       0  1430.2    .016       0    1536     .08       0
 1631.99    .045       0  1890.8     .08       0  2135.3     .04       0
#Block Obstruct= 12 ,-1
     .65   30.19 1622.53   96.87  159.04 1621.01  324.44  357.41 1575.17
  622.83  685.32 1563.94  757.51  824.44  1564.4  894.78  963.97 1565.56
 1523.37 1563.01 1544.83 1925.66 1952.78 1550.58 2020.28 2047.29 1558.29
 2143.86 2182.52  1579.4 2360.97 2394.42 1606.12 2424.02 2464.12 1607.45
Bank Sta=1631.99,1890.8
XS Rating Curve= 0 ,0
Exp/Cntr=0.3,0.1

Type RM Length L Ch R = 1 ,130674  ,1399.3,1293.5,1023.6
BEGIN DESCRIPTION:
Channel burn based on linear interpolation between effective XS DV and DW
END DESCRIPTION:
XS GIS Cut Line= 2
2065114.76075789253289.1673692322062767.53841822255191.945059732
#Sta/Elev= 30
       0 1588.93   156.1  1603.1   288.5 1605.37     451  1594.1   581.6    1565
   611.5 1562.27     648 1558.96   671.3 1549.18   689.7 1547.41   735.5 1525.58
   757.4 1518.12     798 1519.61   824.2  1535.8   836.1 1538.86   860.4 1534.63
  902.211512.591   905.8 1509.57   907.9 1500.54  1143.7 1500.54  1144.4    1508
 1151.551512.553  1182.4 1514.56  1203.5 1523.61  1418.9 1526.22  1803.2 1539.52
  2076.8 1553.15  2164.1 1561.07  2238.2 1562.31  2764.9 1600.19  3021.6 1625.56
#Mann= 7 ,-1 , 0
       0     .04       0   611.5     .08       0   824.2    .016       0
   860.4     .04       0  902.21    .045       0 1151.55     .08       0
  1418.9     .04       0
#XS Ineff= 2 , 0
          838.03 1543.44 1545.92          1540.8
Permanent Ineff=
       F       F
#Block Obstruct= 17 ,-1
  116.53  170.26 1623.77 1200.25 1241.21 1543.41 1260.25 1302.17 1545.79
 1318.31 1353.03 1545.94  1359.7  1382.8 1545.89 1401.14 1418.82 1546.22
  1460.6 1512.07 1549.81 1558.55 1598.91 1552.43 1611.61 1631.78 1553.41
 1756.09 1802.84 1559.51 1832.36 1854.42 1563.14  1956.9 1972.61 1567.97
 2089.58 2136.71 1579.28 2258.13 2291.62 1586.26 2354.96 2392.16 1593.95
 2655.25 2689.25 1615.07 2753.11 2784.31 1622.04
Bank Sta=902.21,1151.55
XS Rating Curve= 0 ,0
Exp/Cntr=0.3,0.1

Type RM Length L Ch R = 1 ,129380  ,1094.7,1122.6,1188.4
BEGIN DESCRIPTION:
Channel burn based on effective XS DV
END DESCRIPTION:
XS GIS Cut Line= 3
2063267.53840247252546.1117687232063093.92752922254316.944841221
 2062698.0940033255115.556104898
#Sta/Elev= 30
       0 1651.55   137.5 1642.94   236.9 1645.01   296.2 1641.63   513.8 1604.85
   533.8 1604.64     616 1585.16   691.8 1543.86   718.2  1533.2   731.4 1531.71
   751.2 1537.28   780.8 1534.99   790.7 1531.67  819.211509.696     827 1507.57
   830.3    1499  1005.1    1499  1008.3 1507.62 1028.93 1508.39  1156.6 1516.64
  1176.4 1524.93  1225.9 1525.51  1377.5 1545.69  1578.6 1549.69  1827.3 1566.28
  2226.5    1585  2504.8  1606.7  2530.4 1614.33  2618.3 1615.75  2670.7 1624.55
#Mann= 8 ,-1 , 0
       0     .04       0   513.8    .016       0   533.8     .08       0
   751.2    .016       0   780.8     .08       0  819.21    .045       0
 1028.93     .08       0  1377.5     .04       0
#XS Ineff= 2 , 0
          760.56 1540.03
Permanent Ineff=
       F       F
#Block Obstruct= 14 ,-1
  209.77  249.27 1664.67 1200.15 1221.39 1545.27 1319.38 1357.33 1563.18
 1411.09 1441.98 1568.27 1503.99 1539.62 1568.43 1734.18 1761.85 1582.48
    1781  1802.7  1584.6 1882.06 1931.36 1590.09 2057.92 2106.71 1598.66
 2170.54 2203.28 1603.91 2213.88 2235.51 1605.63 2391.75 2422.14 1621.27
 2478.63 2495.58 1626.62 2553.77 2591.57 1635.63
Bank Sta=819.21,1028.93
XS Rating Curve= 0 ,0
Exp/Cntr=0.3,0.1

Type RM Length L Ch R = 1 ,128258  ,904.6,1281.1,1408.2
BEGIN DESCRIPTION:
Channel burn based on effective XS DU
END DESCRIPTION:
Node Name=AL
XS GIS Cut Line= 2
2062580.03846514251726.6672133952061670.31620322254643.333952233
#Sta/Elev= 30
       0 1784.84    33.1 1776.33   361.5 1766.91   596.7 1731.88   703.3 1692.29
   768.6  1654.7   802.9 1622.49   943.8 1553.84   987.6 1538.47  1105.4 1552.93
  1282.2 1548.19  1328.7 1532.22  1370.4 1535.58  1398.9 1535.17  1446.1 1517.03
  1611.1 1519.15 1642.351510.269  1648.4  1498.9  1899.2  1498.9 1901.331508.587
  1932.3 1521.89  2411.3 1534.28  2469.7 1541.86  2545.3 1568.29  2583.1 1567.03
  2610.6 1592.87  2648.4 1603.18  2829.2 1603.65  2988.7 1622.41  3055.2 1622.09
#Mann= 8 ,-1 , 0
       0      .1       0   943.8     .05       0  1370.4    .016       0
  1398.9     .04       0 1642.35    .045       0 1901.33     .04       0
  2545.3    .016       0  2583.1      .1       0
#XS Ineff= 2 , 0
          1386.2 1538.44
Permanent Ineff=
       F       F
#Block Obstruct= 6 ,-1
 1095.26    1146 1572.82 2117.28 2149.05 1543.67 2216.85 2244.06 1548.39
 2404.64 2426.94 1557.58  2446.8 2466.23 1561.61 2655.25 2724.79    1625
Bank Sta=1642.35,1901.33
XS Rating Curve= 0 ,0
Exp/Cntr=0.3,0.1

Type RM Length L Ch R = 1 ,126977  ,1030.9,1036.1,1027.4
BEGIN DESCRIPTION:
Channel burn based on effective XS DT
END DESCRIPTION:
XS GIS Cut Line= 3
2062479.53571243251764.2497970322061589.15406758252507.146982991
2059907.55004372253579.232077807
#Sta/Elev= 30
       0 1776.52   172.2  1738.4   323.6 1683.05   390.1 1649.82   575.2 1524.74
   609.9 1523.81     627  1511.6   819.3 1519.96  1075.6 1522.82  1089.9 1528.97
  1141.2  1530.2  1162.2 1521.93  1849.6 1521.86  1901.1 1508.02  1906.8  1497.7
  2149.2  1497.7  2150.6 1506.89  2179.1 1532.66  2219.3 1532.85  2262.1 1570.21
  2332.1  1564.9  2394.4  1594.5  2506.8 1684.67  2581.1 1766.48  2732.8 1853.66
  2819.2 1915.88  2970.4 1964.96  3046.4  2000.1  3063.6 2001.24  3153.9 2045.98
#Mann= 9 ,-1 , 0
       0      .1       0   609.9    .045       0   819.3     .04       0
  1089.9    .016       0  1141.2     .04       0  1901.1    .045       0
  2150.6     .08       0  2179.1    .016       0  2219.3      .1       0
#XS Ineff= 2 , 0
         1116.06 1537.69
Permanent Ineff=
       F       F
#Block Obstruct= 2 ,-1
 1722.28 1756.15 1542.93 2350.56 2383.54 1608.54
Bank Sta=1901.1,2150.6
XS Rating Curve= 0 ,0
Exp/Cntr=0.3,0.1