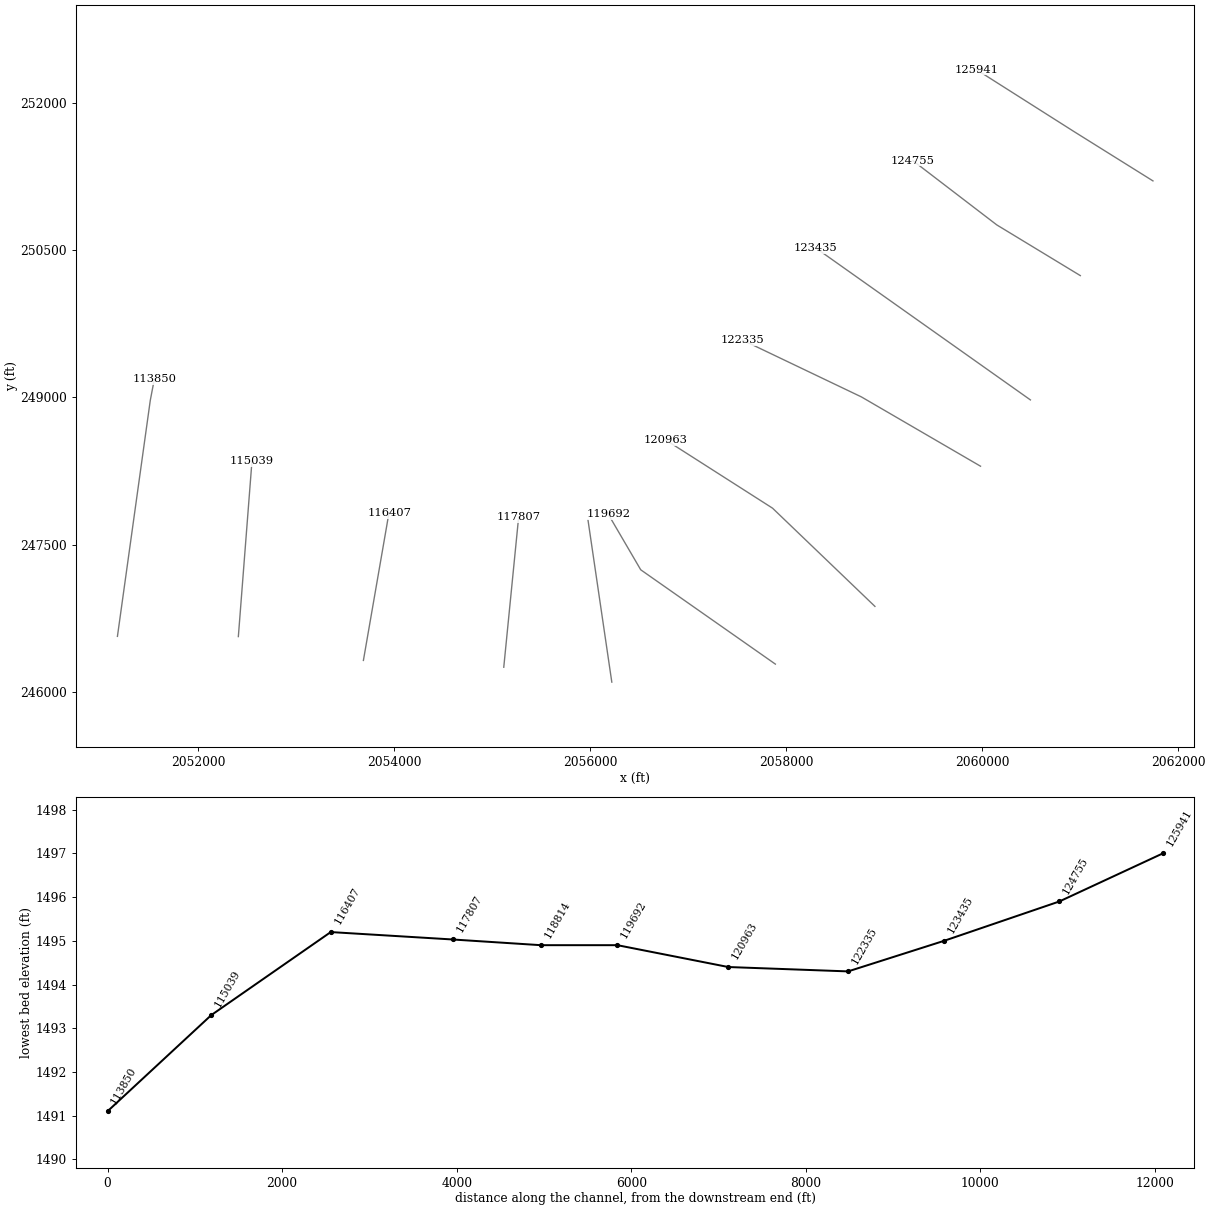
HEC-RAS study GREENBRRV.prj: GREENBRRV

--- GREENBRRV.g01 (geometry) --- (continued)

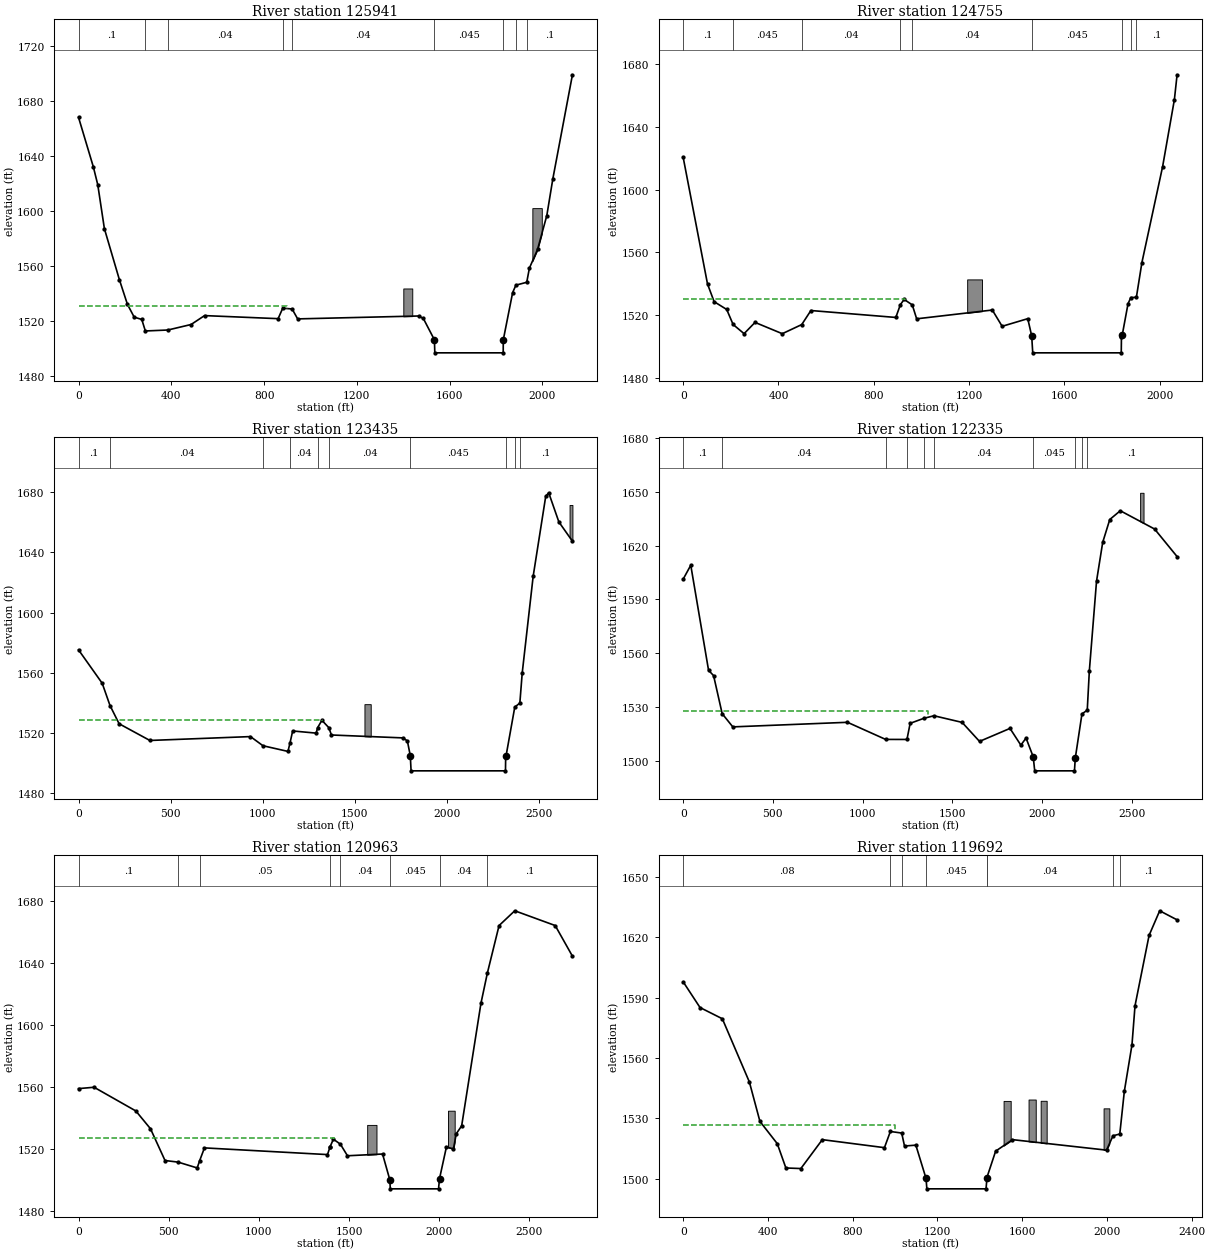
Type RM Length L Ch R = 1 ,125941  ,1220.9,1185.8,1154.8
BEGIN DESCRIPTION:
Channel burn based on effective XS DS
END DESCRIPTION:
XS GIS Cut Line= 3
2061743.78712436251209.3276122082060941.04251643251710.738720988
2059941.86460763252344.745701641
#Sta/Elev= 30
       0  1668.3    63.9 1632.26    82.9  1619.3   111.4  1587.4   175.9 1550.36
   210.8 1532.29     240 1522.96   272.6 1521.31   288.1 1512.91   385.2 1513.61
   485.3 1517.62   543.4  1524.1   860.6 1521.87   880.5 1529.48     921 1528.92
   944.8  1521.7  1466.4 1523.81  1486.8 1522.02  1534.6 1506.48  1536.3    1497
  1831.3    1497  1831.5 1506.33  1871.9 1540.82    1886 1546.26  1932.7 1548.34
  1944.3  1558.7  1979.3  1572.2  2019.3 1596.92  2045.3 1623.65  2129.8 1699.34
#Mann= 9 ,-1 , 0
       0      .1       0   288.1    .045       0   385.2     .04       0
   880.5    .016       0     921     .04       0  1534.6    .045       0
  1831.5     .08       0    1886    .016       0  1932.7      .1       0
#XS Ineff= 2 , 0
          897.18 1531.41
Permanent Ineff=
       F       F
#Block Obstruct= 2 ,-1
 1400.46 1439.12 1543.84 1956.94 1997.62 1602.31
Bank Sta=1534.6,1831.5
XS Rating Curve= 0 ,0
Exp/Cntr=0.3,0.1

Type RM Length L Ch R = 1 ,124755  ,1265.3,1319.7,1316.4
BEGIN DESCRIPTION:
Channel burn based on effective XS DR
END DESCRIPTION:
Node Name=AK
XS GIS Cut Line= 3
2061002.72023077250243.308163419 2060150.1267252250760.541277357
 2059295.6067138251414.648808554
#Sta/Elev= 30
       0  1620.6   102.1 1539.84   129.8 1528.56   182.7 1523.58   209.5    1514
   255.6 1508.14   301.6 1515.33     416 1508.12   497.7 1513.95   536.1 1522.91
   892.6 1518.49   911.8 1526.68   927.6 1529.99   961.7  1526.5   980.1 1517.62
  1297.7 1523.23    1339 1512.84  1446.5 1517.71    1463 1506.75  1467.4  1495.9
    1839  1495.9  1839.8 1505.98  1843.1 1507.22  1867.4  1527.2  1879.1 1531.18
  1902.5 1531.35  1925.7 1553.53  2012.6 1614.74  2062.1 1657.56  2073.4 1673.39
#Mann= 9 ,-1 , 0
       0      .1       0   209.5    .045       0   497.7     .04       0
   911.8    .016       0   961.7     .04       0    1463    .045       0
  1843.1     .08       0  1879.1    .016       0  1902.5      .1       0
#XS Ineff= 2 , 0
          929.58 1530.53
Permanent Ineff=
       F       F
#Block Obstruct= 1 ,-1
 1192.14 1254.45 1542.78
Bank Sta=1463,1843.1
XS Rating Curve= 0 ,0
Exp/Cntr=0.3,0.1

Type RM Length L Ch R = 1 ,123435  ,999.6,1100.7,1117.7
BEGIN DESCRIPTION:
Channel burn based on effective XS DQ
END DESCRIPTION:
XS GIS Cut Line= 3
2060493.35124289248975.3581440032058425.22328398 250438.74852939
2058303.46401305250524.396652058
#Sta/Elev= 30
       0 1575.27   128.5 1553.11   170.8 1538.36   220.3 1526.25   387.4 1515.16
   933.8 1517.73  1001.7 1511.65  1137.3 1507.89  1148.7 1513.61  1162.9 1521.47
  1290.7 1520.02  1298.2 1523.61  1321.8 1528.53  1358.8 1523.72  1373.6 1518.79
  1762.1 1516.86  1785.9 1514.86  1801.9 1504.97    1806    1495  2318.8    1495
  2319.7 1504.02  2322.1 1505.08  2369.2  1537.3  2396.8    1540  2409.6 1559.89
  2469.1  1624.1  2537.4 1677.23  2553.5 1679.53  2608.7 1660.19  2682.4 1647.39
#Mann= 10 ,-1 , 0
       0      .1       0   170.8     .04       0  1001.7    .045       0
  1148.7     .04       0  1298.2    .016       0  1358.8     .04       0
  1801.9    .045       0  2322.1     .08       0  2369.2    .016       0
  2396.8      .1       0
#XS Ineff= 2 , 0
         1323.38 1528.89
Permanent Ineff=
       F       F
#Block Obstruct= 2 ,-1
 1552.77 1586.86 1539.25 2666.74 2682.37 1671.45
Bank Sta=1801.9,2322.1
XS Rating Curve= 0 ,0
Exp/Cntr=0.3,0.1

Type RM Length L Ch R = 1 ,122335  ,1433.4,1371.9,1350.5
BEGIN DESCRIPTION:
Channel burn based on effective XS DP
END DESCRIPTION:
Node Name=AJ
XS GIS Cut Line= 3
2059984.44118859248299.0993200062058768.94859009249005.918009854
2057554.38644297249586.372281387
#Sta/Elev= 30
       0 1601.39    42.2 1609.13   141.3 1550.48   169.4 1547.47   217.2 1526.23
   276.4 1518.85   915.5 1521.41  1128.1 1511.85  1246.9 1511.83  1264.7 1520.83
  1340.5 1523.62  1397.5 1525.06  1554.2 1521.36  1651.3 1510.74  1821.1    1518
  1881.5 1508.67  1910.6  1512.6  1950.6  1502.1  1958.8  1494.3  2180.3  1494.3
  2184.9 1501.39  2222.1  1526.1  2251.6 1528.18  2263.3 1550.22  2303.3 1600.23
  2337.7 1621.92  2377.1 1634.67  2435.7 1639.57  2626.9 1629.35  2752.2 1613.97
#Mann= 10 ,-1 , 0
       0      .1       0   217.2     .04       0  1128.1    .045       0
  1246.9     .04       0  1340.5    .016       0  1397.5     .04       0
  1950.6    .045       0  2184.9     .08       0  2222.1    .016       0
  2251.6      .1       0
#XS Ineff= 2 , 0
         1365.13    1528
Permanent Ineff=
       F       F
#Block Obstruct= 1 ,-1
 2546.24  2565.2  1649.6
Bank Sta=1950.6,2184.9
XS Rating Curve= 0 ,0
Exp/Cntr=0.3,0.1

Type RM Length L Ch R = 1 ,120963  ,1282.8,1270.8,1247.8
BEGIN DESCRIPTION:
Channel burn based on effective XS DO
END DESCRIPTION:
XS GIS Cut Line= 3
2058906.79676422246869.2582242312057862.04771063247871.129217094
2056773.13636506 248566.40712972
#Sta/Elev= 30
       0 1559.05    86.1 1559.92   317.8 1544.63     399 1533.16   479.6 1512.67
   552.1 1511.64     658 1507.88   671.7 1512.56   698.3 1520.81  1380.8 1516.49
  1394.4 1521.34  1394.4 1521.35  1413.4 1526.42  1452.4 1523.19  1491.6 1515.73
  1686.2 1516.86  1726.7 1500.14    1729  1494.4  1996.6  1494.4  2002.3 1501.04
  2040.4 1521.38  2079.4 1520.15  2094.9  1529.9  2124.9 1535.01  2231.8 1613.98
  2267.4 1633.51  2332.4 1664.21  2419.5 1673.75  2643.8 1664.23  2739.4 1644.48
#Mann= 8 ,-1 , 0
       0      .1       0   552.1    .045       0   671.7     .05       0
  1394.4    .016       0  1452.4     .04       0  1726.7    .045       0
  2002.3     .04       0  2267.4      .1       0
#XS Ineff= 2 , 0
         1414.65    1527
Permanent Ineff=
       F       F
#Block Obstruct= 2 ,-1
 1600.87 1652.53 1535.64 2049.19 2086.29  1544.8
Bank Sta=1726.7,2002.3
XS Rating Curve= 0 ,0
Exp/Cntr=0.3,0.1

Type RM Length L Ch R = 1 ,119692  ,1014.8,877.4,447.6
BEGIN DESCRIPTION:
Channel burn based on effective XS DN
END DESCRIPTION:
XS GIS Cut Line= 3
2057890.84137202246280.5731212552056517.06010555247242.622375727
2056187.19888864247806.858451977
#Sta/Elev= 30
       0  1597.9    79.4 1585.13   184.7 1579.54   312.3 1548.08   362.1 1528.46
   443.9 1517.39   484.6 1505.28   555.2    1505   656.5 1519.38   949.7 1515.39
   977.7 1523.45  1031.1 1522.66  1044.4 1516.21  1097.9 1516.64  1145.9 1500.11
  1149.9  1494.9  1429.2  1494.9  1433.3 1500.21  1434.3 1500.87  1474.4 1513.65
    1554 1519.38  1997.8 1514.16  2028.2 1521.29  2060.3 1522.19  2081.8 1543.47
  2117.8 1566.55  2132.2 1586.04  2198.6 1621.05  2248.6 1633.28  2330.7 1628.76
#Mann= 8 ,-1 , 0
       0     .08       0   977.7    .016       0  1031.1     .08       0
  1145.9    .045       0  1433.3     .04       0  1434.3     .04       0
  2028.2    .016       0  2060.3      .1       0
#XS Ineff= 2 , 0
          998.59 1526.63
Permanent Ineff=
       F       F
#Block Obstruct= 4 ,-1
 1511.94 1545.48 1538.65 1629.73 1663.68 1539.35  1686.9 1715.26 1538.72
 1983.82 2011.07 1534.96
Bank Sta=1145.9,1433.3
XS Rating Curve= 0 ,0
Exp/Cntr=0.3,0.1

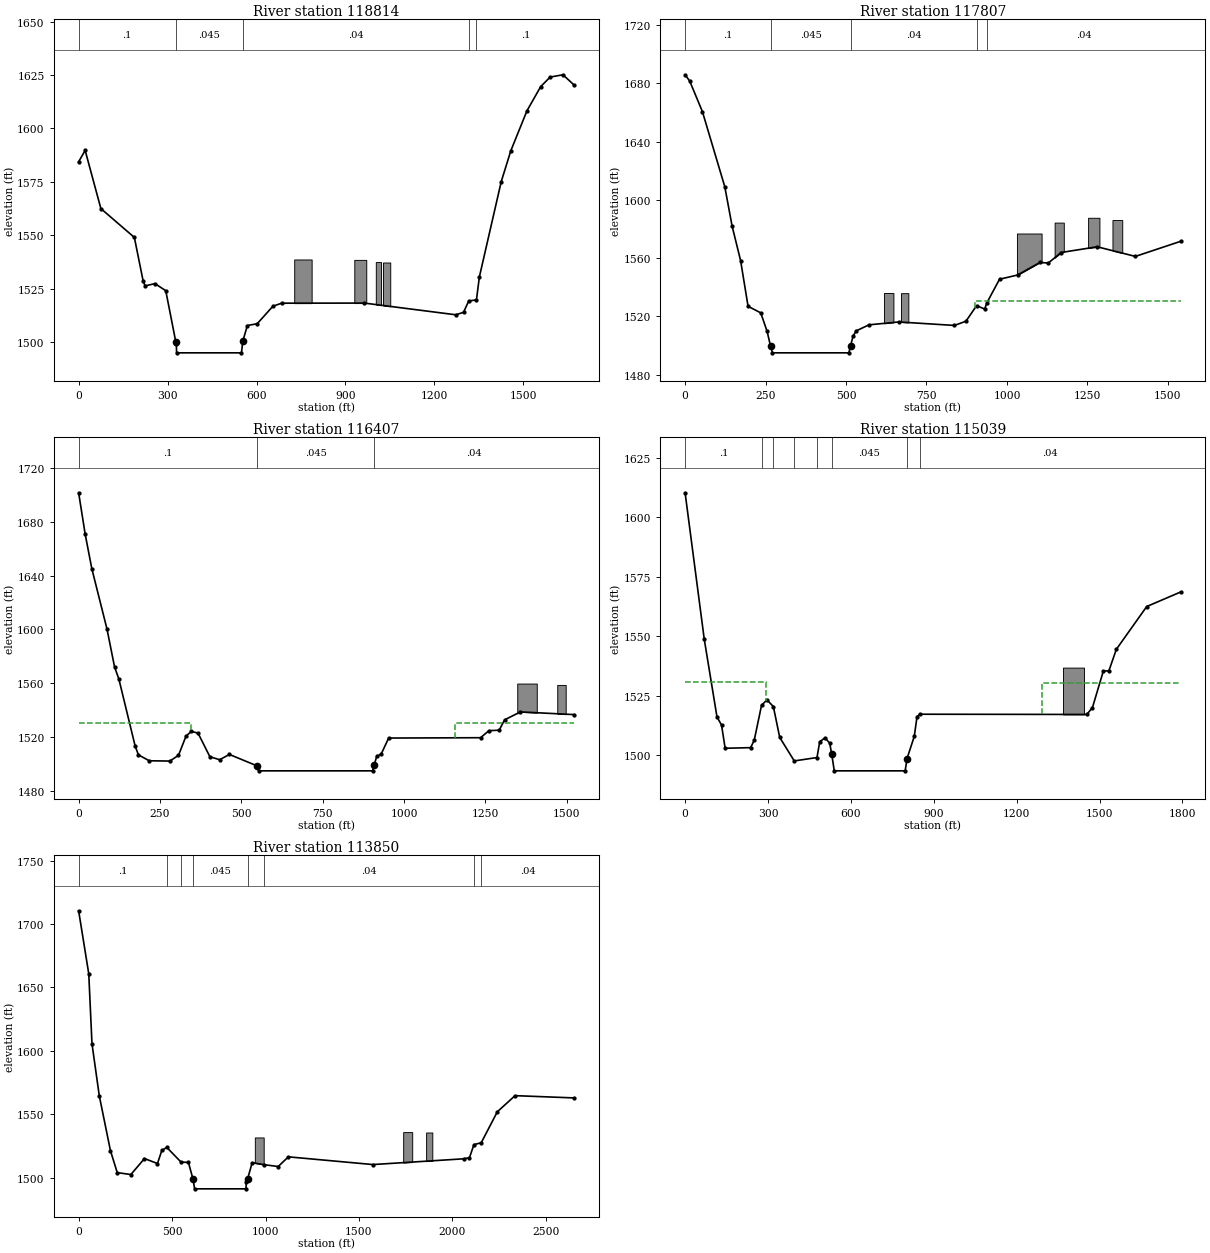
Type RM Length L Ch R = 1 ,118814  ,1042,1007.9,895.3
BEGIN DESCRIPTION:
Channel burn based on effective XS DM
END DESCRIPTION:
XS GIS Cut Line= 2
2056221.92126013246096.7890374812055978.86564389247750.434680313
#Sta/Elev= 30
       0 1584.36      22 1589.69      75 1562.45     188 1548.94   217.6 1528.52
   224.2 1526.26   257.5 1527.31   293.9    1524  327.731500.023   329.7 1498.97
   330.4  1494.9   549.2  1494.9  553.861500.434   569.1  1507.7   602.3 1508.52
   655.3 1516.74     685 1518.15   963.7  1518.2    1272 1512.72  1298.2 1513.87
  1315.6 1519.16  1341.8 1519.72  1351.7 1530.48  1425.4 1575.08  1457.8 1589.56
  1512.2 1608.25  1558.4 1619.55  1590.2 1624.02  1633.6  1625.1  1671.4 1620.26
#Mann= 5 ,-1 , 0
       0      .1       0  327.73    .045       0  553.86     .04       0
  1315.6    .016       0  1341.8      .1       0
#Block Obstruct= 4 ,-1
  727.13  785.92 1538.62  929.78  970.16 1538.43 1002.28 1020.03  1537.4
 1026.55 1051.09  1537.2
Bank Sta=327.73,553.86
XS Rating Curve= 0 ,0
Exp/Cntr=0.3,0.1

Type RM Length L Ch R = 1 ,117807  ,1405.5,1399.1,1377.5
BEGIN DESCRIPTION:
Channel burn based on linear interpolation between effective XS DL and DM
END DESCRIPTION:
Node Name=AI
XS GIS Cut Line= 2
2055119.49072222246248.6985105572055271.40052339  247780.8168374
#Sta/Elev= 30
       0 1685.86    14.2 1681.61    53.8 1660.57   123.4 1608.96   146.1 1581.95
   172.5  1558.3   195.6 1526.98   235.1 1522.46   254.9 1509.68  265.341499.782
   271.4 1495.03   508.8 1495.03   514.31500.033     522 1506.59   531.9 1510.14
   571.4 1514.26   663.7 1516.23   836.7 1513.84   872.6 1516.73   905.6 1527.39
   930.8 1525.11   937.4  1529.3   976.9 1545.54    1033 1548.45  1102.2 1557.04
  1128.6 1556.68  1168.2 1563.89  1280.3 1567.82    1399 1561.21  1539.6 1571.56
#Mann= 5 ,-1 , 0
       0      .1       0  265.34    .045       0   514.3     .04       0
   905.6    .016       0   937.4     .04       0
#XS Ineff= 2 , 0
                          901.41          1530.4
Permanent Ineff=
       F       F
#Block Obstruct= 6 ,-1
   617.8  647.24 1536.08  670.68  693.64 1535.98 1030.96 1107.63 1576.93
 1148.12 1176.58 1584.42 1252.07  1287.3 1587.72 1327.79 1358.18 1586.17
Bank Sta=265.34,514.3
XS Rating Curve= 0 ,0
Exp/Cntr=0.3,0.1

Type RM Length L Ch R = 1 ,116407  ,1334.6,1368.7,1410
BEGIN DESCRIPTION:
Channel burn based on effective XS DL
END DESCRIPTION:
XS GIS Cut Line= 4
2053687.19896738246318.1429254712053927.04375178247700.735550904
2053942.77703411247795.1352449162053952.21700352247817.161840185
#Sta/Elev= 30
       0 1701.33    20.1 1670.67    40.5  1645.1    87.1 1600.37   110.4 1572.25
   123.7 1563.22   173.7 1513.56   183.7 1507.04     217 1502.66   280.2 1502.45
   306.9 1506.69   330.1    1521   346.8 1524.49     367 1523.13   403.4 1505.65
   433.4 1503.45   463.4 1507.35  547.821498.939   553.3  1495.2   903.3  1495.2
  908.661499.634   916.2 1506.16   929.5 1507.49   952.8 1519.51  1235.3 1519.76
  1260.9 1524.96  1292.5 1525.34    1309 1532.98  1357.6 1538.89  1522.9 1536.88
#Mann= 3 ,-1 , 0
       0      .1       0  547.82    .045       0  908.66     .04       0
#XS Ineff= 2 , 0
          344.79 1530.65    1158         1530.65
Permanent Ineff=
       F       F
#Block Obstruct= 2 ,-1
 1347.96 1407.93 1559.91 1470.89 1496.86 1558.89
Bank Sta=547.82,908.66
XS Rating Curve= 0 ,0
Exp/Cntr=0.3,0.1

Type RM Length L Ch R = 1 ,115039  ,1200.3,1188.4,1157.2
BEGIN DESCRIPTION:
Channel burn based on effective XS DK
END DESCRIPTION:
Node Name=AH
XS GIS Cut Line= 2
2052411.15722814246561.1985417312052550.04605797248349.393128067
#Sta/Elev= 30
       0 1610.33    69.3 1548.73   115.4 1515.99   131.9 1512.56     145  1502.8
   237.2 1503.06   250.3  1506.2   276.7 1520.91   296.4 1523.16   319.4 1520.36
   342.5 1507.36   395.1 1497.47   477.4  1498.9   487.3 1505.57     507 1507.21
   523.5 1504.87  530.73 1500.33   539.9  1493.3   796.6  1493.3  803.341498.491
   829.5  1507.8   839.4 1516.05   849.2 1517.13    1454 1517.03  1474.5 1519.95
    1514 1535.38  1533.7 1535.32  1560.9 1544.45  1670.8 1562.45  1793.6 1568.57
#Mann= 8 ,-1 , 0
       0      .1       0   276.7    .016       0   319.4      .1       0
   395.1    .045       0   477.4     .08       0  530.73    .045       0
  803.34     .08       0   849.2     .04       0
#XS Ineff= 2 , 0
          291.83 1530.65 1291.27         1530.48
Permanent Ineff=
       F       F
#Block Obstruct= 1 ,-1
  1367.7 1443.73 1536.75
Bank Sta=530.73,803.34
XS Rating Curve= 0 ,0
Exp/Cntr=0.3,0.1

Type RM Length L Ch R = 1 ,113850  ,1234.9,1222.1,1128
BEGIN DESCRIPTION:
Channel burn based on effective XS DJ
END DESCRIPTION:
XS GIS Cut Line= 3
2051177.33106513246563.5142727512051512.58010728248970.921680157
2051554.08713154249188.035345547
#Sta/Elev= 30
       0 1710.38    54.2 1660.68    71.4  1605.6   110.5 1564.47   170.2 1521.25
   206.6 1503.89   279.5 1502.38   352.3 1514.97   421.9 1511.07   445.1 1521.35
   471.6 1523.78   547.8 1512.24   587.5 1511.91   612.51498.524   620.6  1491.1
   895.6  1491.1   897.1 1496.78   904.3 1499.01   928.7 1511.75   993.1 1510.15
  1067.8 1508.69  1122.3 1516.33  1574.6 1510.25  2060.2 1514.78  2091.4 1515.68
  2115.4 1525.96  2154.3 1527.44  2240.4 1551.87  2335.4 1564.59  2651.7  1562.8
#Mann= 8 ,-1 , 0
       0      .1       0   471.6    .016       0   547.8     .08       0
   612.5    .045       0   904.3     .08       0   993.1     .04       0
  2115.4    .016       0  2154.3     .04       0
#Block Obstruct= 3 ,-1
  942.83  990.28 1531.63 1736.68 1785.08 1535.84 1859.39 1892.55 1535.53
Bank Sta=612.5,904.3
XS Rating Curve= 0 ,0
Exp/Cntr(USF)=0,0
Exp/Cntr=0.3,0.1