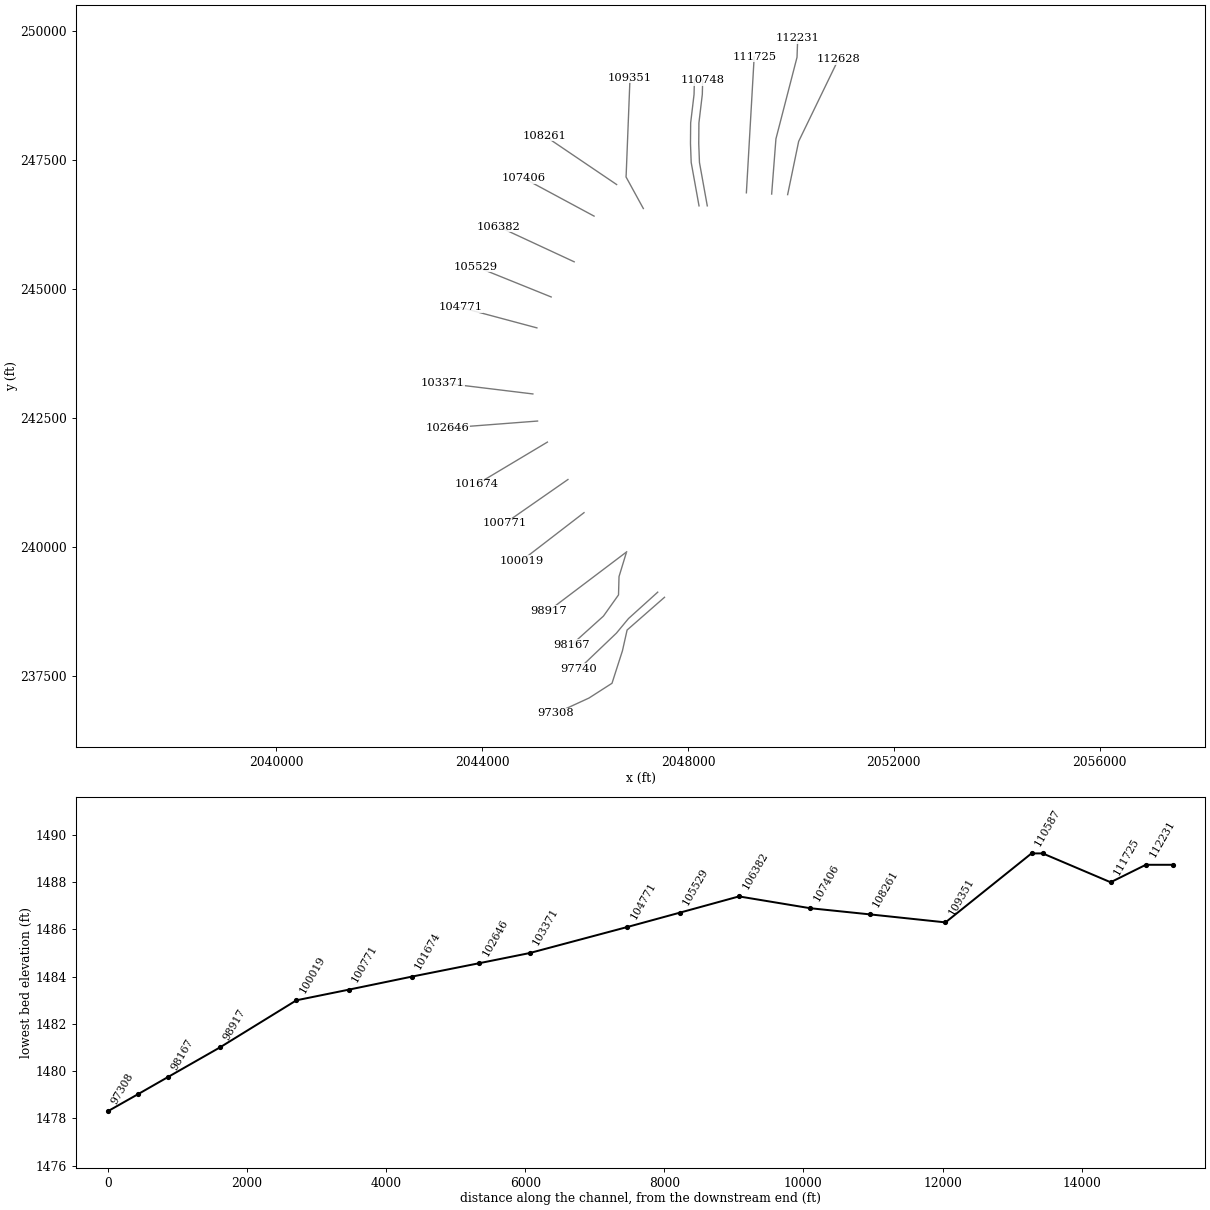
HEC-RAS study GREENBRRV.prj: GREENBRRV

--- GREENBRRV.g01 (geometry) --- (continued)

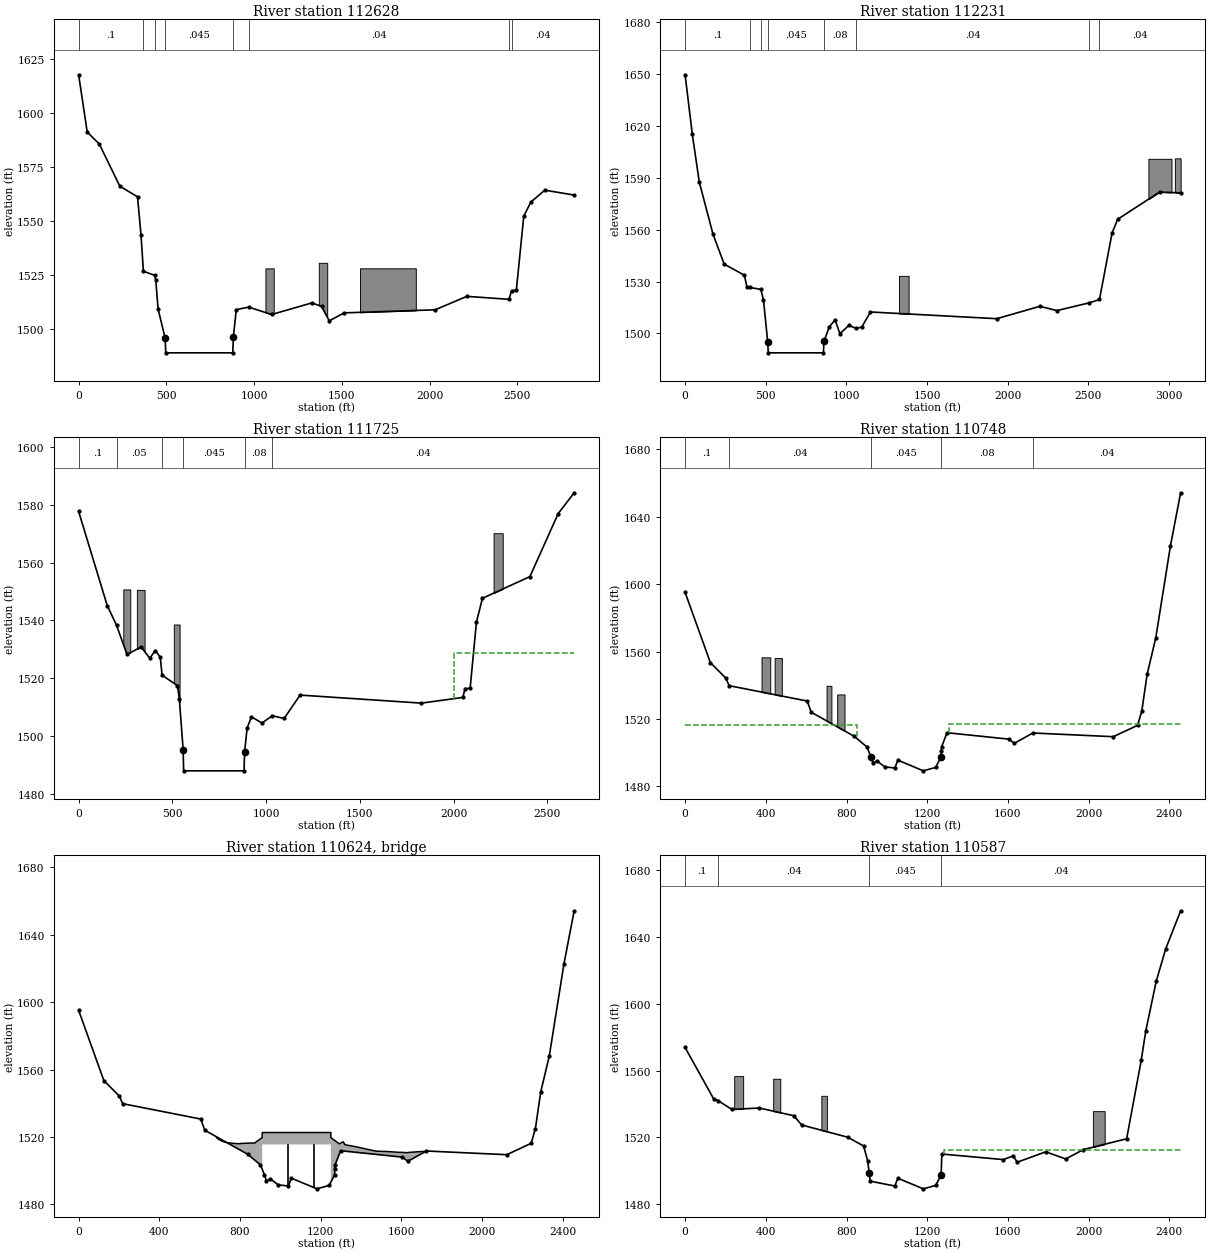
Type RM Length L Ch R = 1 ,112628  ,371,397,492.6
BEGIN DESCRIPTION:
Channel burn based on linear interpolation between effective XS DI and DJ
END DESCRIPTION:
XS GIS Cut Line= 3
2049936.19828122246829.962732766 2050150.3200811247861.640495808
2050923.78468349249454.136336267
#Sta/Elev= 30
       0 1617.53    48.9    1591   117.8 1585.45   234.8 1565.93   335.6 1561.01
   355.7 1543.19   369.1 1526.52   432.8 1524.66   439.5 1522.63   452.9    1509
   493.1 1495.52   496.4 1488.74   878.4 1488.74   881.8 1496.14   898.5 1508.74
   968.9 1509.92  1100.1  1506.5  1329.7 1511.87  1384.5 1510.24  1428.2 1503.57
  1513.4 1507.25  2031.5 1508.67  2212.4  1514.9  2452.8 1513.53  2467.1 1517.46
  2494.5 1517.78    2537 1552.07  2577.1 1558.56  2656.5 1564.08  2824.1 1561.82
#Mann= 8 ,-1 , 0
       0      .1       0   369.1    .016       0   432.8     .08       0
   493.1    .045       0   881.8     .08       0   968.9     .04       0
  2452.8    .016       0  2467.1     .04       0
#Block Obstruct= 3 ,-1
 1064.56 1111.73 1527.87 1368.75 1416.72 1530.44 1603.62 1921.64 1527.89
Bank Sta=493.1,881.8
XS Rating Curve= 0 ,0
Exp/Cntr(USF)=0,0
Exp/Cntr=0.3,0.1

Type RM Length L Ch R = 1 ,112231  ,502.3,506.3,551.7
BEGIN DESCRIPTION:
Channel burn based on linear interpolation between effective XS DI and DJ
END DESCRIPTION:
XS GIS Cut Line= 4
 2049625.6069272246841.2920505292049708.62097574247910.896137374
2050118.49820119249491.4788150212050131.84910528249858.628677635
#Sta/Elev= 30
       0 1649.64    44.8 1615.19    87.9 1587.57   173.4 1557.29   242.5 1540.08
   367.6 1533.65     384  1526.6   400.5 1526.55   469.6 1525.49     486 1519.34
   512.4 1495.01   515.6 1488.74   857.9 1488.74   861.2 1495.39   894.1 1503.78
   930.3 1507.84   959.9 1499.81  1015.8 1504.64  1061.9 1502.84  1095.5 1503.66
  1149.7 1512.38  1932.8  1508.5  2200.4 1515.68  2305.5 1513.17  2506.1 1517.67
  2569.8 1519.61  2647.8 1558.03  2682.8 1566.05  2942.7  1581.8  3073.1  1581.3
#Mann= 8 ,-1 , 0
       0      .1       0   400.5    .016       0   469.6     .08       0
   512.4    .045       0   861.2     .08       0  1061.9     .04       0
  2506.1    .016       0  2569.8     .04       0
#Block Obstruct= 3 ,-1
 1326.64 1386.14 1533.29 2873.19 3016.47 1601.02 3037.23 3073.08  1601.3
Bank Sta=512.4,861.2
XS Rating Curve= 0 ,0
Exp/Cntr(USF)=0,0
Exp/Cntr=0.3,0.1

Type RM Length L Ch R = 1 ,111725  ,937.2,976.5,995.8
BEGIN DESCRIPTION:
Channel burn based on effective XS DI
END DESCRIPTION:
Node Name=AG
XS GIS Cut Line= 2
2049134.24744339246865.0181440562049286.15724455249503.906895146
#Sta/Elev= 30
       0 1577.66   152.7 1545.11     202 1538.37   257.9 1528.24   333.7 1530.83
   379.5 1526.91     409 1529.59   435.3  1527.3   445.2 1521.08   527.3 1517.43
   537.2 1512.82  557.511495.296   560.2    1488   882.3    1488  885.461494.625
   898.7 1502.79   921.7 1506.65   978.3 1504.53  1033.4 1507.06  1095.9  1506.1
  1181.3 1514.19  1828.7 1511.41  2048.9 1513.37    2062 1516.46  2088.3 1516.49
    2122 1539.44    2154 1547.65  2407.1 1555.15  2558.2 1576.95  2643.3 1584.13
#Mann= 6 ,-1 , 0
       0      .1       0     202     .05       0   445.2     .08       0
  557.51    .045       0  885.46     .08       0  1033.4     .04       0
#XS Ineff= 2 , 0
                            2000         1528.69
Permanent Ineff=
       F       F
#Block Obstruct= 4 ,-1
  238.35  275.54 1550.72  310.68  351.86 1550.56  507.73  538.55 1538.59
 2213.38 2262.17 1570.15
Bank Sta=557.51,885.46
XS Rating Curve= 0 ,0
Exp/Cntr=0.5,0.3

Type RM Length L Ch R = 1 ,110748  ,162.8,160.9,160.6
BEGIN DESCRIPTION:
Channel burned from 54089GRB072BU
END DESCRIPTION:
XS GIS Cut Line= 6
2048374.38183714 246612.337218972048222.41396523247452.904107392
2048208.52521347247820.9598017332048211.99731939248220.265433565
2048277.96962839248772.348646984 2048284.9141683249050.126634732
#Sta/Elev= 30
       0  1595.2     125  1553.5   201.7  1544.3   218.4 1539.78   605.3 1530.66
   625.3 1524.01   838.5 1509.71   901.1 1503.42   920.8 1497.62   930.6 1493.88
  950.721495.088  989.961491.571 1039.461490.917 1054.561495.564 1180.951489.222
  1242.21491.282 1269.131497.628 1269.591500.995  1271.9 1503.65  1298.3 1511.85
  1603.4 1508.06  1632.2 1505.58  1723.7 1511.69  2122.2 1509.49  2242.9 1516.25
    2264 1525.02    2290 1546.54  2332.9 1568.17  2405.6 1622.86  2456.1 1654.29
#Mann= 5 ,-1 , 0
       0      .1       0   218.4     .04       0   920.8    .045       0
 1269.13     .08       0  1723.7     .04       0
#XS Ineff= 2 , 0
             850 1516.34    1310         1517.09
Permanent Ineff=
       F       F
#Block Obstruct= 4 ,-1
  378.73   422.1  1556.6  443.75  479.44 1556.18  701.06  725.19 1539.71
  753.76  790.27 1534.58
Bank Sta=920.8,1269.13
XS Rating Curve= 0 ,0
Exp/Cntr=0.5,0.3

Type RM Length L Ch R = 3 ,110624  ,,,
BEGIN DESCRIPTION:
Lowell Road
Bridge Structure: GRB070RP
Assumed railing height of 2.7 ft
END DESCRIPTION:
Bridge Culvert--1,0,-1,-1, 0
Deck Dist Width WeirC Skew NumUp NumDn MinLoCord MaxHiCord MaxSubmerge Is_Ogee
55,20,2.6,0, 195, 195, , , 0.98, 0, 0,0,,
  683.22  686.49  689.76  693.03   696.3  699.57  702.84   706.1  709.37  712.64
  715.91  719.18  722.45  725.72  728.99  732.26  735.53  738.79  742.06  745.33
   748.6   751.8     755   758.2   761.4   764.6   767.8     771   774.2   777.4
   780.6   783.8     787   790.2   793.4   796.6   799.8     803   806.2   809.4
   812.6   815.8     819   822.2   825.4   828.6   831.8     835   838.2   841.4
   844.6  847.81  851.01  854.21  857.46  860.72  863.98  867.24   870.5  873.76
     877     910     910    1106    1250    1250    1292    1311 1320.72 1323.99
 1327.26 1330.53 1333.81 1337.08 1340.35 1343.63  1346.9 1350.17 1353.45 1356.72
 1359.99 1363.27 1366.54 1369.81 1373.08 1376.36 1379.63  1382.9 1386.18 1389.45
 1392.72    1396 1399.27 1402.54 1405.82 1409.09 1412.36 1415.64 1418.91 1422.18
 1425.45 1428.73    1432 1435.27 1438.55 1441.82 1445.09 1448.37 1451.64 1454.91
 1458.19 1461.46 1464.73 1468.01 1471.28 1474.55 1477.82  1481.1 1484.37 1487.64
 1490.92 1494.19 1497.46 1500.74 1504.01 1507.28 1510.56 1513.83  1517.1 1520.38
 1523.65 1526.92 1530.19 1533.47 1536.74 1540.01 1543.29 1546.56 1549.83 1553.11
 1556.38 1559.65 1562.93  1566.2 1569.47 1572.74 1576.02 1579.29 1582.56 1585.84
 1589.11 1592.38 1595.66 1598.93  1602.2 1605.48 1608.75 1612.02  1615.3 1618.57
 1621.84 1625.11 1628.38 1631.65 1634.91 1638.18 1641.45 1644.72 1647.99 1651.25
 1654.52 1657.79 1661.06 1664.33 1667.59 1670.86 1674.13  1677.4 1680.67 1683.94
  1687.2 1690.47 1693.74 1697.01 1700.28 1703.54 1706.81 1710.08 1713.35 1716.62
 1719.88 1723.15 1726.42 1729.69 1732.96
 1519.65  1519.3 1518.98  1518.7 1518.44  1518.2    1518  1517.8 1517.62 1517.45
 1517.28 1517.15 1517.05 1516.96 1516.87 1516.76 1516.67 1516.62 1516.56  1516.5
 1516.44 1516.39 1516.34  1516.3 1516.29 1516.25 1516.19 1516.17 1516.18 1516.13
 1516.07 1516.05 1516.04 1516.03 1516.03 1516.05 1516.09  1516.1 1516.13 1516.18
 1516.21 1516.22 1516.23 1516.26 1516.28 1516.28 1516.28 1516.28 1516.28 1516.27
 1516.26 1516.29 1516.36 1516.45 1516.46 1516.42 1516.41 1516.41 1516.41 1516.42
1516.837 1519.67 1522.67 1522.67 1522.67 1519.671515.9381517.154 1515.39 1515.32
 1515.24 1515.17  1515.1 1515.04 1514.98 1514.92 1514.86 1514.78 1514.71 1514.63
 1514.56 1514.49  1514.4 1514.32 1514.25 1514.17 1514.09 1513.98 1513.92 1513.85
 1513.76 1513.64 1513.54 1513.47 1513.38 1513.28 1513.19 1513.09 1512.99 1512.91
 1512.82 1512.73 1512.62 1512.53 1512.43 1512.35 1512.26 1512.16 1512.08 1511.99
 1511.94  1511.9 1511.82 1511.76 1511.71 1511.64  1511.6 1511.56 1511.53 1511.53
 1511.51 1511.48 1511.45 1511.43 1511.44 1511.44 1511.42 1511.42 1511.43 1511.41
  1511.4 1511.37 1511.34  1511.3 1511.28 1511.28 1511.23 1511.23 1511.24 1511.19
 1511.16 1511.15 1511.14 1511.12 1511.09 1511.04 1511.01 1510.98 1510.93 1510.89
 1510.89 1510.91  1510.9 1510.89 1510.89 1510.88 1510.83 1510.76 1510.75 1510.72
 1510.65 1510.64 1510.69 1510.76 1510.84 1510.88 1510.88  1510.9 1510.93 1510.95
 1510.98    1511 1511.03 1511.08 1511.12 1511.15 1511.18 1511.19 1511.22 1511.27
 1511.28 1511.29 1511.31 1511.34 1511.37 1511.39 1511.39  1511.4 1511.41 1511.43
 1511.48 1511.49 1511.51 1511.52 1511.54
                                                                                
                                                                                
                                                                                
                                                                                
                                                                                
                                                                                
                 1515.57 1515.57 1515.57
                                                                                
                                                                                
                                                                                
                                                                                
                                                                                
                                                                                
                                                                                
                                                                                
                                                                                
                                                                                
                                                                                
                                                                                
                                        
  683.22  686.49  689.76  693.03   696.3  699.57  702.84   706.1  709.37  712.64
  715.91  719.18  722.45  725.72  728.99  732.26  735.53  738.79  742.06  745.33
   748.6   751.8     755   758.2   761.4   764.6   767.8     771   774.2   777.4
   780.6   783.8     787   790.2   793.4   796.6   799.8     803   806.2   809.4
   812.6   815.8     819   822.2   825.4   828.6   831.8     835   838.2   841.4
   844.6  847.81  851.01  854.21  857.46  860.72  863.98  867.24   870.5  873.76
     877     910     910    1106    1250    1250    1292    1311 1320.72 1323.99
 1327.26 1330.53 1333.81 1337.08 1340.35 1343.63  1346.9 1350.17 1353.45 1356.72
 1359.99 1363.27 1366.54 1369.81 1373.08 1376.36 1379.63  1382.9 1386.18 1389.45
 1392.72    1396 1399.27 1402.54 1405.82 1409.09 1412.36 1415.64 1418.91 1422.18
 1425.45 1428.73    1432 1435.27 1438.55 1441.82 1445.09 1448.37 1451.64 1454.91
 1458.19 1461.46 1464.73 1468.01 1471.28 1474.55 1477.82  1481.1 1484.37 1487.64
 1490.92 1494.19 1497.46 1500.74 1504.01 1507.28 1510.56 1513.83  1517.1 1520.38
 1523.65 1526.92 1530.19 1533.47 1536.74 1540.01 1543.29 1546.56 1549.83 1553.11
 1556.38 1559.65 1562.93  1566.2 1569.47 1572.74 1576.02 1579.29 1582.56 1585.84
 1589.11 1592.38 1595.66 1598.93  1602.2 1605.48 1608.75 1612.02  1615.3 1618.57
 1621.84 1625.11 1628.38 1631.65 1634.91 1638.18 1641.45 1644.72 1647.99 1651.25
 1654.52 1657.79 1661.06 1664.33 1667.59 1670.86 1674.13  1677.4 1680.67 1683.94
  1687.2 1690.47 1693.74 1697.01 1700.28 1703.54 1706.81 1710.08 1713.35 1716.62
 1719.88 1723.15 1726.42 1729.69 1732.96
 1519.65  1519.3 1518.98  1518.7 1518.44  1518.2    1518  1517.8 1517.62 1517.45
 1517.28 1517.15 1517.05 1516.96 1516.87 1516.76 1516.67 1516.62 1516.56  1516.5
 1516.44 1516.39 1516.34  1516.3 1516.29 1516.25 1516.19 1516.17 1516.18 1516.13
 1516.07 1516.05 1516.04 1516.03 1516.03 1516.05 1516.09  1516.1 1516.13 1516.18
 1516.21 1516.22 1516.23 1516.26 1516.28 1516.28 1516.28 1516.28 1516.28 1516.27
 1516.26 1516.29 1516.36 1516.45 1516.46 1516.42 1516.41 1516.41 1516.41 1516.42
1516.837 1519.67 1522.67 1522.67 1522.67 1519.671515.9381517.154 1515.39 1515.32
 1515.24 1515.17  1515.1 1515.04 1514.98 1514.92 1514.86 1514.78 1514.71 1514.63
 1514.56 1514.49  1514.4 1514.32 1514.25 1514.17 1514.09 1513.98 1513.92 1513.85
 1513.76 1513.64 1513.54 1513.47 1513.38 1513.28 1513.19 1513.09 1512.99 1512.91
 1512.82 1512.73 1512.62 1512.53 1512.43 1512.35 1512.26 1512.16 1512.08 1511.99
 1511.94  1511.9 1511.82 1511.76 1511.71 1511.64  1511.6 1511.56 1511.53 1511.53
 1511.51 1511.48 1511.45 1511.43 1511.44 1511.44 1511.42 1511.42 1511.43 1511.41
  1511.4 1511.37 1511.34  1511.3 1511.28 1511.28 1511.23 1511.23 1511.24 1511.19
 1511.16 1511.15 1511.14 1511.12 1511.09 1511.04 1511.01 1510.98 1510.93 1510.89
 1510.89 1510.91  1510.9 1510.89 1510.89 1510.88 1510.83 1510.76 1510.75 1510.72
 1510.65 1510.64 1510.69 1510.76 1510.84 1510.88 1510.88  1510.9 1510.93 1510.95
 1510.98    1511 1511.03 1511.08 1511.12 1511.15 1511.18 1511.19 1511.22 1511.27
 1511.28 1511.29 1511.31 1511.34 1511.37 1511.39 1511.39  1511.4 1511.41 1511.43
 1511.48 1511.49 1511.51 1511.52 1511.54
                                                                                
                                                                                
                                                                                
                                                                                
                                                                                
                                                                                
                 1515.57 1515.57 1515.57
                                                                                
                                                                                
                                                                                
                                                                                
                                                                                
                                                                                
                                                                                
                                                                                
                                                                                
                                                                                
                                                                                
                                                                                
                                        
Pier Skew, UpSta & Num, DnSta & Num=  ,1034, 2 ,1034, 2 , 0 , 0 , 0 ,,
       3       3
       0    1520
       3       3
       0    1520
Pier Skew, UpSta & Num, DnSta & Num=  ,1164, 2 ,1164, 2 , 0 , 0 , 0 ,,
       3       3
       0    1520
       3       3
       0    1520
BR Coef=-1 , 1 , 0 ,0.95, 0 ,,,0.8,0,1.33,0,
WSPro=,,,, 1 ,,,, 0 ,,,, 0 ,,,,-1 ,-1 ,-1 , 0 , 0 , 0 , 0 , 0
BR U #Sta/Elev= 30
       0  1595.2     125  1553.5   201.7  1544.3   218.4 1539.78   605.3 1530.66
   625.3 1524.01   838.5 1509.71   901.1 1503.42   920.8 1497.62   930.6 1493.88
  950.721495.088  989.961491.571 1039.461490.917 1054.561495.564 1180.951489.222
  1242.21491.282 1269.131497.628 1269.591500.995  1271.9 1503.65  1298.3 1511.85
  1603.4 1508.06  1632.2 1505.58  1723.7 1511.69  2122.2 1509.49  2242.9 1516.25
    2264 1525.02    2290 1546.54  2332.9 1568.17  2405.6 1622.86  2456.1 1654.29
BR U #Mann= 5
       0      .1   218.4     .04   920.8     .04 1269.13     .08  1723.7     .04
BR D #Sta/Elev= 30
       0 1573.92   141.7 1543.08     165 1541.95   231.7 1536.84   368.5 1537.64
   538.6 1533.03   578.1 1527.48   805.2 1520.19   884.7  1514.9   904.4 1506.18
   912.7 1498.66   917.5 1493.81 1039.461490.917 1054.561495.564 1180.951489.222
  1242.21491.282 1269.131497.628  1272.4 1510.09  1576.9 1506.75  1626.4 1508.94
  1646.2 1505.17  1787.7 1511.41  1886.4 1507.12  1974.5 1512.78  2188.5 1519.22
  2260.7 1566.19  2283.6 1584.04    2335 1613.59  2382.1 1633.03  2456.1 1655.85
BR D #Mann= 4
       0      .1     165     .04   912.7     .04 1269.13     .04
BC Design=,, 0 ,, 0 ,,,,,,
BC Use User HTab Curves=0
BC User HTab FreeFlow(D)= 0

Type RM Length L Ch R = 1 ,110587  ,1259.5,1236.7,1217
BEGIN DESCRIPTION:
Channel burned from 54089GRB072BU
END DESCRIPTION:
XS GIS Cut Line= 6
2048213.79160714 246612.337218972048061.82373522247452.904107392
2048047.93498348247820.9598017332048051.40708938248220.265433565
2048117.37939839248772.3486469842048124.32393831249050.126634732
#Sta/Elev= 30
       0 1573.92   141.7 1543.08     165 1541.95   231.7 1536.84   368.5 1537.64
   538.6 1533.03   578.1 1527.48   805.2 1520.19   884.7  1514.9   904.4 1506.18
   912.7 1498.66   917.5 1493.81 1039.461490.917 1054.561495.564 1180.951489.222
  1242.21491.282 1269.131497.628  1272.4 1510.09  1576.9 1506.75  1626.4 1508.94
  1646.2 1505.17  1787.7 1511.41  1886.4 1507.12  1974.5 1512.78  2188.5 1519.22
  2260.7 1566.19  2283.6 1584.04    2335 1613.59  2382.1 1633.03  2456.1 1655.85
#Mann= 4 ,-1 , 0
       0      .1       0     165     .04       0   912.7    .045       0
 1269.13     .04       0
#XS Ineff= 2 , 0
             878 1512.42    1282         1512.42
Permanent Ineff=
       F       F
#Block Obstruct= 4 ,-1
  243.34  287.79 1556.78  436.54  471.75 1555.19  675.35  702.69 1544.98
 2021.19 2079.62 1535.78
Bank Sta=912.7,1269.13
XS Rating Curve= 0 ,0
Exp/Cntr=0.5,0.3

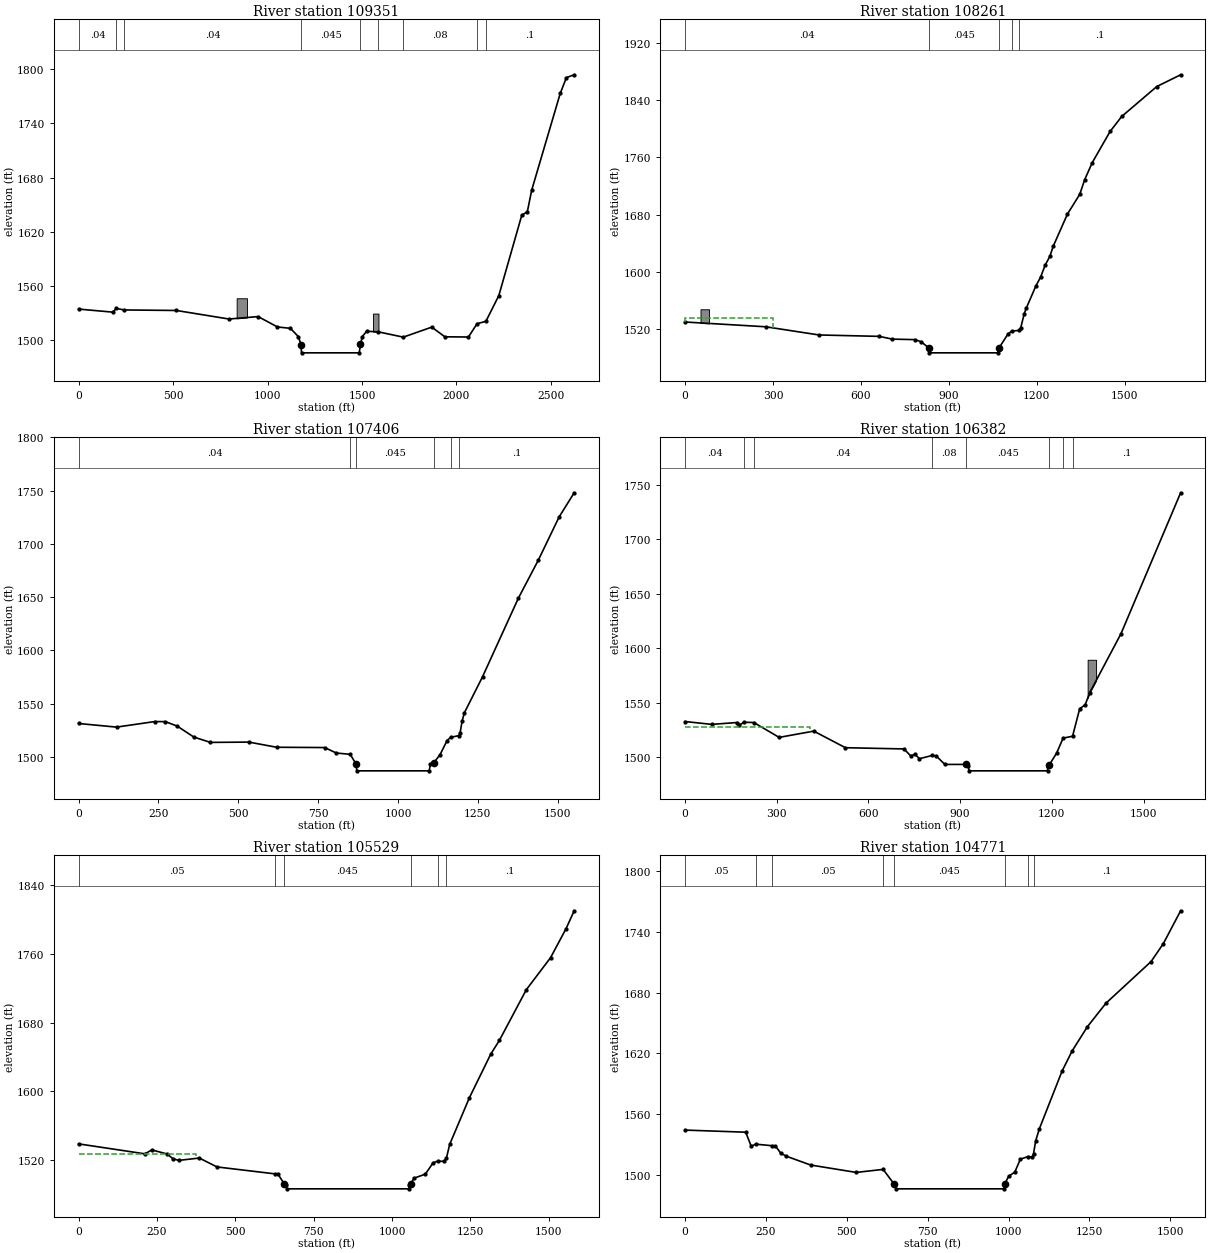
Type RM Length L Ch R = 1 ,109351  ,714.2,1089.7,1279.2
BEGIN DESCRIPTION:
Channel burn based on effective XS DF
END DESCRIPTION:
XS GIS Cut Line= 4
2047131.65723445246560.8300380142046795.29091754247172.642283893
2046798.66873632247226.6873843642046872.96292397249095.920834482
#Sta/Elev= 30
       0 1534.64   180.9 1531.27   199.1 1535.41   240.3  1533.7   517.4 1533.11
   795.8 1523.67   950.1 1526.35  1052.4 1514.91  1120.8 1513.37  1163.5 1504.16
  1176.6 1495.45  1179.9  1486.3  1485.3  1486.3  1491.9 1495.83  1501.7 1504.32
  1524.7 1510.16  1587.1 1509.46  1718.4 1503.64  1869.4 1514.71  1938.4 1504.02
  2063.4 1503.79  2109.1 1518.54  2155.7 1521.09  2224.1 1549.54  2345.5 1638.27
  2375.1 1642.26  2398.5 1666.31  2549.1 1772.91    2582 1790.45    2623 1793.54
#Mann= 9 ,-1 , 0
       0     .04       0   199.1    .016       0   240.3     .04       0
  1176.6    .045       0  1491.9     .08       0  1587.1     .04       0
  1718.4     .08       0  2109.1    .016       0  2155.7      .1       0
#Block Obstruct= 2 ,-1
  836.42   890.9 1546.61 1558.25 1587.11 1529.68
Bank Sta=1176.6,1491.9
XS Rating Curve= 0 ,0
Exp/Cntr=0.3,0.1

Type RM Length L Ch R = 1 ,108261  ,808.8,854.6,873.6
BEGIN DESCRIPTION:
Channel burn based on linear interpolation between effective XS DE and DF
END DESCRIPTION:
Node Name=AF
XS GIS Cut Line= 2
2046612.54612197247025.6083740592045210.63652422247971.788896397
#Sta/Elev= 30
       0 1529.73     275 1523.08     457 1511.62   662.9 1509.66   706.6 1505.84
   784.6 1505.09   805.4 1502.21   833.1 1493.08  833.81 1486.64  1068.1 1486.64
  1070.9 1493.12  1102.2 1513.06  1115.4 1517.09  1140.8 1517.97  1145.8 1522.04
  1157.6 1541.57    1165 1549.56  1197.2 1580.16  1213.1 1592.26  1228.8 1609.09
  1244.7 1621.33  1256.6 1635.84    1305 1680.62    1347 1708.26  1363.5  1728.4
  1389.5 1752.46  1450.5 1796.04  1490.1 1817.04  1609.9 1858.88  1691.3 1875.32
#Mann= 5 ,-1 , 0
       0     .04       0   833.1    .045       0  1070.9     .08       0
  1115.4    .016       0  1140.8      .1       0
#XS Ineff= 2 , 0
             300    1535
Permanent Ineff=
       F       F
#Block Obstruct= 1 ,-1
   52.57   81.69 1547.55
Bank Sta=833.1,1070.9
XS Rating Curve= 0 ,0
Exp/Cntr=0.3,0.1

Type RM Length L Ch R = 1 ,107406  ,1001.1,1024.9,1036.7
BEGIN DESCRIPTION:
Channel burn based on effective XS DE
END DESCRIPTION:
XS GIS Cut Line= 2
 2046174.1782323246413.6292830562044806.99067797247147.136018142
#Sta/Elev= 30
       0 1531.33   118.6 1527.94   237.7 1533.12   271.3 1533.09   308.5 1528.91
   360.8 1518.58   412.7 1513.59   532.9 1513.88   620.1 1509.03   770.3 1508.75
   806.7 1503.63   850.3 1502.39  869.251492.972   869.7 1492.85   870.7  1486.9
  1097.5  1486.9  1101.5 1492.97 1111.551494.411  1131.4 1501.95  1153.6 1515.37
  1164.8 1518.31  1190.9    1520  1194.4 1522.78  1200.9 1533.97  1207.8 1541.44
  1264.7 1575.26    1377 1649.09  1439.1 1684.55  1504.5 1725.26  1551.5 1747.87
#Mann= 6 ,-1 , 0
       0     .04       0   850.3     .08       0  869.25    .045       0
 1111.55     .08       0  1164.8    .016       0  1190.9      .1       0
Bank Sta=869.25,1111.55
XS Rating Curve= 0 ,0
Exp/Cntr=0.3,0.1

Type RM Length L Ch R = 1 ,106382  ,837.3,852.5,863.4
BEGIN DESCRIPTION:
Channel burn based on effective XS DD
END DESCRIPTION:
XS GIS Cut Line= 2
2045787.89357181 245528.212418722044316.53923105246209.636252731
#Sta/Elev= 30
       0  1532.7    87.2 1530.09   170.4  1531.8   177.6 1529.46   192.9 1532.03
     225  1531.8   307.7 1518.14     421 1523.89   524.7 1508.65   716.3 1507.52
     738 1501.17   752.5 1502.56   766.9 1498.54   808.2 1501.51   821.2 1501.14
   850.1 1493.28  920.481493.294     926 1491.79   929.3  1487.4  1186.1  1487.4
  1186.3 1491.75 1192.371493.154  1215.3  1503.5    1237 1517.47  1267.8 1519.19
  1291.2 1544.45  1309.3 1548.13  1323.7 1559.07    1426 1613.21  1621.5 1742.88
#Mann= 8 ,-1 , 0
       0     .04       0   192.9    .016       0     225     .04       0
   808.2     .08       0  920.48    .045       0 1192.37     .08       0
    1237    .016       0  1267.8      .1       0
#XS Ineff= 2 , 0
          408.68 1527.64
Permanent Ineff=
       F       F
#Block Obstruct= 1 ,-1
 1317.19  1344.8 1589.45
Bank Sta=920.48,1192.37
XS Rating Curve= 0 ,0
Exp/Cntr=0.3,0.1

Type RM Length L Ch R = 1 ,105529  ,720.7,758.1,788.5
BEGIN DESCRIPTION:
Channel burn based on linear interpolation between effective XS DC and DD
END DESCRIPTION:
Node Name=AE
XS GIS Cut Line= 2
2045340.84492522244846.7889128182043873.83079889245437.066603646
#Sta/Elev= 30
       0 1539.02   211.7 1527.42   233.2 1532.02   282.4 1527.26   300.1 1522.01
     319 1519.79     385 1522.55   441.5 1512.19   625.4 1504.19     636 1503.87
  656.151492.485   660.8 1490.97   664.3 1486.71  1053.4 1486.71  1055.3 1490.91
 1059.681492.628  1070.4 1499.13  1106.4 1503.82  1131.2 1516.99  1145.3 1518.87
  1166.5 1518.72  1173.6 1522.39  1184.2 1538.56    1247 1592.77    1315  1643.4
  1342.8 1659.54  1428.5 1718.37    1506  1755.7  1555.5 1789.53  1581.3 1810.25
#Mann= 6 ,-1 , 0
       0     .05       0   625.4     .08       0  656.15    .045       0
 1059.68     .08       0  1145.3    .016       0  1173.6      .1       0
#XS Ineff= 2 , 0
          373.18 1527.39
Permanent Ineff=
       F       F
Bank Sta=656.15,1059.68
XS Rating Curve= 0 ,0
Exp/Cntr=0.3,0.1

Type RM Length L Ch R = 1 ,104771  ,1353.4,1400.2,1428.7
BEGIN DESCRIPTION:
Channel burn based on effective XS DC
END DESCRIPTION:
XS GIS Cut Line= 2
2045063.06693748244247.8304650632043583.03216788244642.795882478
#Sta/Elev= 30
       0 1544.16   187.4 1542.07   204.4 1528.18   218.1 1530.25   268.9 1528.71
   279.1 1528.52   295.8 1521.26     313 1518.34   387.7 1509.66     529 1502.32
   612.1 1505.32  646.191490.796   652.6  1486.1   985.4  1486.1  987.331490.582
  1000.4 1498.62    1019 1502.53  1036.3 1515.41  1059.7 1517.96  1073.7 1517.51
  1077.1  1520.9  1083.8 1533.64  1094.6 1545.06  1165.3 1602.47  1196.4 1622.36
  1243.4 1646.23    1301 1669.55  1440.5 1710.71  1478.4 1728.46  1531.8 1760.87
#Mann= 8 ,-1 , 0
       0     .05       0   218.1    .016       0   268.9     .05       0
   612.1     .08       0  646.19    .045       0  987.33      .1       0
  1059.7    .016       0  1077.1      .1       0
Bank Sta=646.19,987.33
XS Rating Curve= 0 ,0
Exp/Cntr=0.3,0.1

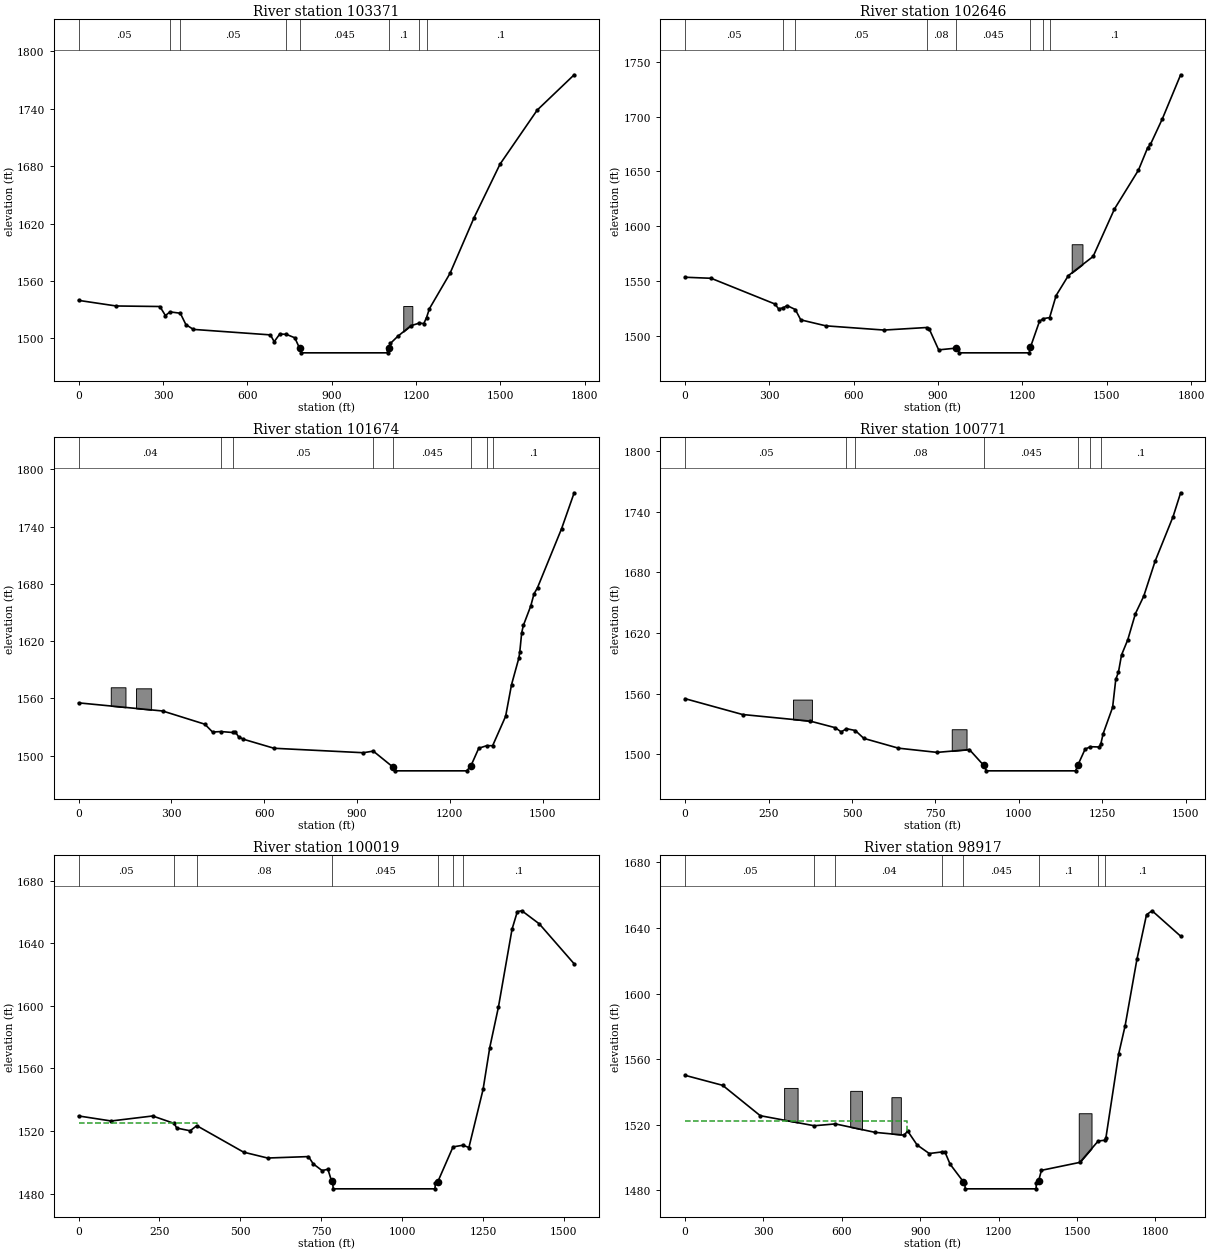
Type RM Length L Ch R = 1 ,103371  ,639.5,725,768.7
BEGIN DESCRIPTION:
Channel burn based on effective XS DB
END DESCRIPTION:
XS GIS Cut Line= 2
2044984.94209372242967.448511392 2043235.8100933243180.122298643
#Sta/Elev= 30
       0  1539.8   133.4 1533.96   288.8  1533.4   308.6 1523.99   325.1 1527.78
   361.5 1526.38   381.3 1514.55   407.8 1509.49   682.1 1503.75   695.3 1496.59
   715.1 1504.65   738.3 1504.34   768.6 1500.73  786.031489.573   791.1    1485
  1098.5    1485  1098.6 1487.82 1103.711490.517  1108.4 1494.77  1134.9  1502.3
  1181.1 1513.28  1210.6 1516.01  1227.4 1515.64  1237.1 1521.86  1247.2 1531.06
  1320.4 1567.96  1405.9 1626.13  1498.4 1682.15  1630.6 1738.61    1762 1775.49
#Mann= 8 ,-1 , 0
       0     .05       0   325.1    .016       0   361.5     .05       0
   738.3     .08       0  786.03    .045       0 1103.71      .1       0
  1210.6    .016       0  1237.1      .1       0
#Block Obstruct= 1 ,-1
 1154.26 1186.49 1533.93
Bank Sta=786.03,1103.71
XS Rating Curve= 0 ,0
Exp/Cntr=0.3,0.1

Type RM Length L Ch R = 1 ,102646  ,749,971.4,1051.8
BEGIN DESCRIPTION:
Channel burn based on linear interpolation between effective XS DA and DB
END DESCRIPTION:
Node Name=AD
XS GIS Cut Line= 2
 2045076.0879088242442.2750210612043318.27547956 242307.72640565
#Sta/Elev= 30
       0  1553.5    92.6 1552.55   319.7 1529.09   332.8 1524.61   349.3 1525.62
   362.5 1527.69   392.1 1524.07   411.5 1514.64   500.7 1509.19   707.9 1505.34
   859.3 1507.66   869.2 1505.98   902.1 1487.28   963.41488.855   971.6 1488.11
   974.5 1484.57  1224.6 1484.57 1228.831489.864  1260.7 1513.24  1273.4 1515.66
  1296.9 1516.76    1320 1536.84  1363.5 1554.99  1451.6 1572.44  1527.4 1615.64
    1613  1651.2  1645.7 1671.63  1655.6 1674.64  1698.4 1698.21    1763 1738.11
#Mann= 8 ,-1 , 0
       0     .05       0   349.3    .016       0   392.1     .05       0
   859.3     .08       0   963.4    .045       0 1228.83      .1       0
  1273.4    .016       0  1296.9      .1       0
#Block Obstruct= 1 ,-1
 1375.43 1413.67  1583.6
Bank Sta=963.4,1228.83
XS Rating Curve= 0 ,0
Exp/Cntr=0.3,0.1

Type RM Length L Ch R = 1 ,101674  ,874.4,903.1,915.7
BEGIN DESCRIPTION:
Channel burn based on effective XS DA
END DESCRIPTION:
XS GIS Cut Line= 2
 2045267.0599678242034.2889603972043891.19198464241213.976296559
#Sta/Elev= 30
       0 1555.26   271.6 1546.74     408 1532.89     433 1524.67   459.8 1525.18
     498  1524.2   505.6 1525.19   517.1 1519.71   532.3 1517.16   631.6 1507.67
   920.1 1502.99   952.5 1504.68 1015.491488.121  1021.3    1484  1254.3    1484
 1267.72 1488.97  1293.4 1507.68  1319.2 1510.37  1338.3 1510.36  1380.3 1541.18
  1399.4 1574.35  1423.1 1602.26  1426.1  1608.7  1432.2 1628.64  1437.6 1636.44
  1461.5 1656.78    1472 1669.46  1483.4 1676.07  1561.4 1738.05  1601.9 1775.52
#Mann= 8 ,-1 , 0
       0     .04       0   459.8    .016       0     498     .05       0
   952.5     .08       0 1015.49    .045       0 1267.72      .1       0
  1319.2    .016       0  1338.3      .1       0
#Block Obstruct= 2 ,-1
   103.9  151.42  1571.6  185.38  234.33 1570.51
Bank Sta=1015.49,1267.72
XS Rating Curve= 0 ,0
Exp/Cntr=0.3,0.1

Type RM Length L Ch R = 1 ,100771  ,736.9,752.1,765
BEGIN DESCRIPTION:
Channel burn based on linear interpolation between effective XS CZ and DA
END DESCRIPTION:
XS GIS Cut Line= 2
2045666.36559963241309.4626541442044446.74763206240463.108375728
#Sta/Elev= 30
       0 1554.89     172 1539.23   375.5 1532.63     450 1526.15   467.5    1522
   483.5 1525.18   509.8 1523.38   535.4 1515.58   639.2 1505.89     755 1501.72
   851.7  1504.5  894.641488.837   902.8 1483.45  1169.9 1483.45 1176.471489.046
  1198.3 1504.91  1214.3 1507.35  1240.7 1507.06  1245.4 1510.09  1252.4 1520.27
  1280.7 1546.31  1290.2 1574.03  1298.2 1581.16  1307.4 1598.14  1326.1 1613.21
  1349.1 1639.14    1374  1656.4    1408 1690.99  1461.9 1735.21  1484.5 1758.75
#Mann= 7 ,-1 , 0
       0     .05       0   483.5    .016       0   509.8     .08       0
  894.64    .045       0 1176.47      .1       0  1214.3    .016       0
  1245.4      .1       0
#Block Obstruct= 2 ,-1
  323.25  379.93 1553.99  798.78   843.1 1524.64
Bank Sta=894.64,1176.47
XS Rating Curve= 0 ,0
Exp/Cntr=0.3,0.1

Type RM Length L Ch R = 1 ,100019  ,1104,1101.9,1099.5
BEGIN DESCRIPTION:
Channel burn based on effective XS CZ
END DESCRIPTION:
XS GIS Cut Line= 2
2045978.86563081240667.1014060682044763.58787763239733.941855058
#Sta/Elev= 30
       0 1529.61   100.6  1526.4   228.8  1529.6     295 1524.87   303.5 1521.87
   344.7 1520.14   365.3  1523.4   510.1 1506.46   584.3 1502.71   710.7 1503.63
   725.2 1499.01   752.8 1494.68   770.7 1495.53  782.481487.746   785.5  1486.6
   787.3    1483  1101.6    1483  1103.3  1486.5 1109.871487.215  1157.6 1509.83
  1188.5  1510.9  1206.7 1509.42  1250.5 1546.55  1271.2 1573.37    1298 1599.25
  1340.1 1649.07  1356.5 1660.33  1370.5 1660.84  1424.4 1652.46  1532.2 1626.91
#Mann= 7 ,-1 , 0
       0     .05       0     295    .016       0   365.3     .08       0
  782.48    .045       0 1109.87      .1       0  1157.6    .016       0
  1188.5      .1       0
#XS Ineff= 2 , 0
             366    1525
Permanent Ineff=
       F       F
Bank Sta=782.48,1109.87
XS Rating Curve= 0 ,0
Exp/Cntr=0.3,0.1

Type RM Length L Ch R = 1 ,98917   ,666.3,750.1,763.7
BEGIN DESCRIPTION:
Channel burn based on effective XS CY
END DESCRIPTION:
Node Name=AC
XS GIS Cut Line= 2
2046807.85872348 239907.552728312045293.10191047238766.059604481
#Sta/Elev= 30
       0 1550.18   143.8 1544.08   287.6 1525.58   494.1 1519.45   575.1 1520.57
   727.1 1515.42   838.1 1513.74     852 1516.18     888 1507.75   934.5 1502.53
   983.7  1503.5   994.2 1503.61  1014.1 1496.09 1064.651485.413  1070.4  1484.6
  1072.2    1481  1343.4    1481  1344.5 1484.51 1352.921485.816  1363.9 1492.28
  1510.8 1497.12  1581.1 1510.14  1606.3 1510.63  1610.4 1511.79  1659.7 1563.33
  1684.3 1580.46  1729.5 1620.97  1766.1 1648.07  1787.5 1650.46  1896.7 1634.98
#Mann= 8 ,-1 , 0
       0     .05       0   494.1    .016       0   575.1     .04       0
   983.7     .08       0 1064.65    .045       0 1352.92      .1       0
  1581.1    .016       0  1606.3      .1       0
#XS Ineff= 2 , 0
           850.7 1522.06
Permanent Ineff=
       F       F
#Block Obstruct= 4 ,-1
  379.02  430.52  1542.5  631.93  676.94 1540.71  789.73  825.76 1536.86
 1506.73 1555.59 1527.07
Bank Sta=1064.65,1352.92
XS Rating Curve= 0 ,0
Exp/Cntr=0.3,0.1

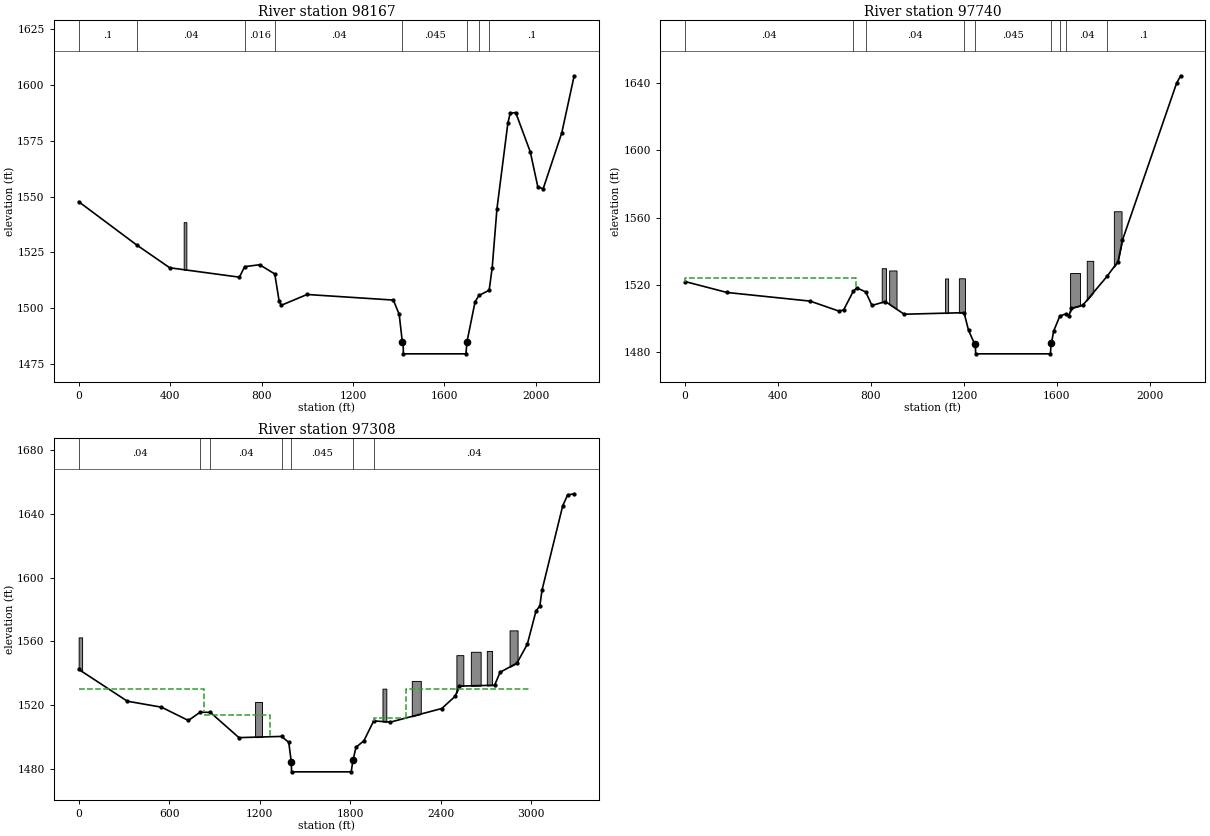
Type RM Length L Ch R = 1 ,98167   ,436.8,426.9,445.3
BEGIN DESCRIPTION:
Channel burn based on linear interpolation between effective XS CX and CY
END DESCRIPTION:
XS GIS Cut Line= 5
2046796.98784059239878.3674488922046659.13536426 239427.88524946
2046649.28875881239073.4074531872046356.35224661238662.311675563
2045734.00355963238103.206155082
#Sta/Elev= 30
       0 1547.71   253.9 1528.36   398.5 1518.17   703.1 1513.98   726.1 1518.68
   791.6 1519.53   857.8 1515.41   876.7 1503.36     886 1501.42   999.1 1506.25
  1376.3 1503.75  1401.9 1497.38  1415.6 1485.05    1419 1484.44  1420.4 1479.74
  1693.8 1479.74  1698.2 1485.05  1733.5 1502.89  1750.4  1505.8  1795.3 1508.14
  1808.5 1518.09  1829.4 1544.53  1877.1 1582.76  1887.4 1587.25  1911.5 1587.47
  1975.3 1569.89  2008.2 1554.28  2031.5 1553.46  2112.8 1578.39  2167.1 1603.92
#Mann= 8 ,-1 , 0
       0      .1       0   253.9     .04       0   726.1    .016       0
   857.8     .04       0  1415.6    .045       0  1698.2     .08       0
  1750.4    .016       0  1795.3      .1       0
#Block Obstruct= 1 ,-1
  459.43   471.1 1538.54
Bank Sta=1415.6,1698.2
XS Rating Curve= 0 ,0
Exp/Cntr(USF)=0,0
Exp/Cntr=0.3,0.1

Type RM Length L Ch R = 1 ,97740   ,181.4,431.9,666.5
BEGIN DESCRIPTION:
Channel burn based on linear interpolation between effective XS CX and CY
END DESCRIPTION:
XS GIS Cut Line= 4
2047411.15738563239126.3026503922046842.58076689238614.150131389
2046608.20590755238332.031929225 2045883.3796013237641.927666396
#Sta/Elev= 30
       0 1521.97   180.5 1515.48   538.2 1510.35   661.3 1504.45   682.2 1505.07
   723.7 1516.17   739.1  1518.2   777.5  1515.8   804.2 1507.76   861.9 1510.09
   942.9 1502.56  1200.6 1503.48  1219.8 1493.05 1246.47 1484.74  1249.4 1484.37
  1250.5 1479.02  1572.5 1479.02  1574.8 1484.64  1576.8 1485.31  1586.4 1492.59
  1612.9  1501.5  1639.8 1502.84  1651.4 1501.44  1662.7 1506.06  1711.7 1507.93
  1815.6 1524.99  1863.2 1533.89  1882.2 1546.54  2115.5 1639.88  2132.8 1644.25
#Mann= 9 ,-1 , 0
       0     .04       0   723.7    .016       0   777.5     .04       0
  1200.6     .08       0 1246.47    .045       0  1576.8     .08       0
  1612.9    .016       0  1639.8     .04       0  1815.6      .1       0
#XS Ineff= 2 , 0
          736.62  1524.1
Permanent Ineff=
       F       F
#Block Obstruct= 7 ,-1
  846.28  864.41  1529.9  878.32     910 1528.56 1118.86    1132 1523.81
 1178.34 1204.66 1523.91 1656.99  1699.8 1527.04 1728.74 1756.63 1534.28
  1845.4 1878.44 1563.74
Bank Sta=1246.47,1576.8
XS Rating Curve= 0 ,0
Exp/Cntr=0.5,0.3

Type RM Length L Ch R = 1 ,97308   ,188.6,147.5,160.1
BEGIN DESCRIPTION:
Channel burn based on effective XS CX
END DESCRIPTION:
XS GIS Cut Line= 6
2047543.03015339239026.8625605552046816.16218455238392.665010065
2046725.84281139237990.9827425632046522.71788955237360.774357304
2046074.80113447237074.3162688172045426.36378305236777.441206396
#Sta/Elev= 30
       0 1542.54   322.6 1522.56     549 1518.81   727.5 1510.47   805.7 1515.71
   873.2 1515.52  1062.3 1499.73  1345.2  1500.5  1392.5 1496.73 1409.071484.517
  1411.1  1478.3  1806.1  1478.3 1817.881485.578    1838 1493.71  1890.3 1497.75
  1955.3 1510.22  2066.5 1509.46  2406.4 1517.98  2494.9 1525.63  2522.1 1532.02
  2756.6 1532.55  2792.7 1540.69  2904.6 1546.44  2973.1 1558.21  3030.8  1579.1
  3056.1 1582.19  3070.5 1592.09  3207.7 1644.95  3240.1 1651.75  3283.7 1652.51
#Mann= 7 ,-1 , 0
       0     .04       0   805.7    .016       0   873.2     .04       0
  1345.2     .08       0 1409.07    .045       0 1817.88     .08       0
  1955.3     .04       0
#XS Ineff= 4 ,-1
       0     834    1530     834    1267 1514.16    1957    2170 1511.99
    2170    3000    1530
Permanent Ineff=
       F       F       F       F
#Block Obstruct= 8 ,-1
       0   23.04 1562.54 1169.14 1215.38 1522.08 2013.43 2038.86 1530.42
 2207.59 2267.28 1535.26 2503.29 2549.16 1551.41 2598.99 2664.02 1553.52
 2704.79 2739.77 1554.04 2855.69 2908.65 1566.93
Bank Sta=1409.07,1817.88
XS Rating Curve= 0 ,0
Exp/Cntr=0.5,0.3