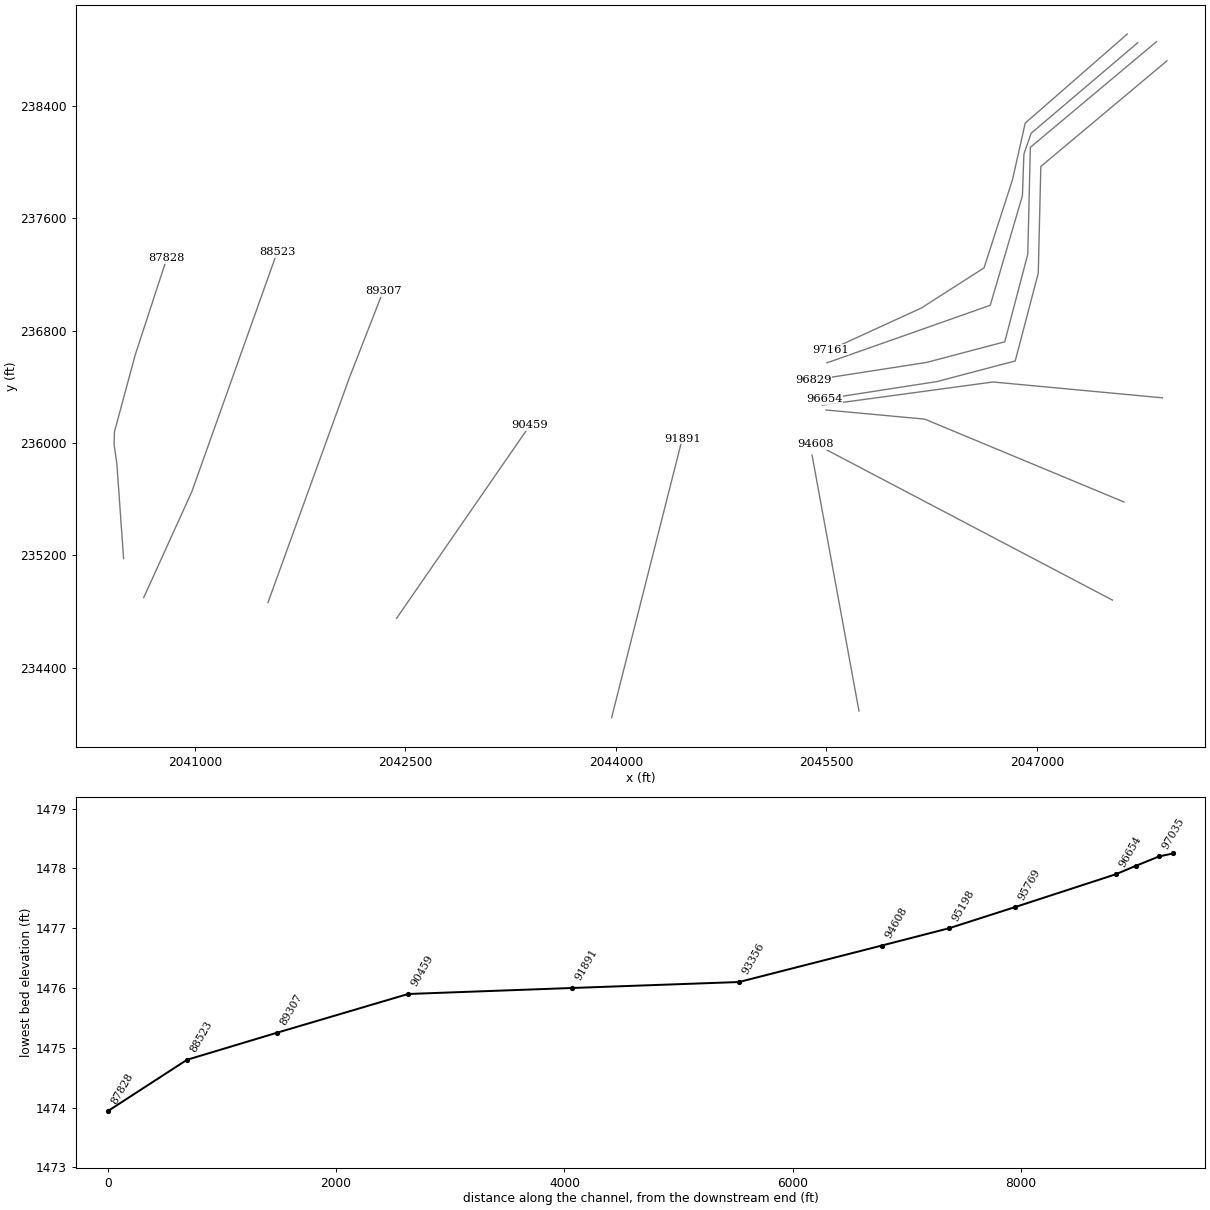
HEC-RAS study GREENBRRV.prj: GREENBRRV

--- GREENBRRV.g01 (geometry) --- (continued)

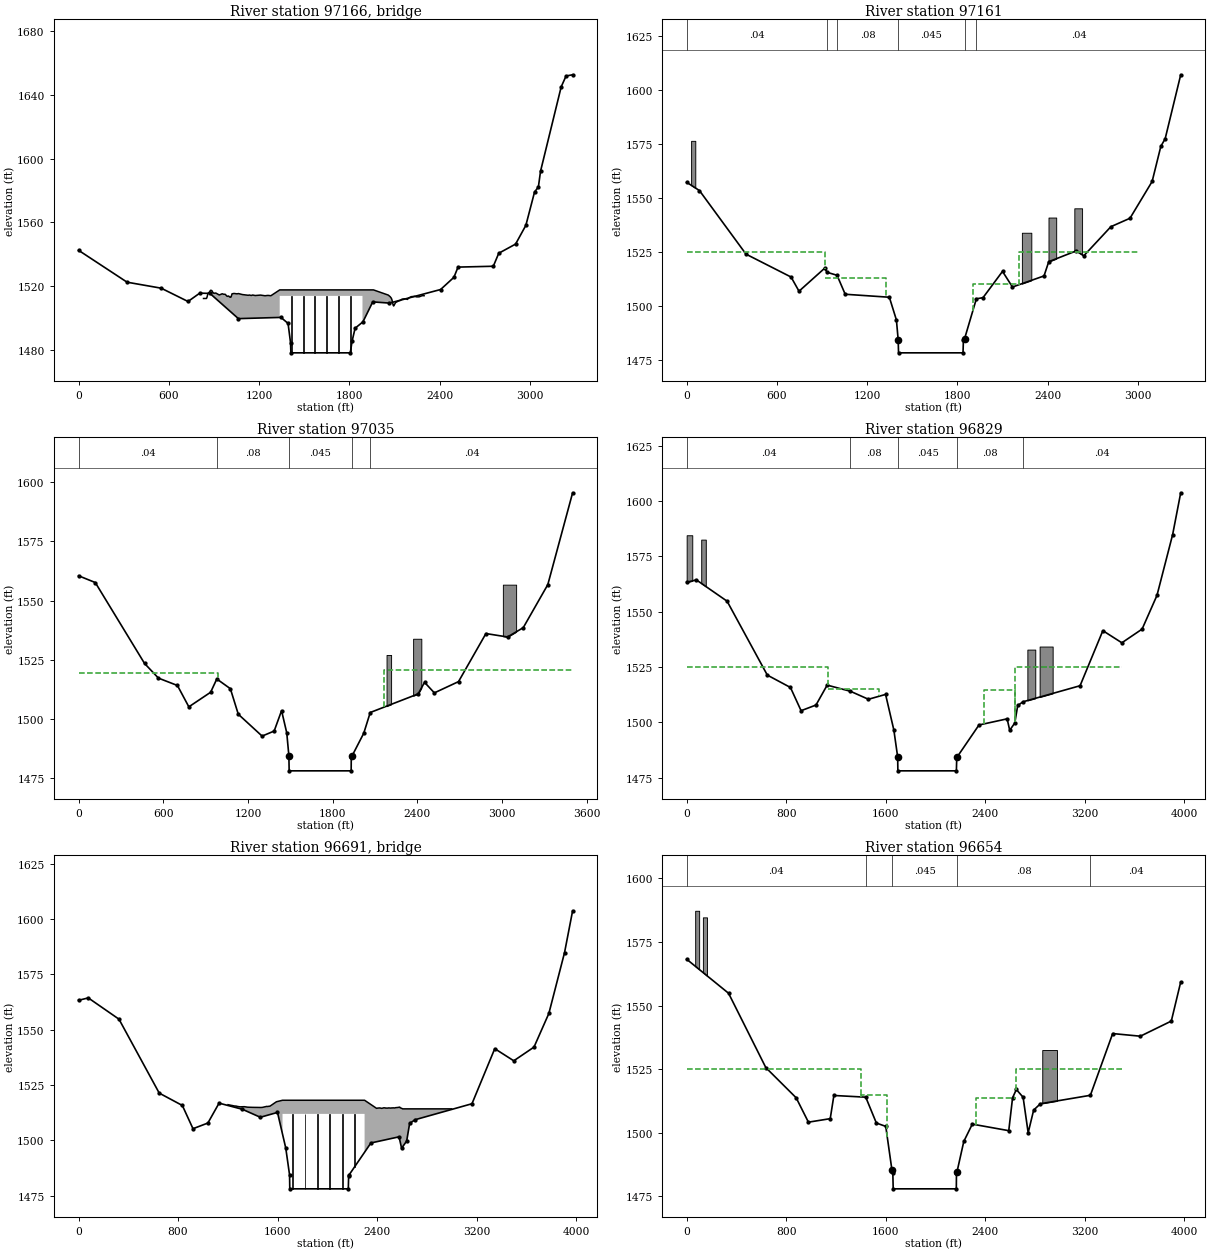
Type RM Length L Ch R = 3 ,97166   ,,,
BEGIN DESCRIPTION:
Lowell Pedestrian Bridge Rd
Bridge Survey Data: GRB060RP
END DESCRIPTION:
Bridge Culvert--1,0,-1,-1, 0
Deck Dist Width WeirC Skew NumUp NumDn MinLoCord MaxHiCord MaxSubmerge Is_Ogee
81,40,2.6,0, 60, 60, , , 0.98, 0, 0,0,,
  830.58   850.2  853.47  860.01  863.28  869.82  876.36  879.63  886.17  892.71
  899.25  912.33  935.22  954.84  964.65  974.45  987.52  997.32 1003.86 1010.39
 1013.66 1020.19 1033.26 1052.87 1062.67 1088.81 1128.02 1134.56 1147.63 1157.43
 1173.77 1209.71 1239.12 1258.72 1278.33    1337    1337    1887    1887    1960
 2058.43 2071.48    2078 2081.27 2084.53 2091.05 2094.31 2107.36 2130.19 2136.72
 2149.76  2172.6 2185.64 2195.43 2211.74 2234.57 2247.62 2263.93  2283.5 2296.55
 1512.35 1512.37 1513.08 1515.42 1515.96 1516.33 1517.41 1517.52 1517.25 1516.13
 1515.64 1515.76 1514.55 1515.31 1514.98    1515 1513.69 1513.91 1513.32  1513.1
 1513.36 1515.28 1515.51 1515.27 1515.44 1514.82 1514.36 1514.53 1514.24 1514.53
 1514.21 1514.48 1514.07 1514.29 1514.081517.7381517.7381517.7381517.7381517.738
 1514.49 1513.44 1512.64 1511.99 1510.92 1508.09 1507.65 1509.83 1510.98 1511.06
 1511.93 1512.18 1511.77 1512.73  1513.5  1513.7 1513.36 1513.39 1514.11 1514.09
                                                                                
                                                                                
                                                                                
                                                1513.9821513.982
                                                                                
                                                                                
   915.6  922.14  928.68  935.22  938.49  945.03  954.84  958.11  964.65  974.45
  977.72  984.25  987.52  990.79  997.32 1000.59 1003.86 1007.12 1010.39 1013.66
 1020.19 1023.46 1026.73 1033.26  1039.8 1046.33 1052.87 1062.67 1088.81 1108.42
 1114.95 1121.49 1128.02 1134.56 1147.63 1157.43  1160.7 1173.77  1180.3 1193.37
 1209.71 1239.12 1258.72 1265.26 1275.06 1278.33    1337    1337    1887    1887
    1960 2058.43 2071.48 2074.74    2078 2081.27 2084.53 2091.05 2094.31 2097.57
 1515.66  1515.4 1514.82 1514.55 1514.54 1514.78 1515.31 1515.28 1514.98    1515
 1514.83 1513.88 1513.69 1513.67 1513.91 1513.75 1513.32 1513.14  1513.1 1513.36
 1515.28 1515.46 1515.34 1515.51 1515.35 1515.47 1515.27 1515.44 1514.82 1514.73
 1514.53 1514.53 1514.36 1514.53 1514.24 1514.53 1514.53 1514.21 1514.32 1514.21
 1514.48 1514.07 1514.29 1514.17 1514.18 1514.081517.7381517.7381517.7381517.738
1517.738 1514.49 1513.44 1513.11 1512.64 1511.99 1510.92 1508.09 1507.65 1508.14
                                                                                
                                                                                
                                                                                
                                                                                
                                                        1513.9821513.982
                                                                                
Pier Skew, UpSta & Num, DnSta & Num=  ,1415, 2 ,1415, 2 , 0 , 0 , 0 ,,
       6       6
       0    1518
       6       6
       0    1518
Pier Skew, UpSta & Num, DnSta & Num=  ,1493, 2 ,1493, 2 , 0 , 0 , 0 ,,
       6       6
       0    1518
       6       6
       0    1518
Pier Skew, UpSta & Num, DnSta & Num=  ,1571, 2 ,1571, 2 , 0 , 0 , 0 ,,
       6       6
       0    1518
       6       6
       0    1518
Pier Skew, UpSta & Num, DnSta & Num=  ,1649, 2 ,1649, 2 , 0 , 0 , 0 ,,
       6       6
       0    1518
       6       6
       0    1518
Pier Skew, UpSta & Num, DnSta & Num=  ,1727, 2 ,1727, 2 , 0 , 0 , 0 ,,
       6       6
       0    1518
       6       6
       0    1518
Pier Skew, UpSta & Num, DnSta & Num=  ,1805, 2 ,1805, 2 , 0 , 0 , 0 ,,
       6       6
       0    1518
       6       6
       0    1518
BR Coef=-1 , 1 , 0 ,1.25, 0 ,,,0.8,0,2,0,
WSPro=,,,, 1 ,,,, 0 ,,,, 0 ,,,,-1 ,-1 ,-1 , 0 , 0 , 0 , 0 , 0
BR U #Sta/Elev= 30
       0 1542.54   322.6 1522.56     549 1518.81   727.5 1510.47   805.7 1515.71
   873.2 1515.52  1062.3 1499.73  1345.2  1500.5  1392.5 1496.73 1409.071484.517
  1411.1  1478.3  1806.1  1478.3 1817.881485.578    1838 1493.71  1890.3 1497.75
  1955.3 1510.22  2066.5 1509.46  2406.4 1517.98  2494.9 1525.63  2522.1 1532.02
  2756.6 1532.55  2792.7 1540.69  2904.6 1546.44  2973.1 1558.21  3030.8  1579.1
  3056.1 1582.19  3070.5 1592.09  3207.7 1644.95  3240.1 1651.75  3283.7 1652.51
BR U #Mann= 7
       0     .04   805.7    .016   873.2     .04  1345.2     .08 1409.07     .04
 1817.88     .08  1955.3     .04
BR D #Sta/Elev= 30
       0 1557.32      85 1553.49   394.5 1524.01     694 1513.39   746.8 1506.82
   916.6 1517.44     934 1515.58   999.6  1514.2  1053.8 1505.41  1347.2 1504.03
  1394.2 1493.47  1405.81484.356  1408.3 1478.25  1836.8 1478.25  1839.4 1484.13
 1847.131484.779  1925.5  1503.3  1969.7 1503.83  2099.3 1516.01  2165.5 1508.77
  2375.2 1513.91  2406.5  1520.5  2588.6  1525.5  2639.6 1523.25  2819.5 1536.73
  2946.6 1540.65  3093.7 1557.69  3151.5 1573.98  3180.3  1577.5  3283.7 1607.17
BR D #Mann= 6
       0     .04     934    .016   999.6     .08  1405.8     .04 1847.13     .08
  1925.5     .04
BC Design=,, 0 ,, 0 ,,,,,,
BC Use User HTab Curves=0
BC User HTab FreeFlow(D)= 0

Type RM Length L Ch R = 1 ,97161   ,63.1,125.7,188.7
BEGIN DESCRIPTION:
Channel burn based on linear interpolation between effective XS CW and CX
END DESCRIPTION:
XS GIS Cut Line= 6
2047642.85672539238914.0153453052046915.98875655238279.817794815
2046825.66938339237878.1355273132046622.54446155237247.927142054
2046174.62770647236961.4690535662045526.19035505236664.593991145
#Sta/Elev= 30
       0 1557.32      85 1553.49   394.5 1524.01     694 1513.39   746.8 1506.82
   916.6 1517.44     934 1515.58   999.6  1514.2  1053.8 1505.41  1347.2 1504.03
  1394.2 1493.47  1405.81484.356  1408.3 1478.25  1836.8 1478.25  1839.4 1484.13
 1847.131484.779  1925.5  1503.3  1969.7 1503.83  2099.3 1516.01  2165.5 1508.77
  2375.2 1513.91  2406.5  1520.5  2588.6  1525.5  2639.6 1523.25  2819.5 1536.73
  2946.6 1540.65  3093.7 1557.69  3151.5 1573.98  3180.3  1577.5  3283.7 1607.17
#Mann= 6 ,-1 , 0
       0     .04       0     934    .016       0   999.6     .08       0
  1405.8    .045       0 1847.13     .08       0  1925.5     .04       0
#XS Ineff= 4 ,-1
       0     920    1525     920    1322    1513    1902    2207    1510
    2207    3000    1525
Permanent Ineff=
       F       F       F       F
#Block Obstruct= 4 ,-1
   29.54   57.42 1576.54 2228.06 2290.75 1533.93 2404.93 2456.09 1540.98
 2576.62 2628.14 1545.26
Bank Sta=1405.8,1847.13
XS Rating Curve= 0 ,0
Exp/Cntr=0.5,0.3

Type RM Length L Ch R = 1 ,97035   ,101.4,205.9,228
BEGIN DESCRIPTION:
Channel burn based on effective XS CW
END DESCRIPTION:
XS GIS Cut Line= 6
2047718.24732263238852.7306909712046957.83086447238206.897336975
2046906.44185963238057.9389734722046896.02521381237762.800128058
2046666.85867739236981.5500501392045503.66415338236571.827772483
#Sta/Elev= 30
       0  1560.5   118.5 1557.64   467.5  1523.5     566 1517.31   700.3 1514.21
   781.2  1505.2   935.4 1511.35   979.2 1516.95  1075.3 1512.85  1131.4 1502.08
  1300.1 1492.86  1385.5 1494.99    1438 1503.59  1474.8 1494.19 1489.731484.556
  1491.7  1478.2  1930.9  1478.2  1931.6 1483.98 1936.891484.445  2020.2 1494.08
    2066 1502.81  2405.5 1510.66  2450.7 1515.54  2520.2 1511.09  2691.3 1515.84
  2885.5 1536.12  3038.5 1534.67  3149.8  1538.6  3323.8 1556.77  3499.5 1595.51
#Mann= 5 ,-1 , 0
       0     .04       0   979.2     .08       0 1489.73    .045       0
 1936.89     .08       0    2066     .04       0
#XS Ineff= 2 , 0
          985.92 1519.35  2163.1         1520.55
Permanent Ineff=
       F       F
#Block Obstruct= 3 ,-1
 2181.45 2213.82 1527.09 2369.76 2427.83 1533.93 3005.46 3099.35 1556.75
Bank Sta=1489.73,1936.89
XS Rating Curve= 0 ,0
Exp/Cntr=0.5,0.3

Type RM Length L Ch R = 1 ,96829   ,161.3,175.4,249.6
BEGIN DESCRIPTION:
Channel burn based on linear interpolation between effective XS CV and CW
END DESCRIPTION:
XS GIS Cut Line= 6
2047851.19029821238859.7618448882046952.40535039238106.868337557
2046934.17638423237346.4515513032046770.11372022236721.451488972
2046214.03740455236574.7503388082045408.48192905236449.750260726
#Sta/Elev= 30
       0 1563.24    78.1 1564.32     325 1554.71   648.7  1521.3   834.6 1515.71
   920.2 1505.21    1040 1507.78  1129.9 1516.77  1317.1 1513.99  1461.6 1510.38
  1599.6 1512.57  1666.3 1496.43 1696.691484.351  1698.5 1478.04    2169 1478.04
  2171.8 1484.01 2177.651484.517  2350.7 1498.76  2577.1 1501.54  2597.7 1496.37
  2638.5 1499.65  2662.2 1507.57  2705.7 1509.26  3163.5  1516.5  3346.8 1541.38
  3499.6  1535.9  3662.3 1542.09  3781.8  1557.3  3907.9  1584.8  3972.8 1603.69
#Mann= 5 ,-1 , 0
       0     .04       0  1317.1     .08       0 1696.69    .045       0
 2177.65     .08       0  2705.7     .04       0
#XS Ineff= 4 ,-1
       0    1140    1525    1140    1545  1514.8    2395    2640 1514.46
    2640    3500    1525
Permanent Ineff=
       F       F       F       F
#Block Obstruct= 4 ,-1
       0   45.14  1584.5  117.09  153.93 1582.53 2739.74 2803.28 1532.83
 2838.24 2943.07 1534.21
Bank Sta=1696.69,2177.65
XS Rating Curve= 0 ,0
Exp/Cntr=0.5,0.3

Type RM Length L Ch R = 3 ,96691   ,,,
BEGIN DESCRIPTION:
CSX
Survey ID:GRB050
END DESCRIPTION:
Bridge Culvert--1,0,-1,-1, 0
Deck Dist Width WeirC Skew NumUp NumDn MinLoCord MaxHiCord MaxSubmerge Is_Ogee
80,30,2.6,0, 175, 175, , , 0.98, 0, 0,0,,
 1201.97 1205.25 1208.53  1211.8 1215.08 1218.36 1221.64 1224.92  1228.2 1231.48
 1234.76 1238.03 1241.31 1244.59 1247.87 1251.15 1254.43 1257.71 1260.98 1264.26
 1267.54 1270.82  1274.1 1277.38 1280.66 1283.93 1287.21 1290.49 1293.77 1297.05
 1300.33 1303.61 1306.89 1310.16 1313.44 1316.72    1320 1323.28 1326.56 1329.84
 1333.11 1336.39 1339.67 1342.95 1346.23 1349.51 1352.79 1356.07 1359.34 1362.62
  1365.9 1369.18 1372.46 1375.74 1379.02 1382.29 1385.57 1388.85 1392.13 1395.41
 1398.69 1401.97 1405.24 1408.52  1411.8 1415.08 1418.36 1421.64 1424.92  1428.2
 1431.47 1434.75 1438.03 1441.31 1444.59 1447.87 1451.15 1454.42  1457.7 1460.98
 1464.26 1467.54 1470.82  1474.1 1477.38 1480.65 1483.93 1487.21 1490.49 1493.77
 1497.05 1500.33  1503.6 1506.88 1510.16 1513.44 1516.72    1520 1523.28 1526.56
 1529.83 1533.11 1536.39 1539.67    1591    1640    1640    2300    2300 2396.51
 2399.78 2403.04  2406.3 2409.56 2412.83 2416.09 2419.35 2422.61 2425.88 2429.14
  2432.4 2435.66 2438.93 2442.19 2445.45 2448.71 2451.97 2455.24  2458.5 2461.76
 2465.02 2468.29 2471.55 2474.81 2478.07 2481.34  2484.6 2487.86 2491.12 2494.39
 2497.65 2500.91 2504.17 2507.44  2510.7 2513.96 2517.22 2520.49 2523.75 2527.01
 2530.27 2533.54  2536.8 2540.06 2543.32 2546.59 2549.85 2553.11 2556.37 2559.64
  2562.9 2566.16 2569.42 2572.69 2575.95 2579.21 2582.47 2585.74 2589.01 2592.28
 2595.54 2598.81 2602.08 2605.35    3000
 1516.07 1516.05    1516 1515.96 1515.92 1515.89 1515.87 1515.82 1515.78 1515.75
 1515.71 1515.65  1515.6 1515.57 1515.54 1515.51 1515.47 1515.47 1515.47 1515.47
 1515.43 1515.37 1515.31 1515.27 1515.24 1515.21 1515.18 1515.15 1515.12  1515.1
  1515.1 1515.11 1515.14 1515.18 1515.19 1515.19  1515.2  1515.2  1515.2  1515.2
 1515.17 1515.15 1515.12 1515.09 1515.07 1515.06    1515 1514.95 1514.94 1514.93
 1514.93 1514.91 1514.88 1514.86 1514.85 1514.85 1514.87 1514.88 1514.89 1514.88
 1514.87 1514.86 1514.86 1514.85 1514.85 1514.85 1514.85 1514.86 1514.84 1514.82
 1514.84 1514.87 1514.87 1514.87 1514.87 1514.87 1514.85 1514.82  1514.8  1514.8
  1514.8  1514.8 1514.78  1514.8 1514.84 1514.88  1514.9 1514.92 1514.97 1515.05
 1515.12 1515.16 1515.18 1515.21 1515.28  1515.3 1515.26 1515.24 1515.29 1515.32
 1515.34 1515.36 1515.39 1515.421517.3921518.0691518.0691518.0691518.069 1514.41
 1514.47 1514.51 1514.54 1514.56 1514.57 1514.59 1514.62  1514.6 1514.55 1514.51
 1514.46 1514.43 1514.42 1514.47 1514.54 1514.56  1514.6 1514.67 1514.63 1514.63
 1514.63 1514.54 1514.53 1514.53 1514.49 1514.47 1514.52 1514.56 1514.57 1514.61
 1514.59 1514.52 1514.54 1514.53 1514.53 1514.57  1514.6 1514.59  1514.6 1514.65
 1514.65  1514.6 1514.59  1514.6 1514.61 1514.68 1514.72 1514.72 1514.73 1514.77
 1514.78  1514.8 1514.87 1514.89 1514.87 1514.94 1514.98 1514.69  1514.6 1514.55
 1514.48 1514.41 1514.31 1514.18 1514.18
                                                                                
                                                                                
                                                                                
                                                                                
                                                                                
                                                                                
                                                                                
                                                                                
                                                                                
                                                                                
                                                1511.9141511.914
                                                                                
                                                                                
                                                                                
                                                                                
                                                                                
                                                                                
                                        
 1201.97 1205.25 1208.53  1211.8 1215.08 1218.36 1221.64 1224.92  1228.2 1231.48
 1234.76 1238.03 1241.31 1244.59 1247.87 1251.15 1254.43 1257.71 1260.98 1264.26
 1267.54 1270.82  1274.1 1277.38 1280.66 1283.93 1287.21 1290.49 1293.77 1297.05
 1300.33 1303.61 1306.89 1310.16 1313.44 1316.72    1320 1323.28 1326.56 1329.84
 1333.11 1336.39 1339.67 1342.95 1346.23 1349.51 1352.79 1356.07 1359.34 1362.62
  1365.9 1369.18 1372.46 1375.74 1379.02 1382.29 1385.57 1388.85 1392.13 1395.41
 1398.69 1401.97 1405.24 1408.52  1411.8 1415.08 1418.36 1421.64 1424.92  1428.2
 1431.47 1434.75 1438.03 1441.31 1444.59 1447.87 1451.15 1454.42  1457.7 1460.98
 1464.26 1467.54 1470.82  1474.1 1477.38 1480.65 1483.93 1487.21 1490.49 1493.77
 1497.05 1500.33  1503.6 1506.88 1510.16 1513.44 1516.72    1520 1523.28 1526.56
 1529.83 1533.11 1536.39 1539.67    1591    1640    1640    2300    2300 2396.51
 2399.78 2403.04  2406.3 2409.56 2412.83 2416.09 2419.35 2422.61 2425.88 2429.14
  2432.4 2435.66 2438.93 2442.19 2445.45 2448.71 2451.97 2455.24  2458.5 2461.76
 2465.02 2468.29 2471.55 2474.81 2478.07 2481.34  2484.6 2487.86 2491.12 2494.39
 2497.65 2500.91 2504.17 2507.44  2510.7 2513.96 2517.22 2520.49 2523.75 2527.01
 2530.27 2533.54  2536.8 2540.06 2543.32 2546.59 2549.85 2553.11 2556.37 2559.64
  2562.9 2566.16 2569.42 2572.69 2575.95 2579.21 2582.47 2585.74 2589.01 2592.28
 2595.54 2598.81 2602.08 2605.35    3000
 1516.07 1516.05    1516 1515.96 1515.92 1515.89 1515.87 1515.82 1515.78 1515.75
 1515.71 1515.65  1515.6 1515.57 1515.54 1515.51 1515.47 1515.47 1515.47 1515.47
 1515.43 1515.37 1515.31 1515.27 1515.24 1515.21 1515.18 1515.15 1515.12  1515.1
  1515.1 1515.11 1515.14 1515.18 1515.19 1515.19  1515.2  1515.2  1515.2  1515.2
 1515.17 1515.15 1515.12 1515.09 1515.07 1515.06    1515 1514.95 1514.94 1514.93
 1514.93 1514.91 1514.88 1514.86 1514.85 1514.85 1514.87 1514.88 1514.89 1514.88
 1514.87 1514.86 1514.86 1514.85 1514.85 1514.85 1514.85 1514.86 1514.84 1514.82
 1514.84 1514.87 1514.87 1514.87 1514.87 1514.87 1514.85 1514.82  1514.8  1514.8
  1514.8  1514.8 1514.78  1514.8 1514.84 1514.88  1514.9 1514.92 1514.97 1515.05
 1515.12 1515.16 1515.18 1515.21 1515.28  1515.3 1515.26 1515.24 1515.29 1515.32
 1515.34 1515.36 1515.39 1515.421517.3921518.0691518.0691518.0691518.069 1514.41
 1514.47 1514.51 1514.54 1514.56 1514.57 1514.59 1514.62  1514.6 1514.55 1514.51
 1514.46 1514.43 1514.42 1514.47 1514.54 1514.56  1514.6 1514.67 1514.63 1514.63
 1514.63 1514.54 1514.53 1514.53 1514.49 1514.47 1514.52 1514.56 1514.57 1514.61
 1514.59 1514.52 1514.54 1514.53 1514.53 1514.57  1514.6 1514.59  1514.6 1514.65
 1514.65  1514.6 1514.59  1514.6 1514.61 1514.68 1514.72 1514.72 1514.73 1514.77
 1514.78  1514.8 1514.87 1514.89 1514.87 1514.94 1514.98 1514.69  1514.6 1514.55
 1514.48 1514.41 1514.31 1514.18 1514.18
                                                                                
                                                                                
                                                                                
                                                                                
                                                                                
                                                                                
                                                                                
                                                                                
                                                                                
                                                                                
                                                1511.9141511.914
                                                                                
                                                                                
                                                                                
                                                                                
                                                                                
                                                                                
                                        
Pier Skew, UpSta & Num, DnSta & Num=  ,1720, 2 ,1720, 2 , 0 , 0 , 0 ,,
       6       6
       0    1516
       6       6
       0    1516
Pier Skew, UpSta & Num, DnSta & Num=  ,1820, 2 ,1820, 2 , 0 , 0 , 0 ,,
       6       6
       0    1516
       6       6
       0    1516
Pier Skew, UpSta & Num, DnSta & Num=  ,1920, 2 ,1920, 2 , 0 , 0 , 0 ,,
       6       6
       0    1516
       6       6
       0    1516
Pier Skew, UpSta & Num, DnSta & Num=  ,2020, 2 ,2020, 2 , 0 , 0 , 0 ,,
       6       6
       0    1516
       6       6
       0    1516
Pier Skew, UpSta & Num, DnSta & Num=  ,2120, 2 ,2120, 2 , 0 , 0 , 0 ,,
       6       6
       0    1516
       6       6
       0    1516
Pier Skew, UpSta & Num, DnSta & Num=  ,2220, 2 ,2220, 2 , 0 , 0 , 0 ,,
       6       6
       0    1516
       6       6
       0    1516
BR Coef=-1 , 1 , 0 ,0.95, 0 ,,,0.8,0,1.33,0,
WSPro=,,,, 1 ,,,, 0 ,,,, 0 ,,,,-1 ,-1 ,-1 , 0 , 0 , 0 , 0 , 0
BR U #Sta/Elev= 30
       0 1563.24    78.1 1564.32     325 1554.71   648.7  1521.3   834.6 1515.71
   920.2 1505.21    1040 1507.78  1129.9 1516.77  1317.1 1513.99  1461.6 1510.38
  1599.6 1512.57  1666.3 1496.43 1696.691484.351  1698.5 1478.04    2169 1478.04
  2171.8 1484.01 2177.651484.517  2350.7 1498.76  2577.1 1501.54  2597.7 1496.37
  2638.5 1499.65  2662.2 1507.57  2705.7 1509.26  3163.5  1516.5  3346.8 1541.38
  3499.6  1535.9  3662.3 1542.09  3781.8  1557.3  3907.9  1584.8  3972.8 1603.69
BR U #Mann= 5
       0     .04  1317.1     .08 1696.69     .04 2177.65     .08  2705.7     .04
BR D #Sta/Elev= 30
       0 1568.21   336.9 1554.83   636.7 1525.58   880.6 1513.71   979.1 1504.12
  1154.5  1505.5  1183.9 1514.62  1440.1 1513.95  1525.5 1503.78  1601.1 1502.46
 1650.941485.218  1657.9 1484.05  1660.9  1477.9  2168.4  1477.9  2169.6 1484.02
 2174.381484.686  2228.6 1496.55    2297 1503.35  2590.1 1500.78  2620.7  1513.7
  2651.2 1516.97  2705.5 1513.92  2746.2 1499.95  2790.3 1508.88  2844.6 1511.37
  3246.4 1514.69  3425.7 1538.97  3648.2 1537.93  3897.2 1543.88  3972.8 1559.25
BR D #Mann= 5
       0     .04  1440.1     .08 1650.94     .04 2174.38     .08  3246.4     .04
BC Design=,, 0 ,, 0 ,,,,,,
BC Use User HTab Curves=0
BC User HTab FreeFlow(D)= 0

Type RM Length L Ch R = 1 ,96654   ,1508.3,884.5,220.5
BEGIN DESCRIPTION:
Channel burn based on effective XS CV
END DESCRIPTION:
XS GIS Cut Line= 6
2047925.84336413238723.4773405642047027.05841631237970.583833233
2047008.82945013237210.1670469792046844.76678614236585.166984648
2046288.69047047236438.4658344842045483.13499497236313.465756387
#Sta/Elev= 30
       0 1568.21   336.9 1554.83   636.7 1525.58   880.6 1513.71   979.1 1504.12
  1154.5  1505.5  1183.9 1514.62  1440.1 1513.95  1525.5 1503.78  1601.1 1502.46
 1650.941485.218  1657.9 1484.05  1660.9  1477.9  2168.4  1477.9  2169.6 1484.02
 2174.381484.686  2228.6 1496.55    2297 1503.35  2590.1 1500.78  2620.7  1513.7
  2651.2 1516.97  2705.5 1513.92  2746.2 1499.95  2790.3 1508.88  2844.6 1511.37
  3246.4 1514.69  3425.7 1538.97  3648.2 1537.93  3897.2 1543.88  3972.8 1559.25
#Mann= 5 ,-1 , 0
       0     .04       0  1440.1     .08       0 1650.94    .045       0
 2174.38     .08       0  3246.4     .04       0
#XS Ineff= 4 ,-1
       0    1400    1525    14001613.333  1514.72326.667    2650  1513.8
    2650    3500    1525
Permanent Ineff=
       F       F       F       F
#Block Obstruct= 3 ,-1
   68.49  100.48 1587.26  130.67  163.55 1584.67 2859.39 2977.91 1532.49
Bank Sta=1650.94,2174.38
XS Rating Curve= 0 ,0
Exp/Cntr=0.5,0.3

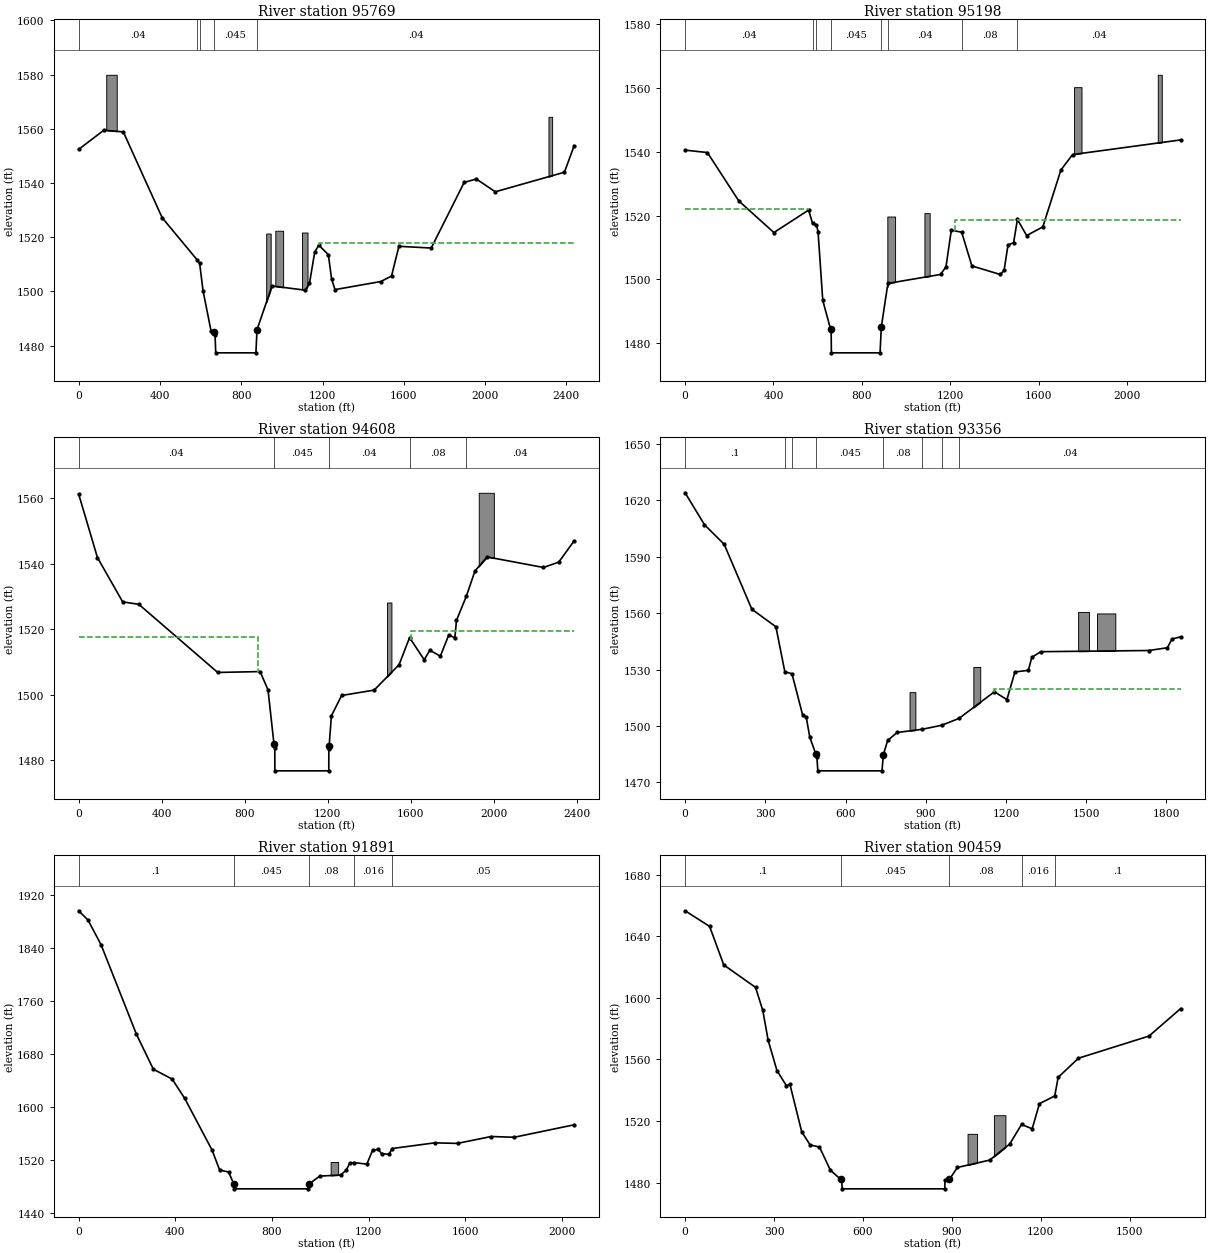
Type RM Length L Ch R = 1 ,95769   ,615.5,571.6,482.4
BEGIN DESCRIPTION:
Channel burn based on linear interpolation between effective XS CU and CV
END DESCRIPTION:
Node Name=AB
XS GIS Cut Line= 3
2047892.92807564236322.4834548982046686.33107939236435.330670148
2045471.05299814 236270.39989765
#Sta/Elev= 30
       0 1552.42   124.3 1559.52   219.9 1558.87     411 1527.21   583.3 1511.64
   595.5 1510.39     612 1500.32   651.6 1485.41  664.891484.985   671.3    1484
   674.6 1477.35   872.3 1477.35  877.781485.903   951.4 1502.03  1115.6 1500.47
  1135.9 1502.99  1161.8  1514.6  1182.1 1517.05  1228.7 1513.57  1244.8 1504.58
  1261.4 1500.68  1486.5 1503.66  1539.5 1505.68  1575.9 1516.66  1734.9 1516.02
  1897.1 1540.24  1956.8  1541.5  2050.1 1536.78  2390.4    1544  2438.3 1553.82
#Mann= 5 ,-1 , 0
       0     .04       0   583.3    .016       0   595.5     .08       0
  664.89    .045       0  877.78     .04       0
#XS Ineff= 2 , 0
                          1183.1         1517.81
Permanent Ineff=
       F       F
#Block Obstruct= 5 ,-1
  135.82  187.49 1579.96  922.88  944.91 1521.37  967.73 1006.26 1522.41
 1098.94 1126.29 1521.75 2311.85 2329.88 1564.44
Bank Sta=664.89,877.78
XS Rating Curve= 0 ,0
Exp/Cntr=0.3,0.1

Type RM Length L Ch R = 1 ,95198   ,602.2,590.3,567.7
BEGIN DESCRIPTION:
Channel burn based on effective XS CU
END DESCRIPTION:
XS GIS Cut Line= 3
2047619.49063039  235580.29596292046200.21984689236170.573653728
2045497.09494081236235.677854225
#Sta/Elev= 30
       0 1540.53   100.9 1539.78     243 1524.62     402  1514.7   559.2 1521.75
     577 1517.58   594.8  1517.1   601.9 1514.99   623.2 1493.43  658.771484.396
   661.1 1483.84   662.3    1477   882.6    1477  888.191485.121   918.1 1498.76
  1156.2 1501.57  1181.1 1503.97  1205.1 1515.45  1252.1  1514.8  1298.3 1504.24
  1426.5 1501.56    1444 1502.81  1461.8 1510.82  1487.1 1511.52  1504.4 1518.81
  1546.3 1513.76  1619.4 1516.48  1701.2  1534.3    1754 1539.14  2243.3 1543.73
#Mann= 8 ,-1 , 0
       0     .04       0     577    .016       0   594.8     .08       0
  658.77    .045       0  888.19     .08       0   918.1     .04       0
  1252.1     .08       0  1504.4     .04       0
#XS Ineff= 2 , 0
          557.75 1522.21 1221.13         1518.57
Permanent Ineff=
       F       F
#Block Obstruct= 4 ,-1
  915.49  950.61 1519.72 1083.46 1107.06 1520.79 1760.81 1794.56 1560.27
 2139.77 2157.97 1564.15
Bank Sta=658.77,888.19
XS Rating Curve= 0 ,0
Exp/Cntr=0.3,0.1

Type RM Length L Ch R = 1 ,94608   ,1411.8,1251.4,1003.2
BEGIN DESCRIPTION:
Channel burn based on linear interpolation between effective XS CT and CU
END DESCRIPTION:
XS GIS Cut Line= 2
2047537.02524413234881.5112712232045423.30998339 235992.62223798
#Sta/Elev= 30
       0 1561.27    90.6 1541.86   212.2 1528.32     290 1527.57   670.2 1506.76
   874.7 1507.03   912.7 1501.43  941.411484.878   945.2 1483.56   945.8 1476.71
  1205.5 1476.71  1205.7 1483.48  1207.11484.191  1217.9  1493.5  1267.5 1499.73
  1424.2 1501.37  1544.5 1509.15  1594.7 1517.41  1665.2 1510.65  1692.6 1513.55
    1743 1511.73  1783.9 1518.22  1813.1 1517.31  1820.8 1522.66    1869 1530.15
  1909.8 1537.75  1968.6 1542.05  2239.7 1538.83  2313.5 1540.44    2388 1546.97
#Mann= 5 ,-1 , 0
       0     .04       0  941.41    .045       0  1207.1     .04       0
  1594.7     .08       0    1869     .04       0
#XS Ineff= 2 , 0
          861.97 1517.56 1602.82         1519.57
Permanent Ineff=
       F       F
#Block Obstruct= 2 ,-1
  1485.9 1507.38 1528.12 1928.11 2000.91 1561.64
Bank Sta=941.41,1207.1
XS Rating Curve= 0 ,0
Exp/Cntr=0.3,0.1

Type RM Length L Ch R = 1 ,93356   ,1547.8,1465.2,1375.5
BEGIN DESCRIPTION:
Channel burn based on effective XS CT
END DESCRIPTION:
XS GIS Cut Line= 2
2045731.46980014234091.5804363942045397.26836881235914.497394234
#Sta/Elev= 30
       0 1624.06    72.5 1607.06   146.2 1596.64   249.6  1562.1   339.6 1552.77
     373 1528.82   399.7 1527.75   439.7 1505.77     453  1504.7   466.4 1493.99
  488.751485.111     493 1483.25   496.4  1476.1   736.5  1476.1  741.321484.601
   757.5  1492.3   793.2 1496.51   886.6 1498.21     960 1500.36  1024.8 1504.03
  1156.8 1518.17  1203.5 1513.99  1233.5 1528.71  1283.6 1529.59  1296.9 1536.53
  1330.3  1539.5  1733.9 1540.13  1803.9  1541.6  1820.6 1546.22  1853.3 1547.42
#Mann= 8 ,-1 , 0
       0      .1       0     373    .016       0   399.7      .1       0
  488.75    .045       0  741.32     .08       0   886.6     .04       0
     960    .016       0  1024.8     .04       0
#XS Ineff= 2 , 0
                         1156.06          1519.4
Permanent Ineff=
       F       F
#Block Obstruct= 4 ,-1
  839.42   861.2 1517.99 1078.01 1103.84 1531.37 1469.92 1510.78 1560.66
 1540.63 1608.97 1559.85
Bank Sta=488.75,741.32
XS Rating Curve= 0 ,0
Exp/Cntr=0.3,0.1

Type RM Length L Ch R = 1 ,91891   ,1510.9,1432.3,1332.8
BEGIN DESCRIPTION:
Channel burn based on effective XS CS
END DESCRIPTION:
Node Name=AA
XS GIS Cut Line= 2
2043969.31715646234043.8374216412044472.78924663  236031.6848239
#Sta/Elev= 30
       0 1896.17    38.5 1882.28    92.6 1845.07   239.1 1709.65   309.2 1656.71
   387.1 1641.83     439 1612.66   552.4 1534.36   583.4 1504.49   620.6 1501.36
  642.051483.414   644.3    1476   949.4    1476  953.241483.314   997.9 1495.23
  1084.3 1496.93    1108 1504.33  1121.5  1514.5  1138.4 1515.69  1192.6 1513.36
  1216.3 1534.01    1240 1535.72  1253.5 1529.26    1284 1528.13  1297.5 1536.95
  1473.3 1545.48  1567.8 1544.67    1707 1555.07  1802.7 1553.94  2050.6 1572.79
#Mann= 5 ,-1 , 0
       0      .1       0  642.05    .045       0  953.24     .08       0
  1138.4    .016       0  1297.5     .05       0
#Block Obstruct= 1 ,-1
 1042.81 1073.97 1516.58
Bank Sta=642.05,953.24
XS Rating Curve= 0 ,0
Exp/Cntr=0.3,0.1

Type RM Length L Ch R = 1 ,90459   ,1030.8,1152.1,1183.4
BEGIN DESCRIPTION:
Channel burn based on effective XS CR
END DESCRIPTION:
XS GIS Cut Line= 2
2042437.19882964234751.3028702292043387.71989447236127.170853391
#Sta/Elev= 30
       0 1656.62    82.7 1646.46   130.5 1621.44   237.7 1606.83   262.1 1591.92
   280.4  1572.4     310 1552.76   341.9 1542.93   353.8 1543.79   393.5    1513
   421.9 1504.43   453.5 1503.09   490.3 1488.02  524.641482.151   528.1 1481.58
   530.4  1475.9   876.2  1475.9   877.1 1481.36  891.881481.993   918.8 1489.78
    1028 1494.59  1095.5 1505.04  1135.4 1517.74  1171.3 1514.93  1195.8 1531.23
  1247.4 1536.28    1259 1548.37  1327.5  1560.8  1565.7 1575.21  1672.3 1593.05
#Mann= 5 ,-1 , 0
       0      .1       0  524.64    .045       0  891.88     .08       0
  1135.4    .016       0  1247.4      .1       0
#Block Obstruct= 2 ,-1
  953.19  985.37 1511.66 1042.12 1080.96 1523.75
Bank Sta=524.64,891.88
XS Rating Curve= 0 ,0
Exp/Cntr=0.3,0.1

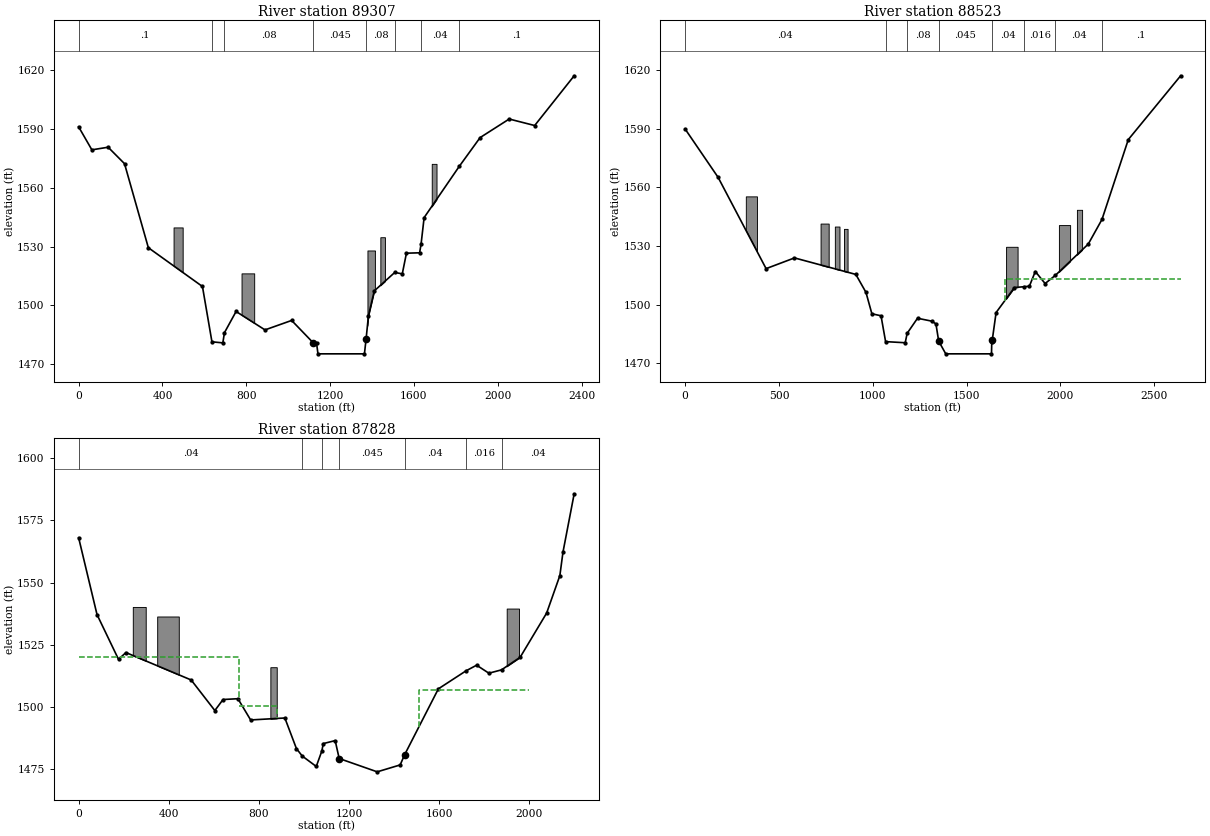
Type RM Length L Ch R = 1 ,89307   ,783.2,784,783.7
BEGIN DESCRIPTION:
Channel burn based on linear interpolation between effective XS CQ and CR
END DESCRIPTION:
XS GIS Cut Line= 3
2041521.40046439234864.1500854792042102.99772638236470.052713558
2042341.71280013 237082.03213264
#Sta/Elev= 30
       0  1591.2    63.2 1579.45   140.8 1580.79     219 1572.38   332.7 1529.46
   590.9 1509.65   636.2 1481.39   688.2 1480.85   695.9 1486.06   751.4 1496.89
   889.4 1487.48  1016.6 1492.31 1118.641480.981  1135.2 1480.89  1142.2 1475.25
 1363.97 1475.25  1372.1 1483.03    1383 1494.67  1410.9  1507.4  1508.6 1516.82
  1544.6 1516.11  1564.4 1526.66  1627.2 1526.86  1634.2 1531.22  1648.8 1544.84
  1816.6 1571.03    1916 1585.71  2054.8 1595.19  2176.4 1591.87  2364.9 1617.28
#Mann= 8 ,-1 , 0
       0      .1       0   636.2    .045       0   695.9     .08       0
 1118.64    .045       0  1372.1     .08       0  1508.6    .016       0
  1634.2     .04       0  1816.6      .1       0
#Block Obstruct= 5 ,-1
  453.07  496.51 1539.82  777.47  837.85 1516.35 1378.34 1413.92 1528.05
 1439.92 1461.74 1534.82 1685.18 1707.98 1572.29
Bank Sta=1118.64,1372.1
XS Rating Curve= 0 ,0
Exp/Cntr=0.3,0.1

Type RM Length L Ch R = 1 ,88523   ,665.3,695,708.4
BEGIN DESCRIPTION:
Channel burn based on effective XS CQ
END DESCRIPTION:
Node Name=Z
XS GIS Cut Line= 3
2040635.98360005234898.8721288892040978.86578831 235654.08059223
2041586.50466488 237359.80979231
#Sta/Elev= 30
       0 1589.92   175.7 1565.18   431.5 1518.42   582.8 1523.91   909.6 1515.46
   963.6 1506.27   995.1 1495.31  1043.8 1494.28  1068.2 1481.05  1172.7 1480.48
  1183.1 1485.31  1238.3 1493.02  1312.8 1491.56  1336.4 1490.16 1350.97 1481.33
  1388.6  1474.8  1632.4  1474.8  1633.8 1480.79 1636.361481.758  1656.9 1495.94
  1754.5 1508.74  1806.6 1509.17  1834.1  1509.4  1865.8 1516.95    1918  1510.8
  1972.8 1514.99  2147.9 1530.99    2221  1543.6  2361.2 1584.48  2640.1 1617.15
#Mann= 8 ,-1 , 0
       0     .04       0  1068.2    .045       0  1183.1     .08       0
 1350.97    .045       0 1636.36     .04       0  1806.6    .016       0
  1972.8     .04       0    2221      .1       0
#XS Ineff= 2 , 0
                         1703.66         1512.89
Permanent Ineff=
       F       F
#Block Obstruct= 7 ,-1
  323.49  382.78 1555.41  721.79  764.95 1541.49  797.84  822.57 1539.97
  846.47  865.61 1538.77 1710.08 1771.41  1529.6 1991.58 2051.26 1540.72
 2087.51  2115.1 1548.53
Bank Sta=1350.97,1636.36
XS Rating Curve= 0 ,0
Exp/Cntr=0.5,0.3

Type RM Length L Ch R = 1 ,87828   ,156.3,159.2,159.2
BEGIN DESCRIPTION:
Channel burned from survey: 54089GRB042BU
END DESCRIPTION:
XS GIS Cut Line= 6
 2040492.7703038235177.6150097252040444.51318248235855.254074395
2040425.06046547235989.197376058 2040427.6661033236080.392731726
2040575.23536196236627.2676222322040800.92979246237317.371885061
#Sta/Elev= 30
       0 1568.08    81.6 1537.16   176.9 1519.18   209.8  1521.9   499.3 1510.87
   604.3 1498.59   640.7 1503.02   706.7 1503.34   763.1  1494.8   914.9 1495.59
   966.2 1483.29  992.17 1480.28 1054.26  1476.1 1078.86  1482.3 1085.48  1485.3
 1138.16  1486.5 1155.86  1479.3 1324.58 1473.94 1426.41 1476.72 1446.181480.808
  1595.9 1507.31  1718.6 1514.55  1765.6 1516.82    1820  1513.6    1876 1514.94
  1958.9 1520.02  2076.2 1537.77  2134.9 1552.85  2148.7 1562.27  2198.4 1585.74
#Mann= 7 ,-1 , 0
       0     .04       0  992.17    .045       0 1078.86     .08       0
 1155.86    .045       0 1446.18     .04       0  1718.6    .016       0
    1876     .04       0
#XS Ineff= 3 ,-1
       0     710    1520     710     879  1500.3    1509    2000 1506.67
Permanent Ineff=
       F       F       F
#Block Obstruct= 4 ,-1
  240.31  297.66 1540.24  348.49  444.31  1536.4  850.62   878.9 1516.01
 1899.09 1953.58 1539.59
Bank Sta=1155.86,1446.18
XS Rating Curve= 0 ,0
Exp/Cntr=0.5,0.3