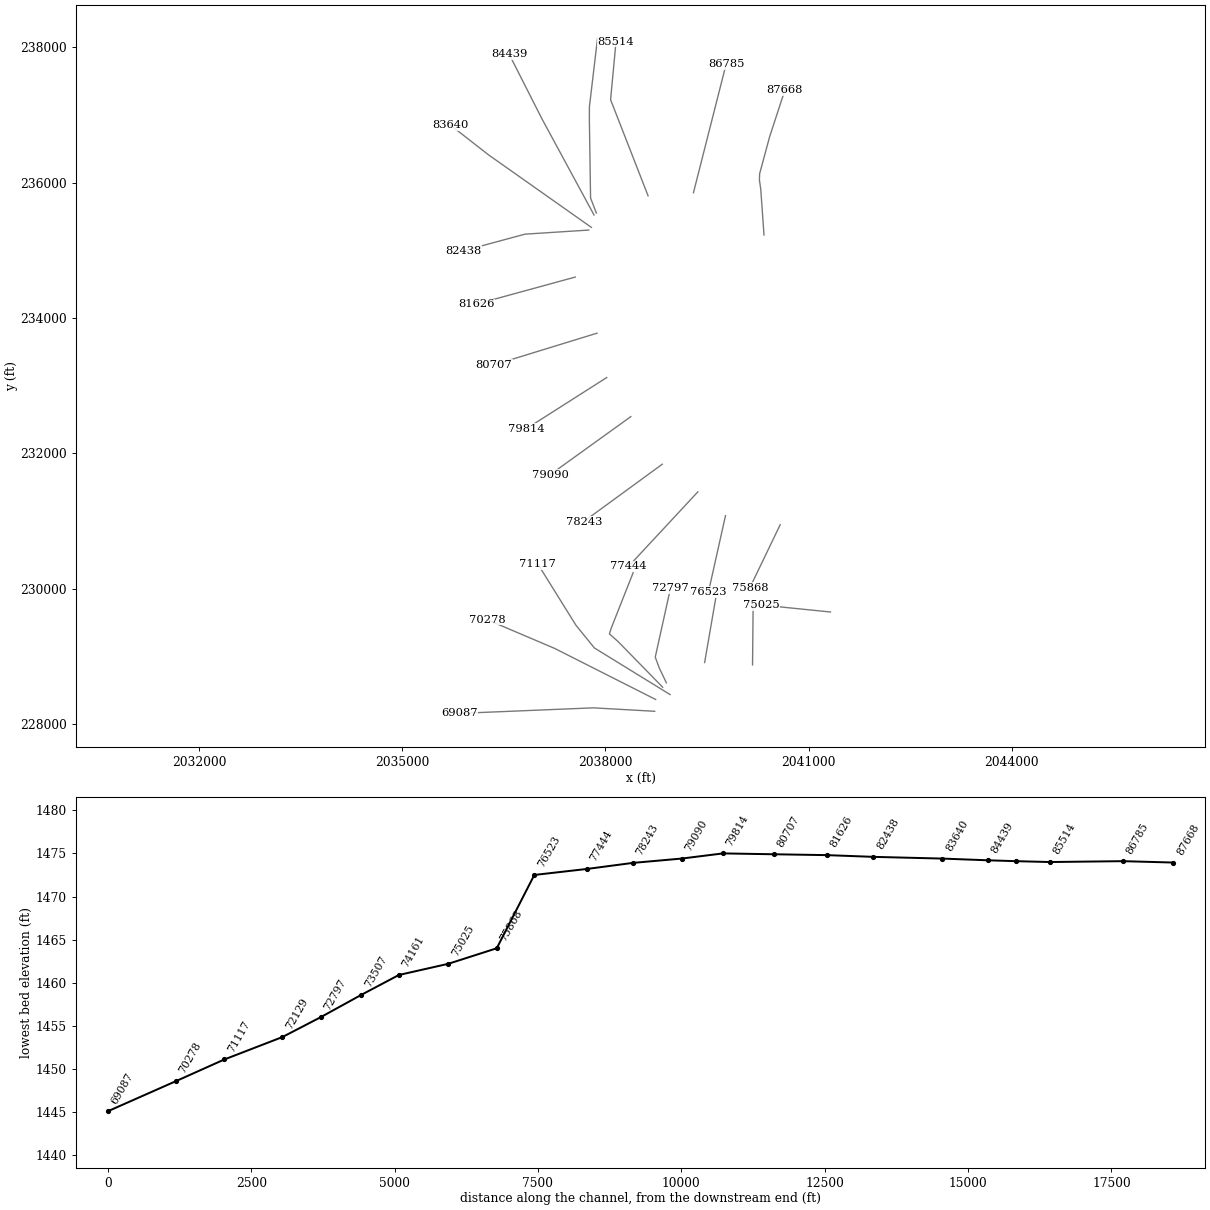
HEC-RAS study GREENBRRV.prj: GREENBRRV

--- GREENBRRV.g01 (geometry) --- (continued)

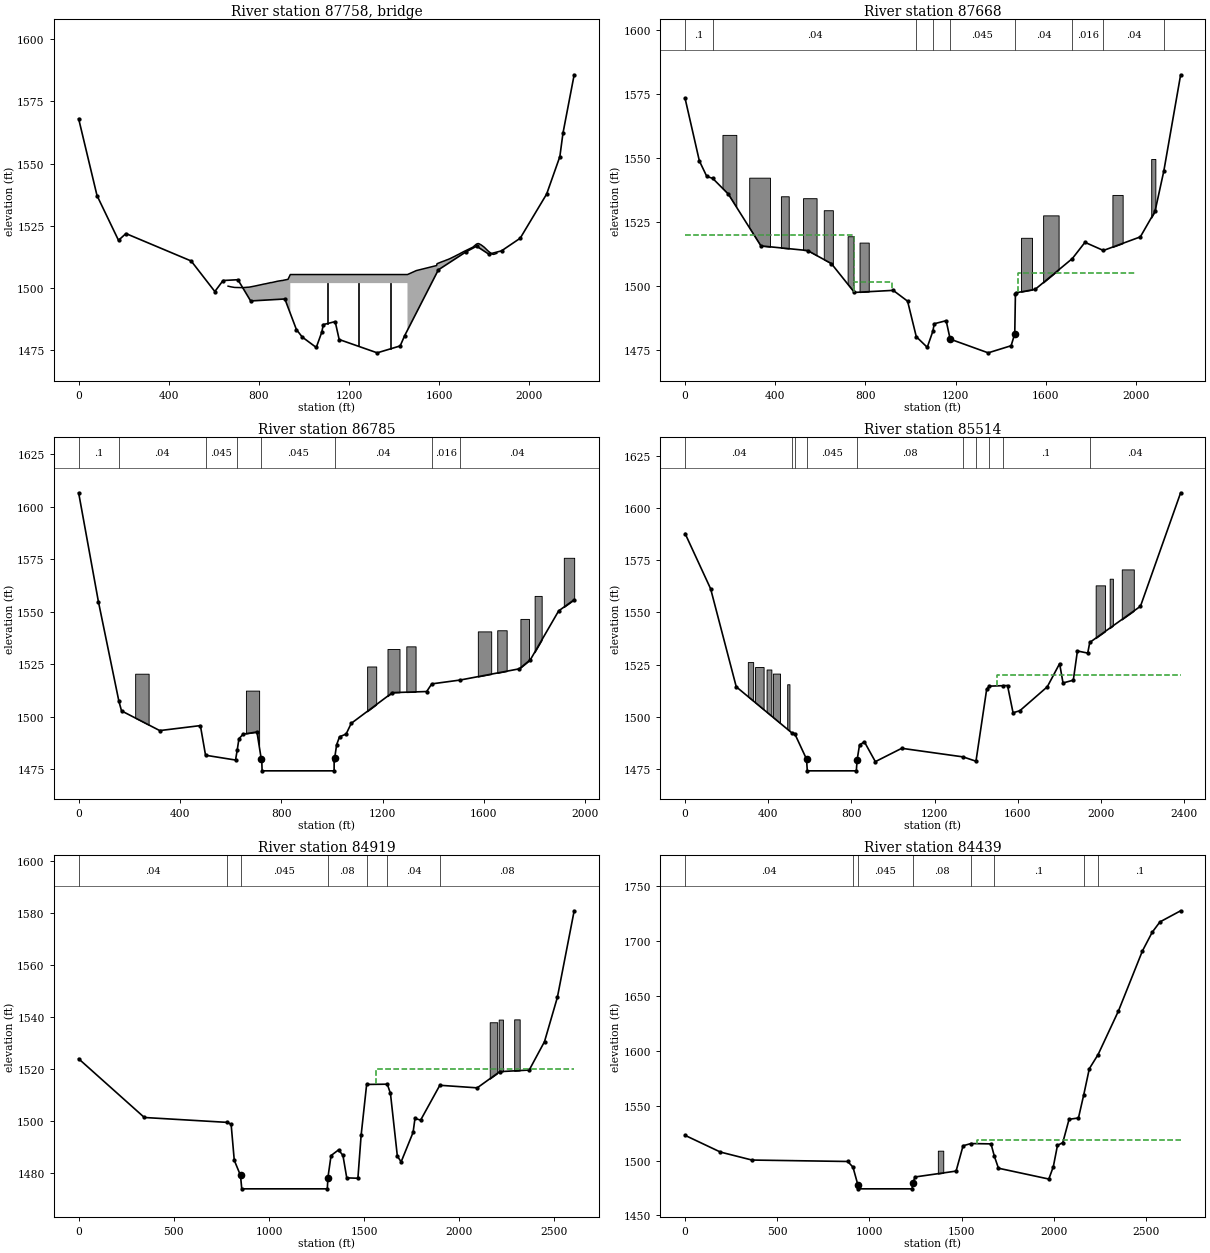
Type RM Length L Ch R = 3 ,87758   ,,,
BEGIN DESCRIPTION:
County Route 17/ Barger Springs Rd
Survey ID: GRB040
END DESCRIPTION:
Bridge Culvert--1,0,-1,-1, 0
Deck Dist Width WeirC Skew NumUp NumDn MinLoCord MaxHiCord MaxSubmerge Is_Ogee
63,30,2.6,0, 168, 168, , , 0.98, 0, 0,0,,
  663.02  666.29  669.56  672.82  676.09  679.35  682.58   685.8  689.02  692.25
  695.47  698.69  701.91  705.14  708.36  711.58   714.8  718.03  721.25  724.47
  727.69  730.92  734.14  737.36  740.58  743.81  747.03  750.25  753.47   756.7
  759.92  763.14  766.36  769.59  772.81  776.03  779.25  782.48   785.7  788.92
  792.15  795.37  798.59  801.81  805.04  808.26  811.48   814.7  817.96  821.22
  824.48  827.74  830.99  834.25  837.51  840.77  844.03  847.29  850.54   853.8
  857.06  860.32  863.58  866.84  870.09  873.35  876.61  879.87  883.13  886.39
  889.64   892.9  896.16  899.42  902.68  905.94  909.21  928.86     939     939
     961    1317    1459    1459    1498    1588 1590.11 1593.38 1596.65 1599.93
  1603.2 1606.47 1609.74 1613.01 1616.28 1619.55 1622.82 1626.09 1629.36 1632.63
  1635.9 1639.17 1642.44 1645.71 1648.98 1652.25 1655.53  1658.8 1662.07 1665.34
 1668.61 1671.88 1675.15 1678.42 1681.69 1684.96 1688.23  1691.5 1694.77 1698.04
 1701.31 1704.58 1707.85 1711.12  1714.4 1717.67 1720.94 1724.21 1727.48 1730.75
 1734.02 1737.29 1740.56 1743.83  1747.1 1750.37 1753.64 1756.91 1760.18 1763.45
 1766.73    1770 1773.27 1776.54 1779.81 1783.08 1786.35 1789.62 1792.89 1796.16
 1799.43  1802.7 1805.97 1809.24 1812.51 1815.78 1819.05 1822.33  1825.6 1828.87
 1832.14 1835.41 1838.68 1841.95 1845.22 1848.49 1851.76 1855.03
 1500.75 1500.67 1500.57 1500.51 1500.47 1500.42 1500.35 1500.29 1500.25 1500.23
 1500.22  1500.2 1500.16 1500.15 1500.15 1500.15 1500.15 1500.16 1500.15 1500.15
 1500.15 1500.18 1500.21 1500.24 1500.25 1500.27  1500.3 1500.33 1500.33 1500.39
 1500.41 1500.46 1500.52 1500.59 1500.64 1500.69 1500.75 1500.81 1500.88 1500.92
    1501 1501.05  1501.1 1501.17 1501.23 1501.29 1501.38 1501.46 1501.52 1501.58
 1501.62 1501.68 1501.74  1501.8 1501.87 1501.91 1501.97 1502.07 1502.16 1502.18
 1502.21 1502.27 1502.32 1502.39 1502.48 1502.56 1502.63 1502.69 1502.73 1502.77
 1502.85  1502.9 1502.95 1503.01 1503.03 1503.04 1503.14  1503.51505.4241505.424
1505.4241505.4241505.4241505.4241507.0131509.042 1509.79  1509.9 1510.01 1510.13
 1510.26 1510.38 1510.51 1510.61 1510.71 1510.82 1510.93 1511.06  1511.2 1511.29
 1511.38  1511.5 1511.62 1511.75 1511.89 1512.03 1512.16 1512.31 1512.47 1512.62
 1512.77 1512.91 1513.09 1513.23 1513.39 1513.52 1513.66 1513.81 1513.99 1514.16
 1514.32 1514.46 1514.61 1514.78  1514.9 1515.05 1515.19 1515.32 1515.46 1515.59
 1515.73 1515.88 1516.03 1516.18 1516.35 1516.53 1516.77 1517.05 1517.31 1517.55
 1517.73 1517.83 1517.88 1517.79 1517.64 1517.48  1517.3 1517.09 1516.89 1516.65
 1516.41 1516.14 1515.84 1515.54 1515.24 1514.96 1514.71 1514.47 1514.23 1514.02
 1513.81 1513.65 1513.54 1513.55 1513.65 1513.73 1513.83 1513.94
                                                                                
                                                                                
                                                                                
                                                                                
                                                                                
                                                                                
                                                                                
                                                                         1501.97
 1501.97 1501.97 1501.97
                                                                                
                                                                                
                                                                                
                                                                                
                                                                                
                                                                                
                                                                                
                                                                
  663.02  666.29  669.56  672.82  676.09  679.35  682.58   685.8  689.02  692.25
  695.47  698.69  701.91  705.14  708.36  711.58   714.8  718.03  721.25  724.47
  727.69  730.92  734.14  737.36  740.58  743.81  747.03  750.25  753.47   756.7
  759.92  763.14  766.36  769.59  772.81  776.03  779.25  782.48   785.7  788.92
  792.15  795.37  798.59  801.81  805.04  808.26  811.48   814.7  817.96  821.22
  824.48  827.74  830.99  834.25  837.51  840.77  844.03  847.29  850.54   853.8
  857.06  860.32  863.58  866.84  870.09  873.35  876.61  879.87  883.13  886.39
  889.64   892.9  896.16  899.42  902.68  905.94  909.21  928.86     939     939
     961    1317    1459    1459    1498    1588 1590.11 1593.38 1596.65 1599.93
  1603.2 1606.47 1609.74 1613.01 1616.28 1619.55 1622.82 1626.09 1629.36 1632.63
  1635.9 1639.17 1642.44 1645.71 1648.98 1652.25 1655.53  1658.8 1662.07 1665.34
 1668.61 1671.88 1675.15 1678.42 1681.69 1684.96 1688.23  1691.5 1694.77 1698.04
 1701.31 1704.58 1707.85 1711.12  1714.4 1717.67 1720.94 1724.21 1727.48 1730.75
 1734.02 1737.29 1740.56 1743.83  1747.1 1750.37 1753.64 1756.91 1760.18 1763.45
 1766.73    1770 1773.27 1776.54 1779.81 1783.08 1786.35 1789.62 1792.89 1796.16
 1799.43  1802.7 1805.97 1809.24 1812.51 1815.78 1819.05 1822.33  1825.6 1828.87
 1832.14 1835.41 1838.68 1841.95 1845.22 1848.49 1851.76 1855.03
 1500.75 1500.67 1500.57 1500.51 1500.47 1500.42 1500.35 1500.29 1500.25 1500.23
 1500.22  1500.2 1500.16 1500.15 1500.15 1500.15 1500.15 1500.16 1500.15 1500.15
 1500.15 1500.18 1500.21 1500.24 1500.25 1500.27  1500.3 1500.33 1500.33 1500.39
 1500.41 1500.46 1500.52 1500.59 1500.64 1500.69 1500.75 1500.81 1500.88 1500.92
    1501 1501.05  1501.1 1501.17 1501.23 1501.29 1501.38 1501.46 1501.52 1501.58
 1501.62 1501.68 1501.74  1501.8 1501.87 1501.91 1501.97 1502.07 1502.16 1502.18
 1502.21 1502.27 1502.32 1502.39 1502.48 1502.56 1502.63 1502.69 1502.73 1502.77
 1502.85  1502.9 1502.95 1503.01 1503.03 1503.04 1503.14  1503.51505.4241505.424
1505.4241505.4241505.4241505.4241507.0131509.042 1509.79  1509.9 1510.01 1510.13
 1510.26 1510.38 1510.51 1510.61 1510.71 1510.82 1510.93 1511.06  1511.2 1511.29
 1511.38  1511.5 1511.62 1511.75 1511.89 1512.03 1512.16 1512.31 1512.47 1512.62
 1512.77 1512.91 1513.09 1513.23 1513.39 1513.52 1513.66 1513.81 1513.99 1514.16
 1514.32 1514.46 1514.61 1514.78  1514.9 1515.05 1515.19 1515.32 1515.46 1515.59
 1515.73 1515.88 1516.03 1516.18 1516.35 1516.53 1516.77 1517.05 1517.31 1517.55
 1517.73 1517.83 1517.88 1517.79 1517.64 1517.48  1517.3 1517.09 1516.89 1516.65
 1516.41 1516.14 1515.84 1515.54 1515.24 1514.96 1514.71 1514.47 1514.23 1514.02
 1513.81 1513.65 1513.54 1513.55 1513.65 1513.73 1513.83 1513.94
                                                                                
                                                                                
                                                                                
                                                                                
                                                                                
                                                                                
                                                                                
                                                                         1501.97
 1501.97 1501.97 1501.97
                                                                                
                                                                                
                                                                                
                                                                                
                                                                                
                                                                                
                                                                                
                                                                
Pier Skew, UpSta & Num, DnSta & Num=  ,1104, 2 ,1104, 2 , 0 , 0 , 0 ,,
       3       3
       0    1504
       3       3
       0    1504
Pier Skew, UpSta & Num, DnSta & Num=  ,1241, 2 ,1241, 2 , 0 , 0 , 0 ,,
       3       3
       0    1504
       3       3
       0    1504
Pier Skew, UpSta & Num, DnSta & Num=  ,1383, 2 ,1383, 2 , 0 , 0 , 0 ,,
       3       3
       0    1504
       3       3
       0    1504
BR Coef=-1 , 1 , 0 ,0.95, 0 ,,,0.8,0,0.6,0,
WSPro=,,,, 1 ,,,, 0 ,,,, 0 ,,,,-1 ,-1 ,-1 , 0 , 0 , 0 , 0 , 0
BR U #Sta/Elev= 30
       0 1568.08    81.6 1537.16   176.9 1519.18   209.8  1521.9   499.3 1510.87
   604.3 1498.59   640.7 1503.02   706.7 1503.34   763.1  1494.8   914.9 1495.59
   966.2 1483.29  992.17 1480.28 1054.26  1476.1 1078.86  1482.3 1085.48  1485.3
 1138.16  1486.5 1155.86  1479.3 1324.58 1473.94 1426.41 1476.72 1446.181480.808
  1595.9 1507.31  1718.6 1514.55  1765.6 1516.82    1820  1513.6    1876 1514.94
  1958.9 1520.02  2076.2 1537.77  2134.9 1552.85  2148.7 1562.27  2198.4 1585.74
BR U #Mann= 7
       0     .04  992.17    .045 1078.86     .08 1155.86     .04 1446.18     .04
  1718.6    .016    1876     .04
BR D #Sta/Elev= 30
       0  1573.3    63.3  1548.9    96.2 1542.84   122.5 1542.08   191.6 1535.95
   336.3 1515.71   543.8 1513.89   648.8  1508.8   751.2 1497.53   923.2 1498.34
  987.06 1494.12 1025.64 1480.24 1074.26  1476.1 1098.86  1482.3 1105.48  1485.3
 1158.16  1486.5 1175.86  1479.3 1344.58 1473.94 1446.41 1476.72  1462.5 1481.43
  1465.4  1496.8  1466.9 1497.38  1553.1 1498.74  1717.9 1510.76    1774  1517.1
  1855.8 1513.92  2019.6 1519.23  2084.7 1529.22  2123.7 1544.91  2198.4 1582.54
BR D #Mann= 9
       0      .1   122.5     .04 1025.64     .04 1098.86     .08 1175.86    .045
  1462.5     .04  1717.9    .016  1855.8     .04  2123.7      .1
BC Design=,, 0 ,, 0 ,,,,,,
BC Use User HTab Curves=0
BC User HTab FreeFlow(D)= 0

Type RM Length L Ch R = 1 ,87668   ,885.5,883.6,889
BEGIN DESCRIPTION:
Channel burned from survey: 54089GRB042BU
END DESCRIPTION:
XS GIS Cut Line= 6
2040340.86050263235225.3580244782040292.60338131235902.997089148
 2040273.1506643 236036.940390812040275.75630213236128.135746479
2040423.32556081 236675.010636972040649.01999131237365.114899814
#Sta/Elev= 30
       0  1573.3    63.3  1548.9    96.2 1542.84   122.5 1542.08   191.6 1535.95
   336.3 1515.71   543.8 1513.89   648.8  1508.8   751.2 1497.53   923.2 1498.34
  987.06 1494.12 1025.64 1480.24 1074.26  1476.1 1098.86  1482.3 1105.48  1485.3
 1158.16  1486.5 1175.86  1479.3 1344.58 1473.94 1446.41 1476.72  1462.5 1481.43
  1465.4  1496.8  1466.9 1497.38  1553.1 1498.74  1717.9 1510.76    1774  1517.1
  1855.8 1513.92  2019.6 1519.23  2084.7 1529.22  2123.7 1544.91  2198.4 1582.54
#Mann= 9 ,-1 , 0
       0      .1       0   122.5     .04       0 1025.64    .045       0
 1098.86     .08       0 1175.86    .045       0  1462.5     .04       0
  1717.9    .016       0  1855.8     .04       0  2123.7      .1       0
#XS Ineff= 3 ,-1
       0     750    1520     750     919  1501.7    1479    2000    1505
Permanent Ineff=
       F       F       F
#Block Obstruct= 11 ,-1
  165.72  227.14 1559.06  284.43  376.51 1542.35   425.1  459.74 1535.09
  523.21  583.25 1534.34  615.21  655.54 1529.64  721.05  747.13 1519.48
  773.83   814.7    1517 1490.31 1539.04 1518.87 1588.33 1657.02 1527.63
 1895.75 1941.12 1535.61  2067.8 2086.23 1549.65
Bank Sta=1175.86,1462.5
XS Rating Curve= 0 ,0
Exp/Cntr=0.5,0.3

Type RM Length L Ch R = 1 ,86785   ,929.5,1270.8,1405.5
BEGIN DESCRIPTION:
Channel burn based on effective XS CN
END DESCRIPTION:
XS GIS Cut Line= 2
2039299.17820281235849.393193722 2039780.9488928237746.094452813
#Sta/Elev= 30
       0 1606.67      78 1554.83   159.2 1507.17   169.4 1502.69   320.4 1493.29
   480.8 1495.67   501.2 1481.54   619.6 1479.25   626.3 1484.02   633.1 1489.41
     650 1491.62   704.2 1492.62  721.151479.802   723.2 1479.48   724.5  1474.1
  1008.9  1474.1  1009.1 1479.42 1011.081480.199    1019 1486.59  1030.3 1490.34
  1056.2 1491.63  1076.6 1496.74    1239 1511.39  1374.4 1511.91  1394.6 1515.56
  1506.5 1517.39    1740 1522.73    1784 1527.09  1895.7 1550.37  1956.9 1555.67
#Mann= 8 ,-1 , 0
       0      .1       0   159.2     .04       0   501.2    .045       0
   626.3     .08       0  721.15    .045       0 1011.08     .04       0
  1394.6    .016       0  1506.5     .04       0
#Block Obstruct= 10 ,-1
  223.22  276.42 1520.41  660.68  712.76 1512.35 1139.24 1175.15 1523.85
 1219.73 1267.13  1532.2 1294.05  1330.6 1533.45  1576.5 1629.23 1540.58
 1653.05 1690.31 1541.12 1744.64 1778.44 1546.53  1800.8 1828.55  1557.5
 1916.05 1956.93 1575.67
Bank Sta=721.15,1011.08
XS Rating Curve= 0 ,0
Exp/Cntr=0.3,0.1

Type RM Length L Ch R = 1 ,85514   ,698.8,595.4,418.8
BEGIN DESCRIPTION:
Channel burn based on effective XS CM
END DESCRIPTION:
Node Name=Y
XS GIS Cut Line= 3
2038629.44084595235804.033508682 2038076.0940828237223.804808863
2038156.18374589238079.308028202
#Sta/Elev= 30
       0 1587.83   122.8 1561.32     246 1514.31   513.6 1492.19   527.2 1491.83
     584 1479.62   587.6    1474   823.5    1474     827 1479.08   838.8 1486.43
   862.2 1487.91   914.9 1478.41  1041.8 1484.81  1336.6 1480.69  1398.8 1478.62
  1450.2  1513.1  1462.1 1514.62  1527.5 1514.85  1550.5 1514.93  1577.1 1501.86
  1609.8 1502.84  1741.7 1514.31    1801 1525.44  1817.4 1516.16  1866.9 1517.48
  1886.6  1531.5  1936.1 1530.48    1946 1535.59  2189.8 1552.95    2383 1607.38
#Mann= 10 ,-1 , 0
       0     .04       0   513.6    .016       0   527.2     .08       0
     584    .045       0     827     .08       0  1336.6    .045       0
  1398.8     .08       0  1462.1    .016       0  1527.5      .1       0
    1946     .04       0
#XS Ineff= 2 , 0
       0                    1500       0    1520
Permanent Ineff=
       F       F
#Block Obstruct= 8 ,-1
  301.66   327.3 1526.17  336.45  377.45 1523.79  391.87  414.79 1522.61
   422.2  456.48 1520.65  490.92  501.85 1515.53  1974.4 2019.55 1562.97
 2041.74 2057.18 1566.16 2099.95  2157.7 1570.62
Bank Sta=584,827
XS Rating Curve= 0 ,0
Exp/Cntr(USF)=0,0
Exp/Cntr=0.3,0.1

Type RM Length L Ch R = 1 ,84919   ,263.9,479.4,617.4
BEGIN DESCRIPTION:
Channel burn based on effective XS CL
END DESCRIPTION:
XS GIS Cut Line= 5
2037866.22276112235549.7852327732037780.70884358 235770.94191607
2037763.01630891236918.0079134392037763.01630891237114.591631926
2037883.15080354238130.274177439
#Sta/Elev= 30
       0 1524.05   345.3  1501.5   781.5 1499.62   801.3 1498.87   817.7 1485.08
   850.5 1479.24   857.1  1474.1  1306.6  1474.1  1309.9 1478.45  1326.3 1486.88
  1365.7 1489.06  1388.7 1486.95  1408.8 1478.31  1467.4 1478.17  1484.2  1494.6
  1513.3 1514.19  1621.9 1514.29  1638.4 1510.73  1674.7 1486.62  1694.6 1484.47
  1757.3 1495.78  1767.2 1501.12    1797  1500.5  1897.8 1513.87  2094.3 1512.88
  2212.4  1519.1  2367.5 1519.72  2447.8 1530.63  2515.3  1547.6  2603.7 1580.88
#Mann= 7 ,-1 , 0
       0     .04       0   781.5     .08       0   850.5    .045       0
  1309.9     .08       0  1513.3    .016       0  1621.9     .04       0
  1897.8     .08       0
#XS Ineff= 2 , 0
       0                    1565       0    1520
Permanent Ineff=
       F       F
#Block Obstruct= 3 ,-1
 2160.02 2199.28 1538.07 2207.12 2229.32  1539.1 2288.43  2317.4 1539.18
Bank Sta=850.5,1309.9
XS Rating Curve= 0 ,0
Exp/Cntr(USF)=0,0
Exp/Cntr=0.3,0.1

Type RM Length L Ch R = 1 ,84439   ,534.4,799.7,938.8
BEGIN DESCRIPTION:
Channel burn based on effective XS CK
END DESCRIPTION:
XS GIS Cut Line= 3
2037831.63317653235520.7579250382037063.40374186236940.028708537
2036577.29283745237899.229874124
#Sta/Elev= 30
       0 1522.95   191.8 1507.72   362.6 1500.45   882.5 1499.14     911 1493.99
   937.1 1478.14   940.9  1474.2  1231.9  1474.2  1235.6 1479.44  1247.8 1485.02
  1470.6 1490.38  1508.5 1513.45    1551 1515.48  1660.2 1515.17  1678.3 1503.92
  1700.5    1493  1973.9 1483.13  1998.3 1494.41  2020.7 1513.76  2049.6 1516.34
  2083.7 1537.59  2134.7  1538.8  2163.6  1560.1  2193.6  1583.7  2241.4 1596.65
  2351.7 1636.35  2481.6 1690.99  2534.7 1708.05  2576.8 1717.51  2689.2 1727.67
#Mann= 8 ,-1 , 0
       0     .04       0     911     .08       0   937.1    .045       0
  1235.6     .08       0    1551    .016       0  1678.3      .1       0
  2163.6    .016       0  2241.4      .1       0
#XS Ineff= 2 , 0
                         1585.35         1518.47
Permanent Ineff=
       F       F
#Block Obstruct= 1 ,-1
 1371.61 1400.94 1508.98
Bank Sta=937.1,1235.6
XS Rating Curve= 0 ,0
Exp/Cntr=0.3,0.1

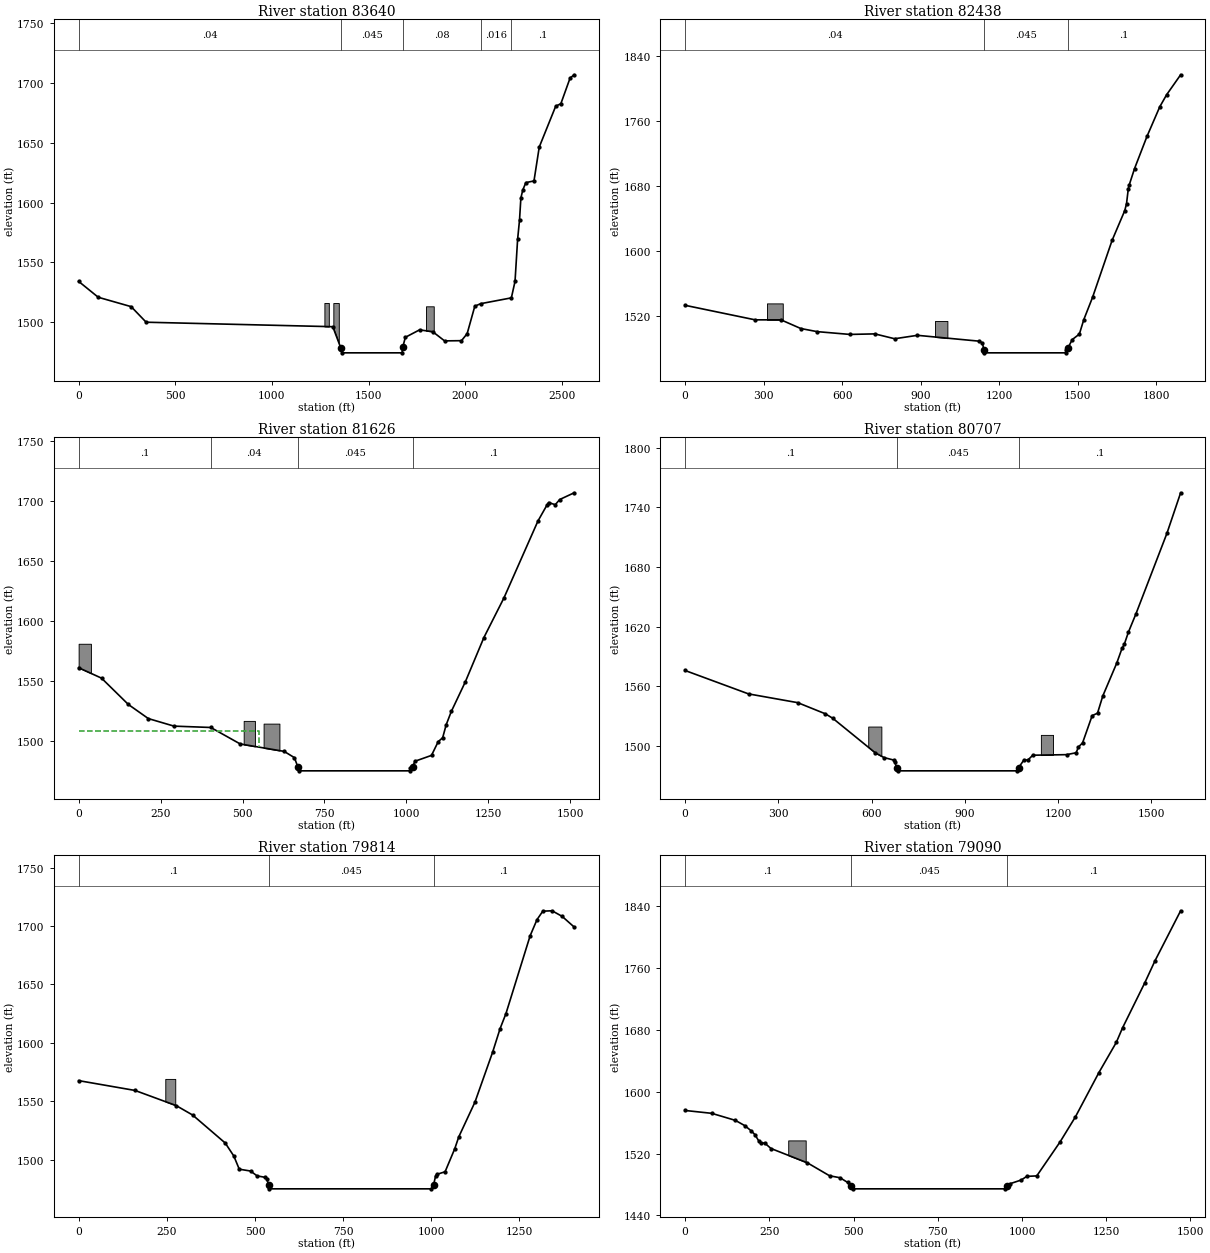
Type RM Length L Ch R = 1 ,83640   ,718.6,1201.6,1389.2
BEGIN DESCRIPTION:
Channel burn based on effective XS CJ
END DESCRIPTION:
XS GIS Cut Line= 3
2037793.10181864 235337.240346642036274.00446314236409.289055556
 2035718.4491438236843.316730812
#Sta/Elev= 30
       0 1534.19   101.6 1520.89   271.8 1513.05   349.4 1500.02  1315.2 1496.27
    1357 1478.32  1361.7  1474.4  1673.7  1474.4  1677.2 1479.05  1690.7  1487.4
    1764 1493.61  1832.3 1492.09  1893.7  1484.4  1981.2 1484.58  2010.5 1490.46
  2050.1 1513.41  2079.8 1515.51  2239.3  1520.4  2258.2 1534.15  2271.6 1569.32
  2281.5 1585.55  2288.5 1603.95  2298.3 1610.58  2314.2 1616.84  2356.3 1618.22
  2383.6  1646.6  2468.8 1680.78  2495.5 1682.89  2543.2 1704.35  2564.3 1707.05
#Mann= 5 ,-1 , 0
       0     .04       0    1357    .045       0  1677.2     .08       0
  2079.8    .016       0  2239.3      .1       0
#Block Obstruct= 3 ,-1
  1271.8 1294.71 1516.14 1318.03 1346.37 1516.07 1797.46  1837.6 1513.34
Bank Sta=1357,1677.2
XS Rating Curve= 0 ,0
Exp/Cntr=0.3,0.1

Type RM Length L Ch R = 1 ,82438   ,818,812.3,809.9
BEGIN DESCRIPTION:
Channel burn based on effective XS CI
END DESCRIPTION:
Node Name=X
XS GIS Cut Line= 3
2037754.03923272 235298.177760722036812.19892481235237.413774639
2035896.40023147234990.017943978
#Sta/Elev= 30
       0 1533.07   267.6  1515.2   366.2 1515.19   441.8 1504.52   504.1  1500.7
   629.2 1497.26   724.6 1497.92   800.2 1491.94   887.2 1496.15  1121.6    1489
  1135.2  1486.9  1141.1 1478.44    1142  1474.6  1454.6  1474.6  1455.5 1477.58
  1461.4 1480.21  1478.4 1490.88  1505.6 1497.64  1522.6 1515.48  1555.9 1542.78
  1630.8 1613.12    1679 1649.58  1685.7 1657.95  1692.5 1676.42  1695.9 1681.03
  1716.3 1701.24  1763.9 1740.92  1812.7 1777.31  1838.7 1792.06  1892.4  1816.7
#Mann= 3 ,-1 , 0
       0     .04       0  1141.1    .045       0  1461.4      .1       0
#Block Obstruct= 2 ,-1
  312.61     373 1535.44  954.33 1001.64 1513.83
Bank Sta=1141.1,1461.4
XS Rating Curve= 0 ,0
Exp/Cntr=0.3,0.1

Type RM Length L Ch R = 1 ,81626   ,907.5,918.2,921.2
BEGIN DESCRIPTION:
Channel burn based on effective XS CH
END DESCRIPTION:
XS GIS Cut Line= 2
2037554.38641681234603.7332834752036096.05304739234204.427651644
#Sta/Elev= 30
       0 1560.87    69.9 1552.16   151.7  1530.2   212.7 1518.42     291 1512.12
   403.2 1510.99     493 1497.24   627.1 1491.03   658.3 1485.82   668.5 1478.38
     671 1477.63   671.9  1474.8  1011.6  1474.8  1012.1 1477.34  1019.6 1478.16
  1025.7 1482.76  1076.7  1487.7  1097.1 1499.15  1110.7 1502.41  1121.6 1513.34
  1137.1 1524.34  1179.9 1549.07  1236.6 1586.09  1297.8 1619.18  1401.5 1683.34
  1429.8 1697.04  1433.9 1698.75  1454.3 1696.94  1467.9 1701.27    1512 1706.89
#Mann= 4 ,-1 , 0
       0      .1       0   403.2     .04       0   668.5    .045       0
  1019.6      .1       0
#XS Ineff= 2 , 0
          550.76 1508.04
Permanent Ineff=
       F       F
#Block Obstruct= 3 ,-1
       0    37.5 1580.87  503.61  537.91 1516.48  564.38  612.64 1514.21
Bank Sta=668.5,1019.6
XS Rating Curve= 0 ,0
Exp/Cntr=0.3,0.1

Type RM Length L Ch R = 1 ,80707   ,807.5,893.4,951
BEGIN DESCRIPTION:
Channel burn based on effective XS CG
END DESCRIPTION:
XS GIS Cut Line= 2
2037875.56720489233774.7401908042036352.12963498233305.990472138
#Sta/Elev= 30
       0 1575.85     204 1552.31   362.4 1543.48   451.2 1532.27   475.2 1527.72
   611.7    1493     640 1488.23   670.8 1485.76   674.3 1484.03   681.1 1477.28
   685.2  1474.9  1068.5  1474.9  1072.5 1478.02  1088.9 1485.42  1103.4 1486.05
  1118.3 1490.62  1226.9 1491.18  1257.8 1493.09  1265.3 1498.96  1278.4 1502.99
  1309.3 1530.43  1326.5  1532.9  1343.6 1550.29  1388.3 1583.22  1405.4 1598.12
  1412.5 1602.07    1426 1614.49  1450.1  1632.8  1549.6 1713.68  1593.9 1754.64
#Mann= 3 ,-1 , 0
       0      .1       0   681.1    .045       0  1072.5      .1       0
#Block Obstruct= 2 ,-1
  589.01  631.26 1519.46 1144.38 1183.47 1511.06
Bank Sta=681.1,1072.5
XS Rating Curve= 0 ,0
Exp/Cntr=0.3,0.1

Type RM Length L Ch R = 1 ,79814   ,704.5,723.8,735.5
BEGIN DESCRIPTION:
Channel burn based on effective XS CF
END DESCRIPTION:
Node Name=W
XS GIS Cut Line= 2
2038018.79624914233119.3582994792036833.90032497232364.150164232
#Sta/Elev= 30
       0 1567.64   159.9 1559.23   276.6 1546.27   323.3 1538.17   415.7 1514.22
     440 1503.11   455.5 1491.81   487.4 1490.25   506.1 1486.08   529.5 1484.82
   533.4 1483.48   539.2 1478.04   541.1    1475  1000.3    1475  1006.3 1478.34
  1012.1 1485.83  1015.8 1487.41  1039.1 1489.62  1066.4 1509.27    1078 1519.57
  1123.8 1549.26  1173.7 1591.84    1195 1612.13  1211.7 1625.07  1280.3 1691.71
  1299.8 1705.51  1316.2 1712.71  1342.4 1713.04  1370.9 1708.27  1405.1 1699.12
#Mann= 3 ,-1 , 0
       0      .1       0   539.2    .045       0  1006.3      .1       0
#Block Obstruct= 1 ,-1
   245.7  273.96  1569.1
Bank Sta=539.2,1006.3
XS Rating Curve= 0 ,0
Exp/Cntr=0.3,0.1

Type RM Length L Ch R = 1 ,79090   ,847.2,847.6,856.5
BEGIN DESCRIPTION:
Channel burn based on effective XS CE
END DESCRIPTION:
XS GIS Cut Line= 2
2038374.69908063232542.1015799792037181.12272763231682.726330221
#Sta/Elev= 30
       0  1575.6    79.1 1571.91   149.2 1562.82   177.4 1555.95     196 1549.36
   207.2 1544.45   218.4 1536.42     224 1533.97   236.8 1533.35   254.9 1526.49
   363.1 1507.96   428.9 1491.24   459.9 1488.74   482.3  1482.7   492.3 1477.78
   499.2  1474.4   948.3  1474.4   956.4 1477.85   965.2 1481.13   997.7 1485.81
  1014.1  1490.5  1043.8 1491.11  1112.9 1534.94  1158.5 1567.35    1228 1624.39
  1279.8 1663.48  1298.5 1682.38  1364.4 1740.47  1394.9 1769.08  1470.8 1833.47
#Mann= 3 ,-1 , 0
       0      .1       0   492.3    .045       0   956.4      .1       0
#Block Obstruct= 1 ,-1
  306.05  357.92 1536.95
Bank Sta=492.3,956.4
XS Rating Curve= 0 ,0
Exp/Cntr=0.3,0.1

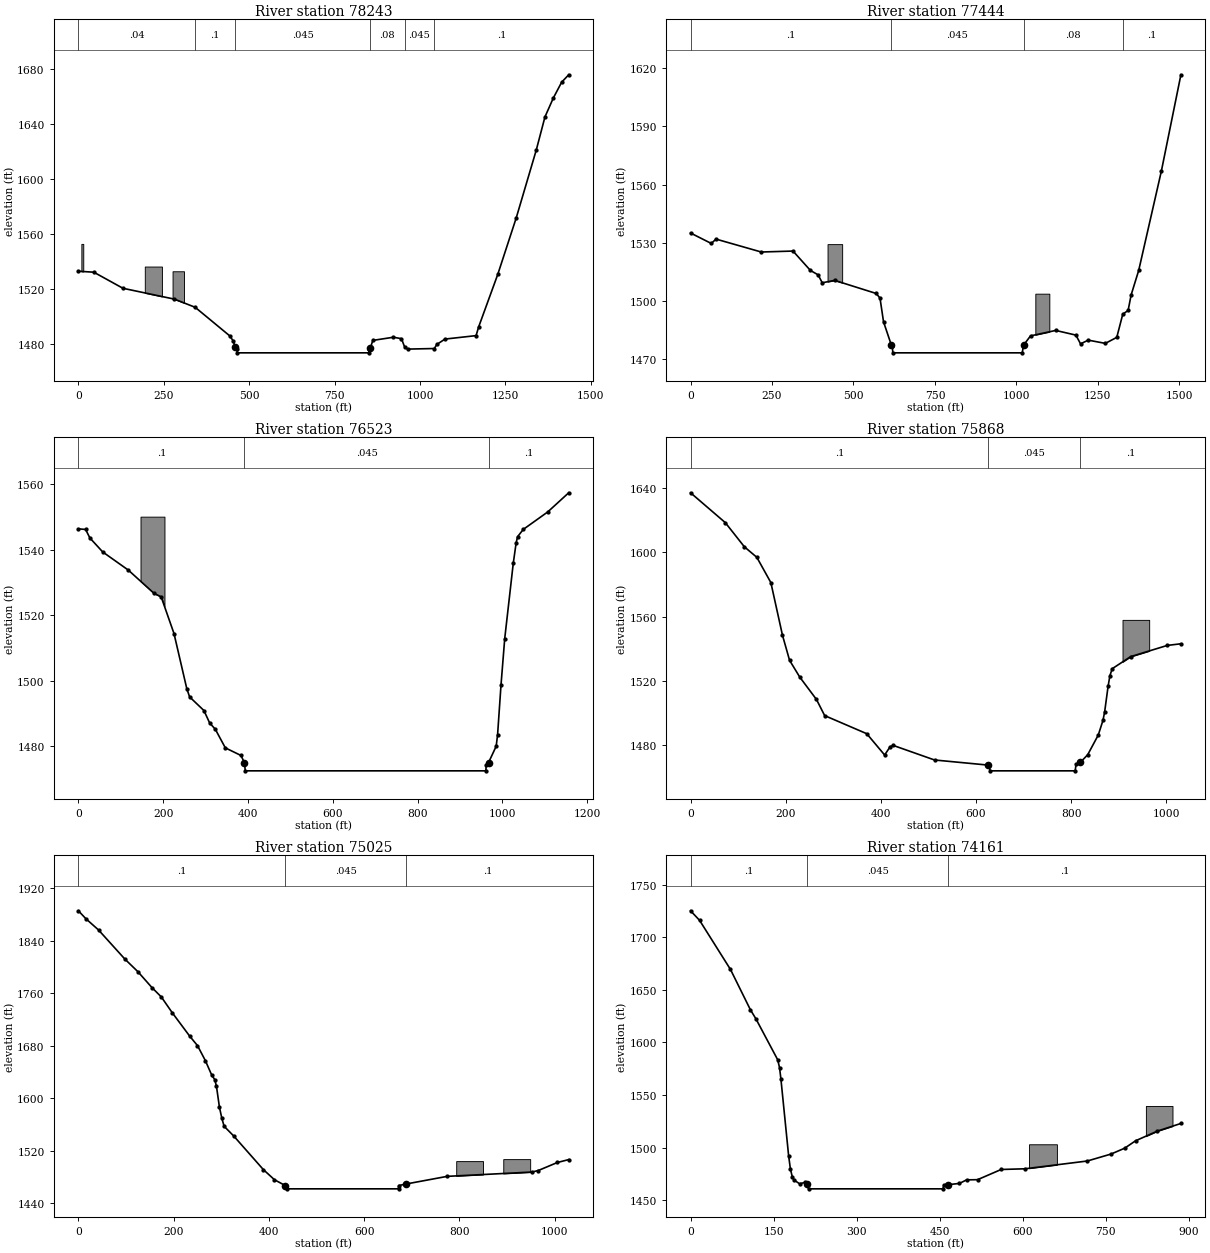
Type RM Length L Ch R = 1 ,78243   ,752.4,798.9,883.6
BEGIN DESCRIPTION:
Channel burn based on effective XS CD
END DESCRIPTION:
XS GIS Cut Line= 2
2038839.10858488231838.9763458072037680.25460339230992.622395471
#Sta/Elev= 30
       0 1533.25    45.2 1532.54   130.5 1520.84   281.1 1512.95   341.8 1507.02
   443.1 1486.22   452.5 1482.79   459.5 1477.92   463.6 1476.66     465  1473.9
   849.6  1473.9   851.6 1476.74     854 1477.18   861.8 1482.95     922 1485.24
   945.5  1484.2   954.5 1478.37   963.3 1476.62  1041.8 1477.04  1048.8 1479.97
    1073 1483.91  1163.9 1486.42  1171.4 1492.73  1227.3 1530.88  1281.3 1571.93
    1340 1621.31  1365.5 1645.48  1389.9 1659.17  1414.3 1670.69    1435  1676.1
#Mann= 6 ,-1 , 0
       0     .04       0   341.8      .1       0   459.5    .045       0
     854     .08       0   954.5    .045       0  1041.8      .1       0
#Block Obstruct= 3 ,-1
    8.78    14.3 1553.12  194.38  244.53 1536.65  275.65  309.04 1533.22
Bank Sta=459.5,854
XS Rating Curve= 0 ,0
Exp/Cntr=0.3,0.1

Type RM Length L Ch R = 1 ,77444   ,782.4,920.4,1100.4
BEGIN DESCRIPTION:
Channel burn based on effective XS CC
END DESCRIPTION:
XS GIS Cut Line= 2
2039364.28240331231430.9902851432038339.97670914230328.559747234
#Sta/Elev= 30
       0 1535.01    63.6 1529.62    78.1 1531.87   216.9 1525.21   314.4  1525.7
   367.8 1515.71   391.4 1513.43   404.1 1509.34   442.1 1510.58   569.7 1503.82
   581.4 1501.44   592.2  1489.2   616.2 1477.21   619.1 1476.54   620.8  1473.2
  1017.8  1473.2  1022.1  1477.2  1043.3 1481.94  1120.6 1484.76  1182.6 1482.34
  1196.8 1477.84  1220.4 1479.75  1272.9 1478.08    1308 1481.18  1326.4 1493.14
  1342.8 1495.06  1352.1 1503.08  1375.3 1515.72  1444.9 1566.98  1504.8 1616.63
#Mann= 4 ,-1 , 0
       0      .1       0   616.2    .045       0  1022.1     .08       0
  1326.4      .1       0
#Block Obstruct= 2 ,-1
  420.38  465.24 1529.28 1058.07 1101.02 1503.72
Bank Sta=616.2,1022.1
XS Rating Curve= 0 ,0
Exp/Cntr=0.3,0.1

Type RM Length L Ch R = 1 ,76523   ,707.1,655,654.2
BEGIN DESCRIPTION:
Channel burn based on effective XS CB
END DESCRIPTION:
Node Name=V
XS GIS Cut Line= 2
2039772.26846397231079.4276680652039520.53241889229950.955515563
#Sta/Elev= 30
       0 1546.33    17.1 1546.14    27.1 1543.55    57.4 1539.28   117.9 1533.73
   178.4 1526.64   195.2 1525.58   225.5 1514.38   255.7 1497.54   262.4 1495.04
   296.1 1490.89   309.5 1487.12     323 1485.17   346.5 1479.51   383.5 1477.18
   391.7 1474.93   393.5  1472.5   960.9  1472.5   961.6 1474.41   967.1    1475
   985.2 1480.01   988.5 1483.54   996.6 1498.77  1005.3 1512.82  1025.5 1535.86
  1032.2 1542.01  1035.6 1543.92    1049 1546.15  1106.6 1551.47  1156.2 1557.33
#Mann= 3 ,-1 , 0
       0      .1       0   391.7    .045       0   967.1      .1       0
#Block Obstruct= 1 ,-1
  146.52  203.01 1550.05
Bank Sta=391.7,967.1
XS Rating Curve= 0 ,0
Exp/Cntr=0.3,0.1

Type RM Length L Ch R = 1 ,75868   ,1034.7,843.5,564.9
BEGIN DESCRIPTION:
Channel burn based on effective XS CA
END DESCRIPTION:
XS GIS Cut Line= 2
2040579.56015646230944.8790526392040132.51150988230016.059716061
#Sta/Elev= 30
       0 1636.97    73.1 1618.38   113.1 1603.37   139.3 1596.83   168.8 1581.12
   193.2 1548.39   208.1 1532.77   229.6 1522.29   264.7 1508.39   281.9 1498.36
   370.4  1487.1     408 1473.84   419.5 1478.99   426.2  1479.8   512.9 1470.75
     626 1467.56   630.1    1464   808.6    1464   810.4 1468.17   819.5 1469.29
   834.9 1474.03   857.1 1486.28     867  1495.4   870.5 1500.67   877.7 1516.49
   881.6 1523.25   886.5 1527.55   925.1 1535.04  1002.1 1542.01  1030.8 1543.04
#Mann= 3 , 0 , 0
       0      .1       0     626    .045       0   819.5      .1       0
#Block Obstruct= 1 ,-1
  908.07   964.1 1557.91
Bank Sta=626,819.5
XS Rating Curve= 0 ,0
Exp/Cntr=0.3,0.1

Type RM Length L Ch R = 1 ,75025   ,1083.7,863.6,438.1
BEGIN DESCRIPTION:
Channel burn based on effective XS BZ
END DESCRIPTION:
XS GIS Cut Line= 2
2041321.74764848 229655.81667015 2040297.4419543229759.983456567
#Sta/Elev= 30
       0 1885.36    15.9 1873.18    42.3 1856.18    97.8 1811.72   124.8 1792.81
   154.4 1768.56   174.2 1754.22   197.3 1730.04   233.6 1694.72   250.1 1680.19
   266.6 1657.43   279.8 1635.63   286.4 1628.39     290 1618.06   296.2 1586.51
   301.3 1569.37   306.1 1557.35   325.9 1542.86   388.6 1491.34   411.7 1476.09
   434.7 1467.06     438  1462.2   672.2  1462.2   672.5 1467.19   688.7 1469.64
   774.4 1481.19   952.5 1487.77   965.5 1490.03  1005.8 1502.29  1029.6  1506.7
#Mann= 3 ,-1 , 0
       0      .1       0   434.7    .045       0   688.7      .1       0
#Block Obstruct= 2 ,-1
  793.38  849.65 1504.39  892.18  948.69 1507.43
Bank Sta=434.7,688.7
XS Rating Curve= 0 ,0
Exp/Cntr=0.3,0.1

Type RM Length L Ch R = 1 ,74161   ,676.4,653.9,613.2
BEGIN DESCRIPTION:
Channel burn based on effective XS BY
END DESCRIPTION:
XS GIS Cut Line= 2
 2040171.5740958228874.5665922312040180.25452463229759.983456567
#Sta/Elev= 30
       0 1725.13    16.3 1716.04    72.1 1669.36   108.2 1630.93     118 1622.48
   157.4  1583.5   160.7 1576.05   163.1 1565.63   177.1 1492.31   180.3 1479.78
   183.6 1472.58   186.9 1469.29   196.8 1465.74   206.6 1466.97   209.5  1465.7
   213.2  1460.9     456  1460.9   457.2 1464.65   465.8 1464.91   485.5 1466.03
   498.6 1469.44   518.3  1469.6   560.9 1479.29   603.8 1479.95   716.5 1487.35
   759.4 1493.97     784 1499.53   803.7 1506.58   843.1 1515.79   885.5 1523.03
#Mann= 3 ,-1 , 0
       0      .1       0   209.5    .045       0   465.8      .1       0
#Block Obstruct= 2 ,-1
  611.25  661.59 1503.25  822.29  870.31 1539.67
Bank Sta=209.5,465.8
XS Rating Curve= 0 ,0
Exp/Cntr=0.3,0.1

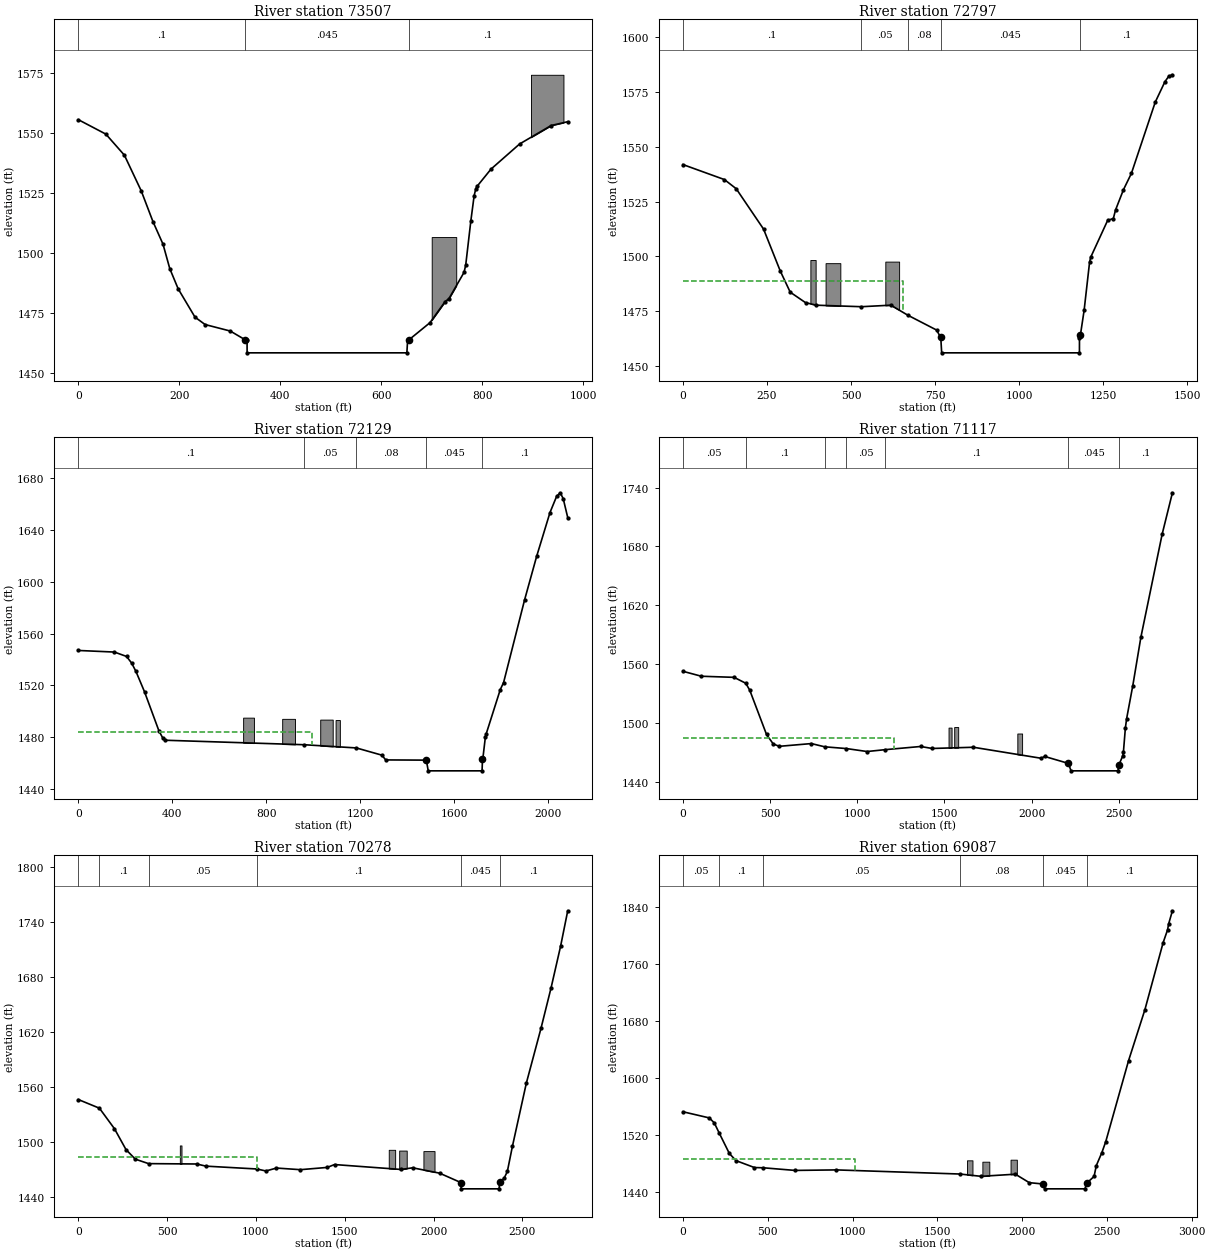
Type RM Length L Ch R = 1 ,73507   ,724.4,710.5,698.6
BEGIN DESCRIPTION:
Channel burn based on effective XS BX
END DESCRIPTION:
Node Name=U
XS GIS Cut Line= 2
2039464.10864723 228909.288963722039629.03941973229864.149914891
#Sta/Elev= 30
       0 1555.67    54.5 1549.66    91.2 1540.89   124.5 1526.06   147.8 1513.22
   167.7 1503.82   181.1 1493.65   197.7 1485.24     231 1473.46     251 1470.38
   300.9 1467.67     330 1464.08   334.1 1463.79   334.2  1458.6   650.5  1458.6
     652 1463.82   653.8 1463.88   696.3 1471.16   726.1 1479.92   733.7 1481.14
   763.7  1492.1     767 1495.11   777.2  1513.6   783.7 1524.03     787 1526.92
   790.3 1528.13     817 1535.07   873.7 1545.55   936.2 1553.24     969 1554.82
#Mann= 3 ,-1 , 0
       0      .1       0     330    .045       0   653.8      .1       0
#Block Obstruct= 2 ,-1
  699.68  748.23  1506.8  896.23  960.53 1574.36
Bank Sta=330,653.8
XS Rating Curve= 0 ,0
Exp/Cntr=0.3,0.1

Type RM Length L Ch R = 1 ,72797   ,635.2,667.4,643.5
BEGIN DESCRIPTION:
Channel burn based on effective XS BW
END DESCRIPTION:
XS GIS Cut Line= 4
2038899.27167601228610.1957630352038792.33933716228834.335034726
2038735.49654699228989.3608260872038960.63655706230007.379287228
#Sta/Elev= 30
       0  1541.9   123.1 1535.07   158.3 1530.89   239.7 1512.46   289.5  1493.3
     319 1483.68   364.5 1478.91   396.9 1477.74     531 1477.05   618.4 1477.75
   668.8 1473.18   754.7 1466.38   766.2 1463.12   766.9 1463.09   769.6    1456
  1179.5    1456  1179.6 1462.81  1182.4 1464.15  1193.4 1475.36  1209.7 1497.43
  1213.1 1499.65  1263.5 1516.46  1280.3 1517.29    1287 1521.22  1310.5 1530.45
  1334.1 1537.89  1405.2 1570.46  1433.8  1579.7  1444.9 1582.14  1456.1 1582.88
#Mann= 5 ,-1 , 0
       0      .1       0     531     .05       0   668.8     .08       0
   766.2    .045       0  1182.4      .1       0
#XS Ineff= 2 , 0
          654.42 1488.67
Permanent Ineff=
       F       F
#Block Obstruct= 3 ,-1
  378.98  394.63 1498.37   424.2  468.11 1496.92  601.94  642.99 1497.63
Bank Sta=766.2,1182.4
XS Rating Curve= 0 ,0
Exp/Cntr=0.3,0.1

Type RM Length L Ch R = 1 ,72129   ,364.5,1012.4,1185.9
BEGIN DESCRIPTION:
Channel burn based on effective XS BV
END DESCRIPTION:
XS GIS Cut Line= 5
2038845.39989281 228544.645688462038185.05163714229220.659306797
2038058.52094387229332.658491569 2038088.7806207229425.758428768
2038409.42112406230237.413932145
#Sta/Elev= 30
       0 1546.88   153.8 1545.64   205.5 1542.24   227.2 1537.08   245.5 1530.63
   281.9 1514.91   342.9 1484.85   358.6 1479.46   371.1 1477.38   962.2 1473.91
  1184.2 1471.43  1292.9 1465.84  1309.3 1462.15  1479.9 1461.99  1482.4 1461.96
  1490.4  1453.7  1719.7  1453.7  1721.5 1462.64  1723.3 1463.57  1733.8 1479.86
  1737.4 1482.37  1797.2 1516.56  1811.4 1522.07    1901 1586.14  1952.5 1619.93
    2009 1653.64  2037.2 1666.15  2052.8 1668.94  2065.4 1664.37  2084.6 1649.77
#Mann= 5 ,-1 , 0
       0      .1       0   962.2     .05       0  1184.2     .08       0
  1479.9    .045       0  1721.5      .1       0
#XS Ineff= 2 , 0
          995.77 1483.61
Permanent Ineff=
       F       F
#Block Obstruct= 4 ,-1
     702     748 1494.88  868.31  922.78 1493.94 1030.32 1083.55 1493.36
  1095.8 1113.99 1493.01
Bank Sta=1479.9,1721.5
XS Rating Curve= 0 ,0
Exp/Cntr=0.3,0.1

Type RM Length L Ch R = 1 ,71117   ,282.6,839.1,945.9
BEGIN DESCRIPTION:
Channel burn based on effective XS BU
END DESCRIPTION:
XS GIS Cut Line= 4
 2038954.7277583228436.102809914 2037837.6388387229124.388290362
2037565.56857486229459.2439997012037003.17131189230363.282118723
#Sta/Elev= 30
       0 1552.64   105.4 1547.61   293.2 1546.49     360 1540.47   382.9 1533.45
   479.2 1488.21   517.8 1478.52   552.5 1476.12   736.7 1478.92     813 1475.62
   937.8 1473.83  1056.2 1470.81  1158.8 1472.68  1363.5 1475.95  1429.7 1473.92
  1666.4 1475.16  2055.6 1463.91  2074.9 1465.81    2212 1458.66  2226.4  1451.1
  2496.1  1451.1    2501 1457.19  2524.2 1466.65    2527  1469.9  2538.4 1494.75
  2545.6 1504.35  2581.1 1538.12  2627.4 1587.43  2749.4 1692.51  2808.3  1734.8
#Mann= 7 ,-1 , 0
       0     .05       0     360      .1       0     813    .016       0
   937.8     .05       0  1158.8      .1       0    2212    .045       0
    2501      .1       0
#XS Ineff= 2 , 0
         1208.45 1485.05
Permanent Ineff=
       F       F
#Block Obstruct= 3 ,-1
 1523.69 1541.12 1495.21 1556.07  1579.1 1495.77  1918.4 1945.75 1489.19
Bank Sta=2212,2501
XS Rating Curve= 0 ,0
Exp/Cntr=0.3,0.1

Type RM Length L Ch R = 1 ,70278   ,754.9,1190.5,1270.2
BEGIN DESCRIPTION:
Channel burn based on effective XS BT
END DESCRIPTION:
Node Name=T
XS GIS Cut Line= 3
 2038741.2852943228363.6505886352037249.24706013229118.600660818
2036252.30306298229542.969454899
#Sta/Elev= 30
       0 1545.96   118.8 1536.51   203.4 1514.16   268.6 1491.34     321 1480.95
   395.5 1476.09     667 1475.69   718.1 1473.35  1004.9 1470.25  1056.4 1468.08
  1115.8 1471.26  1250.1 1469.49  1401.4 1471.94  1442.5 1475.08  1816.7 1469.74
  1882.5 1471.53  2034.2 1465.69  2154.5 1455.39  2155.2 1455.35  2155.4  1448.6
  2369.4  1448.6  2372.3  1455.6  2397.8 1460.25  2415.7 1467.56  2444.2 1494.91
  2522.8 1563.96  2605.4 1623.77  2661.8 1667.64  2715.8 1713.37  2755.7 1751.74
#Mann= 6 ,-1 , 0
       0     .05       0   118.8      .1       0   395.5     .05       0
  1004.9      .1       0  2154.5    .045       0  2372.3      .1       0
#XS Ineff= 2 , 0
         1007.32 1482.98
Permanent Ineff=
       F       F
#Block Obstruct= 4 ,-1
  571.58  580.91  1495.9 1747.92 1783.92 1491.14 1806.62 1849.11 1490.31
 1943.17 2005.65 1489.75
Bank Sta=2154.5,2372.3
XS Rating Curve= 0 ,0
Exp/Cntr=0.3,0.1

Type RM Length L Ch R = 1 ,69087   ,1035.9,1169.2,1198.6
BEGIN DESCRIPTION:
Channel burn based on effective XS BS
END DESCRIPTION:
XS GIS Cut Line= 3
2038727.69171953 228189.210837282037823.41665776 228240.12117644
2035844.31700231 228158.42071481
#Sta/Elev= 30
       0 1552.99     155 1544.41   184.5 1537.44   213.4  1523.3   273.3 1494.63
   312.7 1484.58   421.1 1474.94   474.6 1474.55     661 1470.89   904.2 1471.61
  1633.2 1465.84  1757.9 1462.62  1960.2 1465.61  2042.4 1453.75  2125.7 1451.84
    2129 1451.88  2132.3  1445.1    2372  1445.1  2378.5 1453.08  2385.1 1453.91
  2424.5 1462.47  2437.6  1477.6  2470.5 1495.87  2493.5  1511.3  2628.1 1624.75
    2724 1695.74  2831.7 1789.73  2857.6 1807.47  2864.4 1816.17  2886.5 1834.41
#Mann= 6 ,-1 , 0
       0     .05       0   213.4      .1       0   474.6     .05       0
  1633.2     .08       0  2125.7    .045       0  2385.1      .1       0
#XS Ineff= 2 , 0
         1014.08 1487.31
Permanent Ineff=
       F       F
#Block Obstruct= 3 ,-1
 1674.84 1707.28 1485.02 1765.71 1806.62 1483.11 1931.89 1968.98 1485.92
Bank Sta=2125.7,2385.1
XS Rating Curve= 0 ,0
Exp/Cntr=0.3,0.1