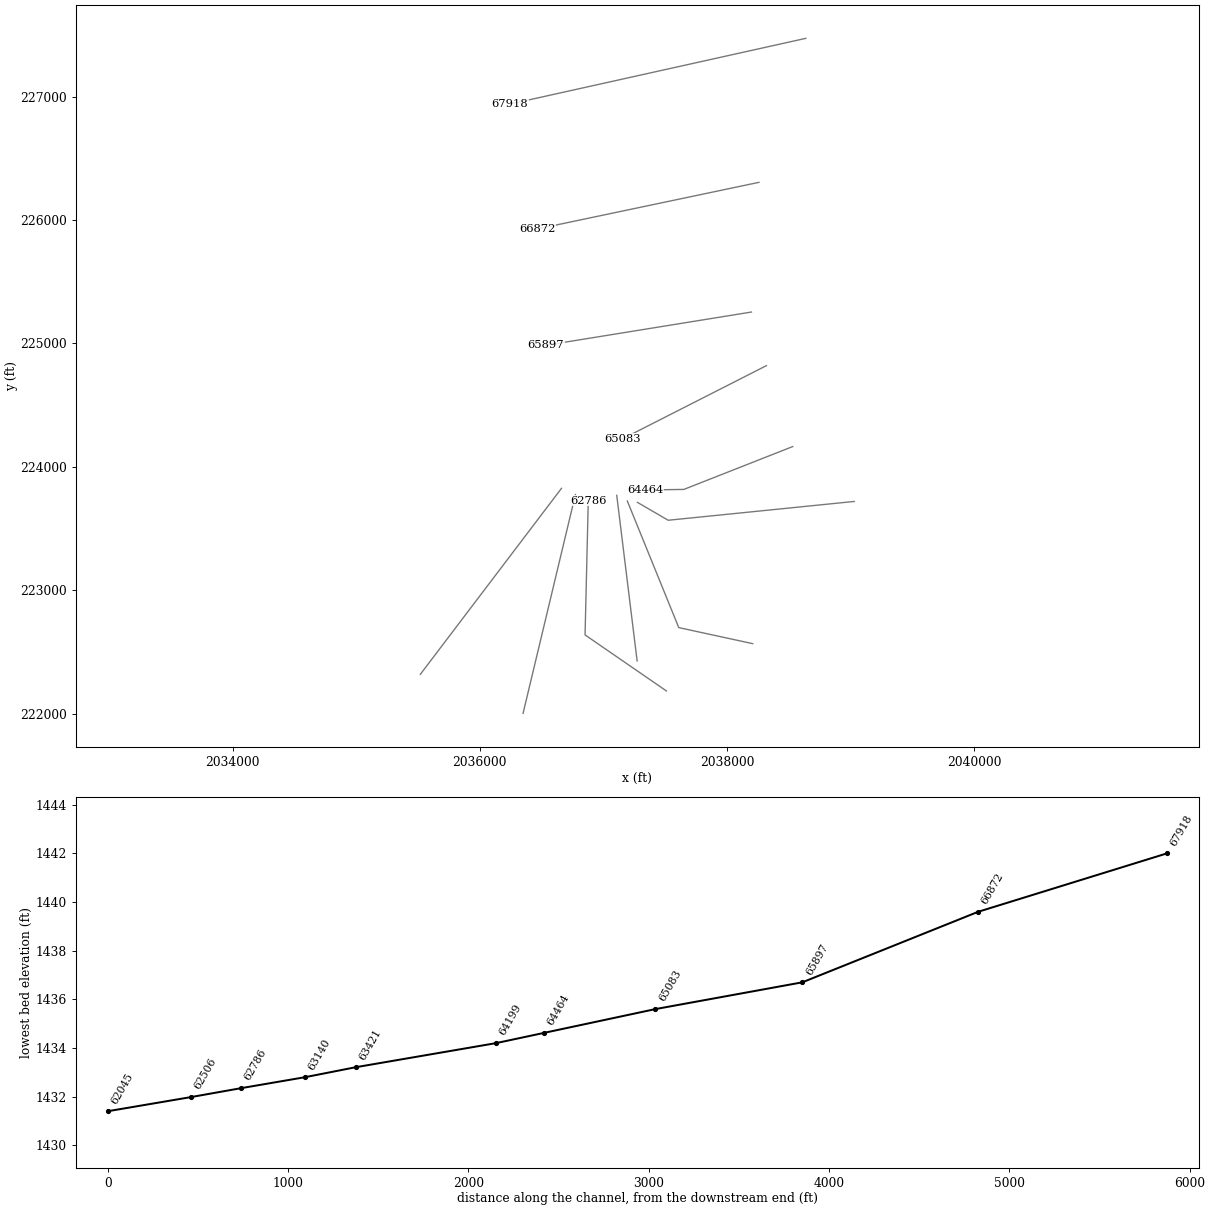
HEC-RAS study GREENBRRV.prj: GREENBRRV

--- GREENBRRV.g01 (geometry) --- (continued)

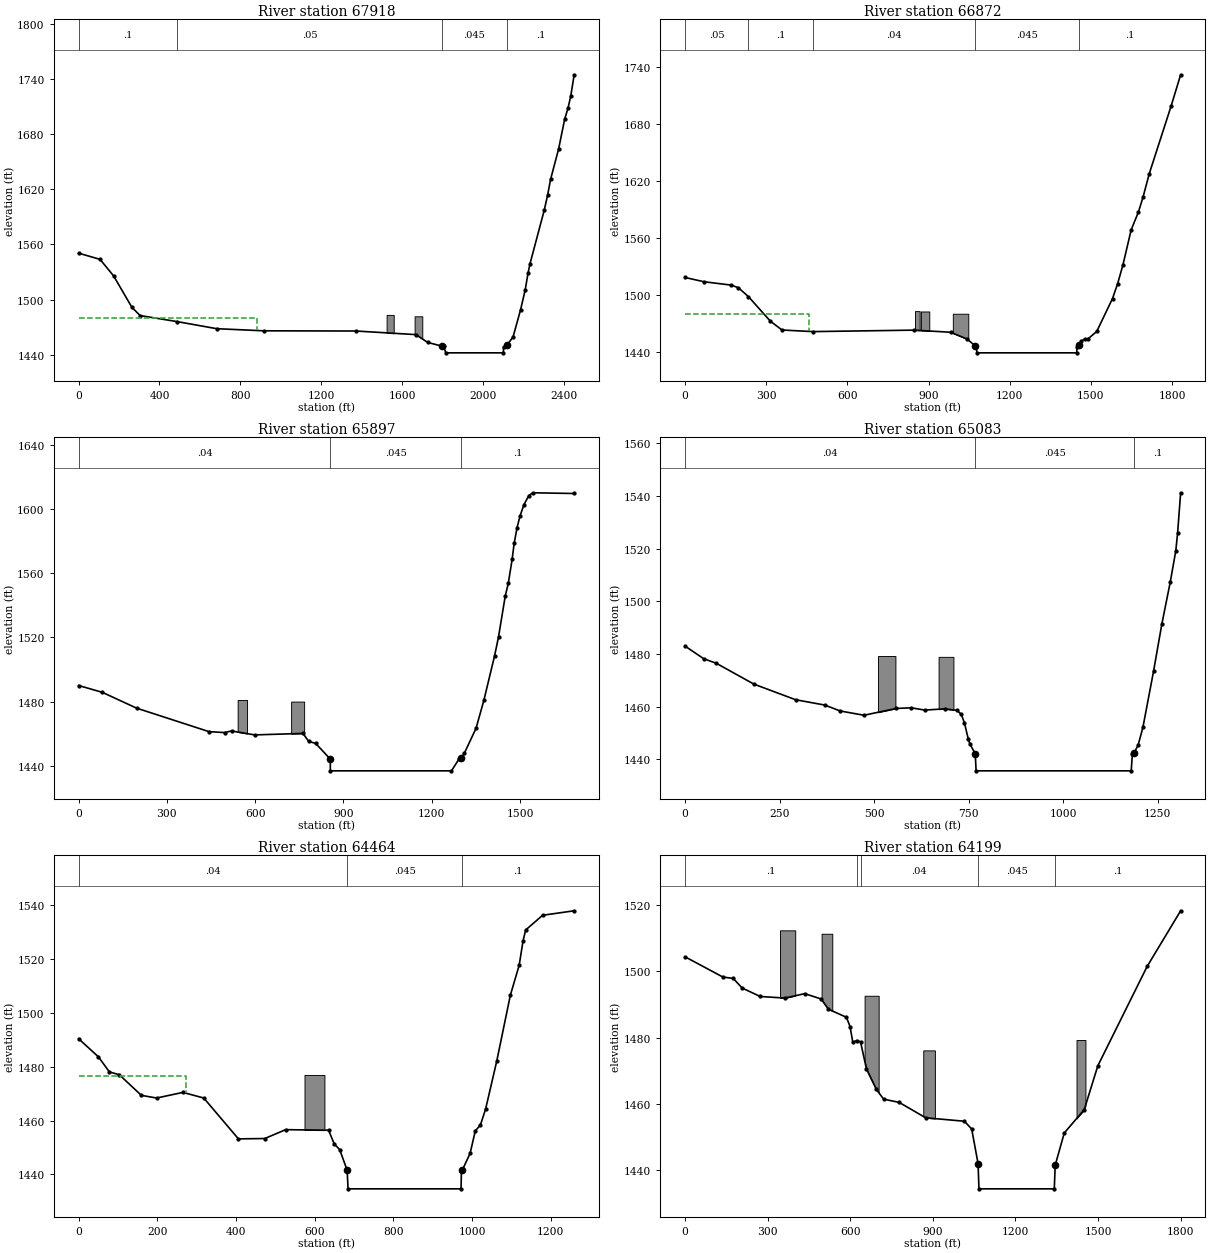
Type RM Length L Ch R = 1 ,67918   ,1053.8,1046.2,1041.3
BEGIN DESCRIPTION:
Channel burn based on effective XS BR
END DESCRIPTION:
XS GIS Cut Line= 2
  2038636.817772227471.4327702512036243.62263414 226938.80274722
#Sta/Elev= 30
       0 1550.49   105.8 1543.75     173 1525.75   263.7 1491.49   304.1  1482.6
   488.7 1475.95   683.5 1468.28     915 1465.98  1372.9 1465.75  1668.7 1461.84
    1727 1453.32  1796.4 1449.38  1806.5 1449.14  1816.7    1442  2101.6    1442
  2102.2 1448.29  2119.1 1450.37  2149.4 1459.28  2186.3 1488.68  2209.7 1510.63
  2223.2 1528.37  2233.3    1539  2303.4    1597  2320.7 1613.95    2335 1630.77
  2374.5 1663.61  2404.7 1696.21  2421.6 1708.62    2435 1721.66  2451.8 1744.65
#Mann= 4 ,-1 , 0
       0      .1       0   488.7     .05       0  1796.4    .045       0
  2119.1      .1       0
#XS Ineff= 2 , 0
          880.28 1480.46
Permanent Ineff=
       F       F
#Block Obstruct= 2 ,-1
 1523.79 1558.94 1483.29 1662.31 1700.34 1481.77
Bank Sta=1796.4,2119.1
XS Rating Curve= 0 ,0
Exp/Cntr=0.3,0.1

Type RM Length L Ch R = 1 ,66872   ,991.4,975.1,962.5
BEGIN DESCRIPTION:
Channel burn based on effective XS BQ
END DESCRIPTION:
XS GIS Cut Line= 2
2038257.51132289226305.1222560552036464.97685023  225927.5180244
#Sta/Elev= 30
       0 1518.69    69.9 1514.21   170.9 1510.69   197.3 1507.88   234.2  1498.6
   314.9 1472.92   358.3 1463.56   472.2 1461.89   847.8 1463.44   981.9  1461.2
  1042.2 1454.11  1072.4 1446.97  1076.5 1446.28  1078.8  1439.6  1447.9  1439.6
  1448.4 1446.15  1454.6  1447.7  1464.7 1451.92  1478.1 1454.31  1488.2 1453.96
  1521.7 1462.04  1580.1 1496.63  1598.8 1512.02  1618.3 1531.56  1649.1 1568.77
  1675.9 1587.42  1692.7 1602.86  1716.1  1627.8  1796.6 1698.57  1831.9 1731.47
#Mann= 5 ,-1 , 0
       0     .05       0   234.2      .1       0   472.2     .04       0
  1072.4    .045       0  1454.6      .1       0
#XS Ineff= 2 , 0
          456.34 1480.03
Permanent Ineff=
       F       F
#Block Obstruct= 3 ,-1
  849.75  867.12  1483.4  871.66  902.73 1483.02  989.72  1046.9 1480.66
Bank Sta=1072.4,1454.6
XS Rating Curve= 0 ,0
Exp/Cntr=0.3,0.1

Type RM Length L Ch R = 1 ,65897   ,613.8,814.1,855
BEGIN DESCRIPTION:
Channel burn based on effective XS BP
END DESCRIPTION:
Node Name=S
XS GIS Cut Line= 2
2038196.74766488225254.7749473152036534.42126514224985.677716479
#Sta/Elev= 30
       0    1490    80.9  1485.7   196.7 1475.88   443.1 1461.18   496.3 1460.59
   519.6 1461.63     598 1459.14   762.2 1460.08   782.1 1455.05   805.4 1453.86
   855.2 1444.03   855.4  1436.7  1267.1  1436.7  1293.1 1444.25  1300.6 1444.97
  1310.6 1447.64  1350.5 1463.26    1377 1480.65  1413.6  1508.6  1426.9 1520.36
  1449.8  1545.9  1460.1 1553.78  1473.3 1568.95  1480.1 1578.83    1490 1588.63
    1500 1595.88  1513.3 1602.91  1529.9 1608.66  1543.2 1610.37    1684 1609.92
#Mann= 3 ,-1 , 0
       0     .04       0   855.2    .045       0  1300.6      .1       0
#Block Obstruct= 2 ,-1
  540.42  572.39 1480.97  722.15  766.35 1479.95
Bank Sta=855.2,1300.6
XS Rating Curve= 0 ,0
Exp/Cntr=0.3,0.1

Type RM Length L Ch R = 1 ,65083   ,639.6,618.8,563.8
BEGIN DESCRIPTION:
Channel burn based on effective XS BO
END DESCRIPTION:
XS GIS Cut Line= 2
2038318.27530897224820.7472720592037150.74057056224226.129038721
#Sta/Elev= 30
       0    1483    49.2  1478.2    82.4 1476.48   181.8 1468.56   292.2 1462.62
   369.5 1460.59     410 1458.35     473 1456.72   558.1 1459.31   597.8 1459.55
   633.8 1458.68   686.2 1459.16   719.3 1458.56   730.4 1457.01   738.7 1453.75
   748.4 1447.86   752.5 1445.98   767.2 1442.02   769.4  1435.6  1179.5  1435.6
  1182.6 1441.91  1187.5 1442.47    1198 1445.48  1210.4 1452.09  1238.5 1473.38
  1260.5 1491.37  1282.7  1507.3  1297.4 1519.23  1302.2 1526.01  1310.2 1541.26
#Mann= 3 ,-1 , 0
       0     .04       0   767.2    .045       0  1187.5      .1       0
#Block Obstruct= 2 ,-1
  510.14  556.09 1479.24  670.25  709.43 1478.92
Bank Sta=767.2,1187.5
XS Rating Curve= 0 ,0
Exp/Cntr=0.3,0.1

Type RM Length L Ch R = 1 ,64464   ,351.2,265.3,252.2
BEGIN DESCRIPTION:
Channel burn based on linear interpolation between effective XS BN and BO
END DESCRIPTION:
XS GIS Cut Line= 3
2038530.94909622224165.365380734 2037649.8724463223818.142978057
2037337.37274322223813.802763641
#Sta/Elev= 30
       0 1490.41    50.1 1483.71    78.3 1478.08   103.4 1477.04   159.4 1469.37
   198.2 1468.38   265.2 1470.47   318.1 1468.38   406.2 1453.19   473.2 1453.32
   526.1 1456.62   635.4 1456.41   649.5 1451.37   663.6 1449.19   682.6 1441.51
   684.8 1434.62   972.1 1434.62     973 1441.41   975.4 1441.61   995.1 1447.82
  1008.2 1456.14  1021.3 1458.38  1034.4 1464.23  1062.9 1482.18  1097.4 1506.61
  1119.8 1517.72  1129.6 1526.74  1136.2 1530.82  1179.3 1536.31  1259.6 1537.98
#Mann= 3 ,-1 , 0
       0     .04       0   682.6    .045       0   975.4      .1       0
#XS Ineff= 2 , 0
          272.11 1476.68
Permanent Ineff=
       F       F
#Block Obstruct= 1 ,-1
  574.13  624.77 1476.96
Bank Sta=682.6,975.4
XS Rating Curve= 0 ,0
Exp/Cntr=0.3,0.1

Type RM Length L Ch R = 1 ,64199   ,1013.4,777.5,466.1
BEGIN DESCRIPTION:
Channel burn based on effective XS BN
END DESCRIPTION:
XS GIS Cut Line= 3
2039028.13699937223720.7629585552037523.54234568223568.445968922
2037274.63409433  223713.3328615
#Sta/Elev= 30
       0 1504.43   137.6  1498.3   174.6 1497.91   207.6 1494.97   272.8 1492.43
     362 1491.95   434.4 1493.28   493.8 1491.69   520.7 1488.58   586.1 1486.13
   599.3 1483.33   609.2 1478.58   623.8 1479.09   637.5 1478.69   658.9 1470.47
   694.9 1464.28   721.3 1461.34   777.4 1460.38     874 1455.71  1014.8 1454.66
  1041.2 1452.31  1064.3 1441.87  1067.6  1434.2  1341.3  1434.2  1344.6 1441.35
  1377.5 1451.11  1450.1 1458.18  1499.5 1471.46  1678.8 1501.55  1800.3 1518.37
#Mann= 5 ,-1 , 0
       0      .1       0   623.8    .016       0   637.5     .04       0
  1064.3    .045       0  1344.6      .1       0
#Block Obstruct= 5 ,-1
  344.91  400.08 1512.45  495.91  534.77 1511.42   652.1   703.2 1492.65
  865.22   907.5 1476.11 1422.05 1454.44 1479.26
Bank Sta=1064.3,1344.6
XS Rating Curve= 0 ,0
Exp/Cntr(USF)=0,0
Exp/Cntr=0.3,0.1

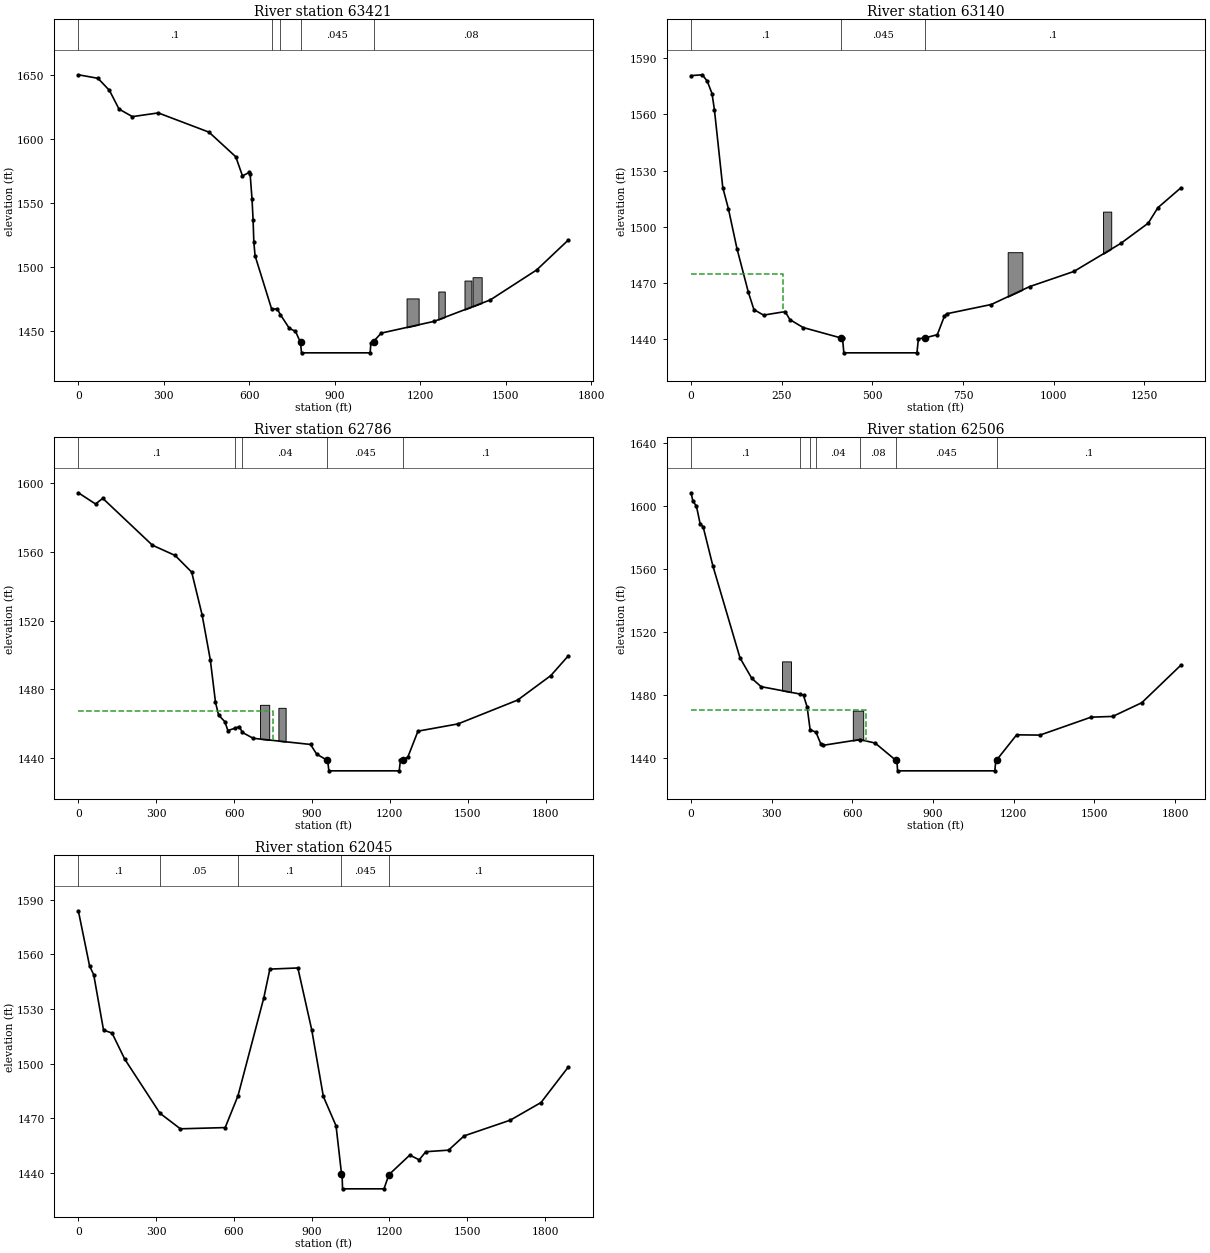
Type RM Length L Ch R = 1 ,63421   ,334.4,281.2,218.8
BEGIN DESCRIPTION:
Channel burn based on linear interpolation between effective XS BM and BN
END DESCRIPTION:
XS GIS Cut Line= 3
2038207.11127476 222569.097914992037608.98846181222699.124613457
2037192.90302672223724.478007083
#Sta/Elev= 30
       0    1650    68.8 1647.25   109.1 1637.79   142.7 1623.26   189.7 1617.37
   280.3 1620.27   458.3 1605.27   552.3 1586.07   575.8 1571.16   600.4 1573.98
   602.6 1572.74   609.3 1553.16     613 1537.08   615.7 1519.49     620 1508.94
     678 1467.44   697.9 1467.45   708.6 1463.04   740.4 1452.25   761.7 1450.02
   779.4 1441.33   782.9 1433.21  1023.7 1433.21  1026.2 1440.59  1035.6 1442.05
  1062.6 1448.59  1247.9 1457.75    1445 1474.43  1607.9 1497.83  1718.7 1521.11
#Mann= 5 ,-1 , 0
       0      .1       0     678    .016       0   708.6      .1       0
   779.4    .045       0  1035.6     .08       0
#Block Obstruct= 4 ,-1
  1151.5 1193.84 1475.64 1262.88 1285.47 1481.02 1354.73 1378.93 1489.56
 1383.12 1414.99 1492.17
Bank Sta=779.4,1035.6
XS Rating Curve= 0 ,0
Exp/Cntr(USF)=0,0
Exp/Cntr=0.3,0.1

Type RM Length L Ch R = 1 ,63140   ,380.1,353.7,305.1
BEGIN DESCRIPTION:
Channel burn based on effective XS BM
END DESCRIPTION:
XS GIS Cut Line= 2
2037272.26854272222429.2543516462037107.33777022223770.399963304
#Sta/Elev= 30
       0 1580.72    31.4 1581.17    45.1 1577.62    57.9 1571.11    64.5 1562.51
    87.6 1520.96   103.2 1509.59   126.7 1488.41   158.1 1465.13   173.5 1455.86
     200 1452.93   259.5  1454.8   272.7 1450.53   309.2 1446.31   414.9 1440.67
   417.9 1440.46   421.5  1432.8   623.1  1432.8   627.1  1440.3   644.3 1440.75
   679.3 1442.47   699.1  1452.5   705.7 1453.67     828 1458.59   933.8 1468.13
  1056.1 1476.24    1185 1491.16  1261.1    1502  1287.5 1510.22  1351.2 1520.87
#Mann= 3 ,-1 , 0
       0      .1       0   414.9    .045       0   644.3      .1       0
#XS Ineff= 2 , 0
          253.18 1474.77
Permanent Ineff=
       F       F
#Block Obstruct= 2 ,-1
  873.37   913.9  1486.5 1136.41 1158.98 1508.15
Bank Sta=414.9,644.3
XS Rating Curve= 0 ,0
Exp/Cntr=0.3,0.1

Type RM Length L Ch R = 1 ,62786   ,326.2,280.2,209.4
BEGIN DESCRIPTION:
Channel burn based on linear interpolation between effective XS BL and BM
END DESCRIPTION:
XS GIS Cut Line= 3
2037508.68215157222186.4479166442036851.11856218222639.683837015
2036877.12390187 223728.19305561
#Sta/Elev= 30
       0 1594.51    66.2 1587.98    94.1 1591.27   285.3 1563.94     373 1557.95
   436.7 1548.23   476.8 1523.34   508.5 1497.03   528.4 1472.32   540.3 1464.88
   564.3 1461.03   576.2 1455.86   604.2 1457.22     620 1458.18     632 1454.76
   673.6 1451.33   894.6 1447.74   918.1 1442.11   957.3 1438.64   960.6 1438.46
   965.2 1432.35  1236.3 1432.35  1240.9 1438.51  1249.4 1438.93  1269.1 1440.24
  1308.5 1455.49  1462.8 1459.72  1692.5 1473.62  1820.5 1487.92  1887.5 1499.38
#Mann= 5 ,-1 , 0
       0      .1       0   604.2    .016       0     632     .04       0
   957.3    .045       0  1249.4      .1       0
#XS Ineff= 2 , 0
          749.56 1467.09
Permanent Ineff=
       F       F
#Block Obstruct= 2 ,-1
  699.94   735.4 1470.85  770.73  798.63  1469.1
Bank Sta=957.3,1249.4
XS Rating Curve= 0 ,0
Exp/Cntr(USF)=0,0
Exp/Cntr=0.3,0.1

Type RM Length L Ch R = 1 ,62506   ,512,460.5,335.4
BEGIN DESCRIPTION:
Channel burn based on linear interpolation between effective XS BL and BM
END DESCRIPTION:
XS GIS Cut Line= 2
2036349.58701095 222004.41053879 2036773.1025431223776.488686469
#Sta/Elev= 30
       0 1608.26     6.7 1603.14    20.2 1599.69    33.7 1588.74    45.4 1586.47
    80.9 1562.14   182.1 1503.59     226  1490.6   260.5 1485.35   404.8 1480.69
   418.3 1479.79   431.8 1472.51   442.9 1458.06   464.7 1456.44   482.4 1449.19
   492.5  1448.2     628 1451.82   684.7  1449.6   761.4  1438.7   765.7 1438.42
   768.2 1431.98    1130 1431.98  1133.4 1438.49  1137.2 1438.96    1211 1454.81
  1297.8 1454.64  1487.6    1466  1568.5 1466.48  1676.5 1475.17    1822    1499
#Mann= 7 ,-1 , 0
       0      .1       0   404.8     .04       0   442.9    .016       0
   464.7     .04       0     628     .08       0   761.4    .045       0
  1137.2      .1       0
#XS Ineff= 2 , 0
          652.39 1470.67
Permanent Ineff=
       F       F
#Block Obstruct= 2 ,-1
  338.39  371.69 1501.37  601.71  640.39 1470.13
Bank Sta=761.4,1137.2
XS Rating Curve= 0 ,0
Exp/Cntr(USF)=0,0
Exp/Cntr=0.3,0.1

Type RM Length L Ch R = 1 ,62045   ,675.9,721.9,795.7
BEGIN DESCRIPTION:
Channel burn based on effective XS BL
END DESCRIPTION:
XS GIS Cut Line= 2
2035518.79632789222320.7473508122036660.28912364223826.823734984
#Sta/Elev= 30
       0 1583.84    43.5 1553.47    59.3  1548.8    97.1 1518.44     130 1516.78
   179.1 1502.47   314.9 1472.83   393.5 1464.31   566.4 1464.98   615.8  1482.4
   715.4  1536.1   738.8 1551.86   846.8 1552.49   900.4  1518.5   945.1 1482.06
   994.1 1465.94  1015.1 1439.78  1015.1 1439.71  1017.5 1438.39  1019.2  1431.4
  1179.1  1431.4  1197.8 1439.13  1278.5  1449.9  1314.9  1447.3  1340.3 1451.75
    1428 1452.61  1488.2 1460.43  1666.2 1469.05  1784.9 1478.73  1889.8 1498.16
#Mann= 5 ,-1 , 0
       0      .1       0   314.9     .05       0   615.8      .1       0
  1015.1    .045       0  1197.8      .1       0
Bank Sta=1015.1,1197.8
XS Rating Curve= 0 ,0
Exp/Cntr=0.8,0.6