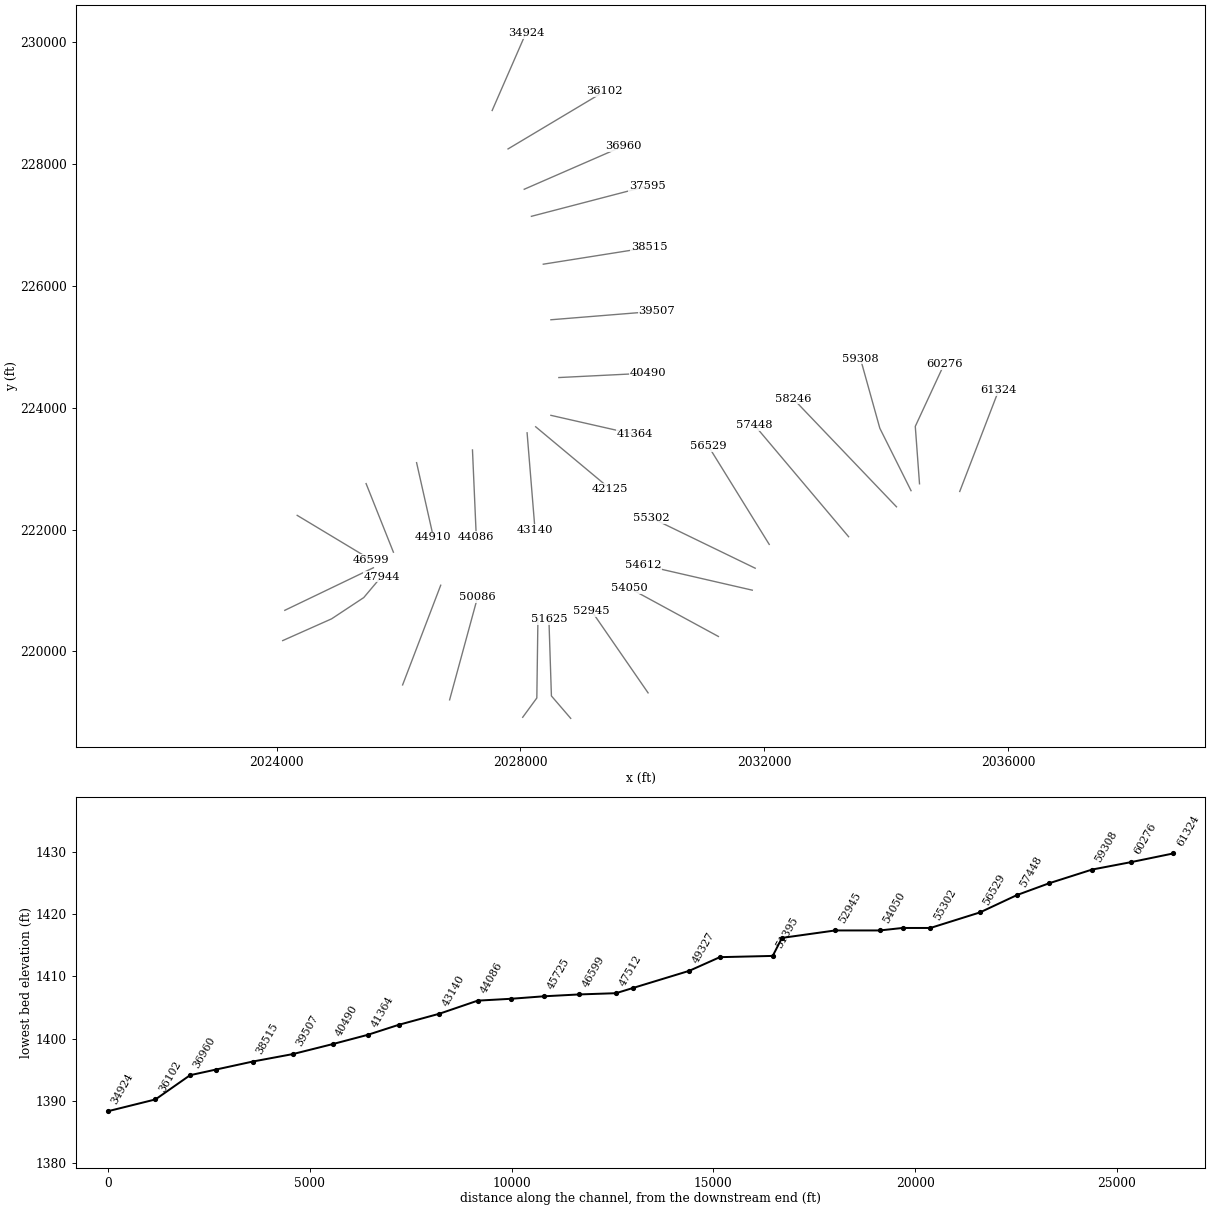
HEC-RAS study GREENBRRV.prj: GREENBRRV

--- GREENBRRV.g01 (geometry) --- (continued)

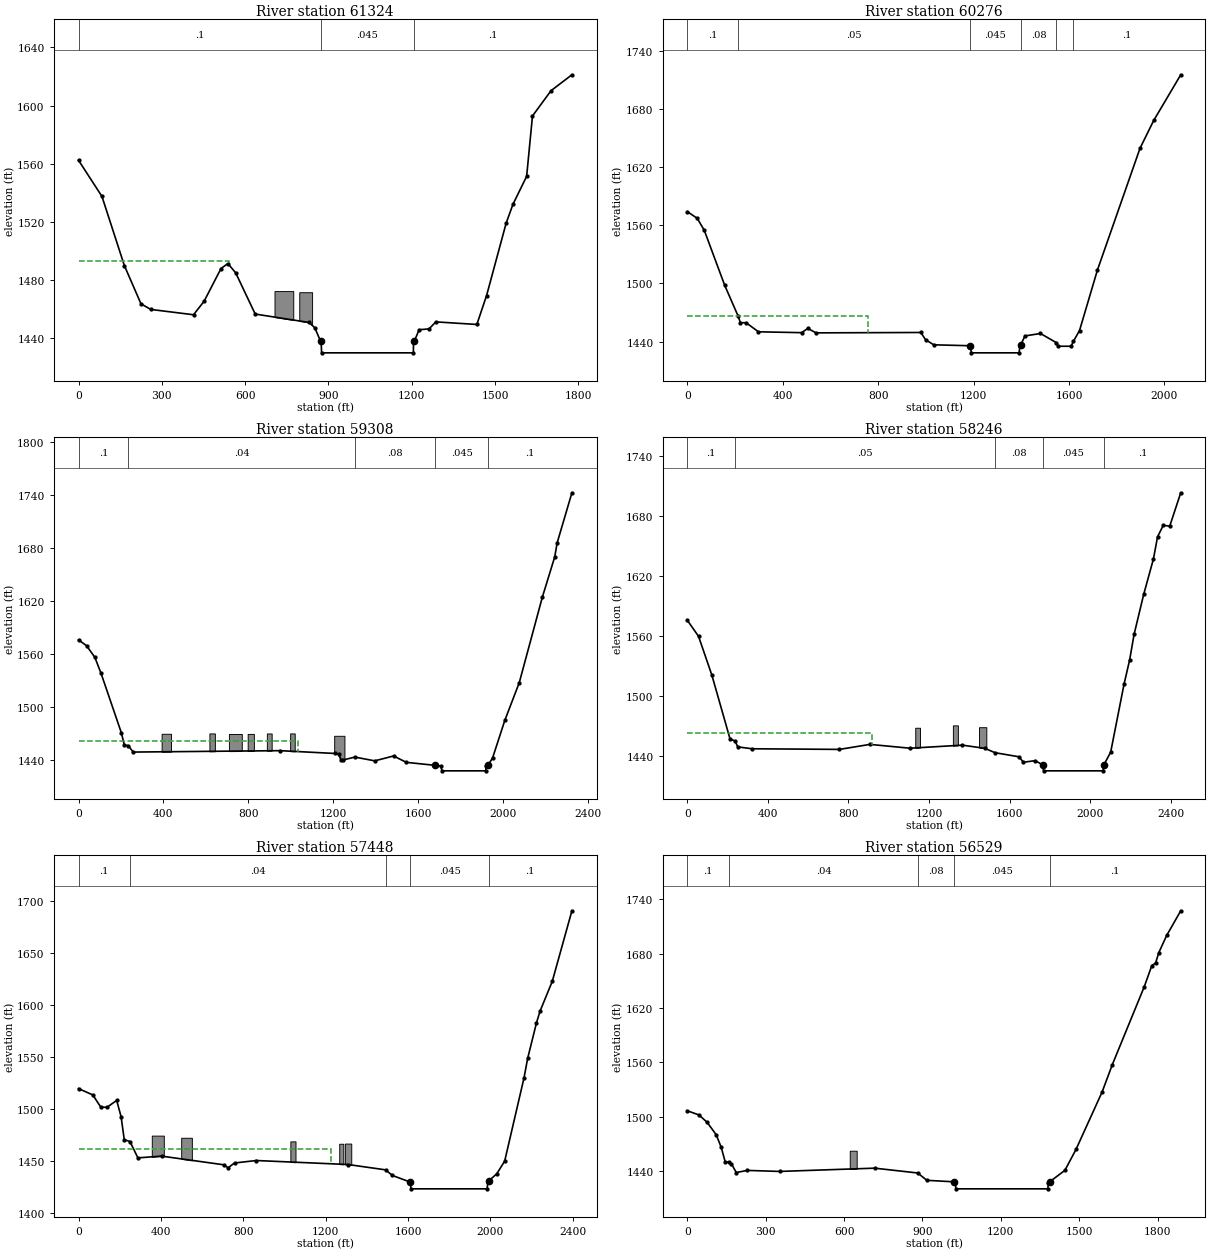
Type RM Length L Ch R = 1 ,61324   ,1002.7,1047.4,1026.9
BEGIN DESCRIPTION:
Channel burn based on effective XS BK
END DESCRIPTION:
Node Name=R
XS GIS Cut Line= 2
2035206.29629672222624.5666250592035844.31700231224282.552810401
#Sta/Elev= 30
       0 1562.32    84.3 1537.45   165.1 1489.82   224.9 1463.53     260 1459.67
   414.1 1456.01   452.2 1465.32   513.1 1487.83   537.8 1491.26   565.9 1484.83
   636.2 1456.48   830.4 1450.69   850.6 1447.07   871.7  1437.7   873.6 1437.36
   875.2  1429.8  1205.7  1429.8  1206.1 1437.22  1208.7 1437.63  1226.4 1445.71
    1262 1446.28  1286.5  1451.1  1434.2 1449.33  1469.3 1469.25  1539.6 1518.97
  1564.2    1532  1613.5 1551.26  1634.5 1592.79  1701.3 1610.19  1776.5 1621.14
#Mann= 3 ,-1 , 0
       0      .1       0   871.7    .045       0  1208.7      .1       0
#XS Ineff= 2 , 0
          540.85 1492.96
Permanent Ineff=
       F       F
#Block Obstruct= 2 ,-1
  705.62  773.17 1472.29  794.78  841.01 1471.51
Bank Sta=871.7,1208.7
XS Rating Curve= 0 ,0
Exp/Cntr=0.3,0.1

Type RM Length L Ch R = 1 ,60276   ,508.7,968.4,1075.2
BEGIN DESCRIPTION:
Channel burn based on effective XS BJ
END DESCRIPTION:
XS GIS Cut Line= 3
2034546.57386288222750.4348116372034477.12944797223692.275119558
2034950.21970914224712.240271226
#Sta/Elev= 30
       0 1574.14    41.5 1567.27    71.1  1554.8   156.6 1498.08   212.5 1466.54
   222.4  1459.5   246.2 1459.49   298.1 1450.12     479 1449.22   505.3 1453.64
   539.3 1449.02   978.9 1449.41   998.6    1442  1033.1 1436.69    1185 1435.73
  1191.3  1428.4  1391.2  1428.4  1393.9  1435.3  1397.1 1436.18  1415.4 1445.84
  1480.4 1448.37  1546.7 1438.98  1553.9 1435.21  1608.9  1435.2  1618.7 1440.28
  1644.3 1451.45  1719.5 1513.96  1897.9 1639.57  1955.3 1668.25  2068.7 1715.44
#Mann= 6 ,-1 , 0
       0      .1       0   212.5     .05       0    1185    .045       0
  1397.1     .08       0  1546.7    .045       0  1618.7      .1       0
#XS Ineff= 2 , 0
          757.75 1466.83
Permanent Ineff=
       F       F
Bank Sta=1185,1397.1
XS Rating Curve= 0 ,0
Exp/Cntr=0.3,0.1

Type RM Length L Ch R = 1 ,59308   ,722,1061.9,1124.1
BEGIN DESCRIPTION:
Channel burn based on effective XS BI
END DESCRIPTION:
XS GIS Cut Line= 3
2034407.68503305222637.5875963872033895.53218597223661.892962471
2033578.69194038224799.045871899
#Sta/Elev= 30
       0 1575.56    37.7 1569.02      77 1555.78   106.2 1537.62   201.8 1470.37
   215.8 1456.68   234.8  1455.6   257.8 1448.47   949.5 1450.06  1209.2 1446.88
  1226.2 1445.74  1236.5 1439.91  1246.6  1439.5  1302.7 1442.77  1396.5 1438.52
  1485.1 1444.05    1545 1436.82 1681.421433.417  1707.5 1432.71  1713.3  1427.2
  1919.2  1427.2  1920.6 1432.31 1931.741434.127  1951.7 1441.76  2009.6 1484.49
  2077.6 1527.16  2186.1 1623.79  2244.6 1669.52  2256.2 1685.55  2325.7 1742.22
#Mann= 5 ,-1 , 0
       0      .1       0   234.8     .04       0  1302.7     .08       0
 1681.42    .045       0 1931.74      .1       0
#XS Ineff= 2 , 0
         1036.62 1460.68
Permanent Ineff=
       F       F
#Block Obstruct= 7 ,-1
  391.65     436 1469.19  616.94  642.67 1469.59  708.87  769.56 1468.99
  797.34  826.56 1469.06  887.69   910.4 1469.53  997.53 1019.06  1469.6
 1205.12 1253.47 1466.91
Bank Sta=1681.42,1931.74
XS Rating Curve= 0 ,0
Exp/Cntr=0.3,0.1

Type RM Length L Ch R = 1 ,58246   ,857,797.6,791.5
BEGIN DESCRIPTION:
Channel burn based on effective XS BH
END DESCRIPTION:
Node Name=Q
XS GIS Cut Line= 2
 2034168.9699593222372.8305799812032476.26140247224143.663980559
#Sta/Elev= 30
       0 1575.68    55.4 1559.77   121.8 1520.75     212 1456.88   237.5 1454.83
     250 1449.01   321.1  1447.1     755 1446.47   906.4 1451.47  1105.4 1447.66
  1365.8 1450.72  1476.7 1447.52  1527.7 1443.16  1646.2 1439.08  1668.8  1433.6
  1727.3 1435.21  1764.2 1430.91  1768.7    1425  2063.8    1425 2068.931431.329
  2101.8  1443.7  2168.1  1511.7    2196 1536.11    2218 1561.59  2265.6 1601.57
  2314.4  1637.4  2334.4 1659.29  2362.9 1670.84    2395 1670.01  2449.7 1703.42
#Mann= 5 ,-1 , 0
       0      .1       0   237.5     .05       0  1527.7     .08       0
  1764.2    .045       0 2068.93      .1       0
#XS Ineff= 2 , 0
           916.9 1462.88
Permanent Ineff=
       F       F
#Block Obstruct= 3 ,-1
 1131.44 1155.23 1468.16 1318.35 1343.17 1470.53 1447.95 1484.46 1468.69
Bank Sta=1764.2,2068.93
XS Rating Curve= 0 ,0
Exp/Cntr=0.3,0.1

Type RM Length L Ch R = 1 ,57448   ,984.2,919.5,878
BEGIN DESCRIPTION:
Channel burn based on effective XS BG
END DESCRIPTION:
XS GIS Cut Line= 2
2033383.37966697221882.3791330612031838.24069689223713.976519734
#Sta/Elev= 30
       0 1519.38    69.5 1513.28   108.1 1501.57   138.2  1501.4   185.4 1508.02
   206.8 1492.32   222.1  1470.3   249.8 1468.54   288.4 1452.84     403 1454.53
   706.4 1446.17   726.2 1443.29   757.6 1447.92   863.6  1450.3  1308.7 1446.46
    1491 1441.35  1524.6 1435.95  1612.1  1429.5  1614.4  1423.1  1984.6  1423.1
  1988.2 1429.69  1991.6 1430.64  2031.2  1437.5  2069.7 1449.71  2163.9 1529.87
  2181.3 1548.39  2224.2 1582.52  2241.4 1593.69  2300.9  1622.4  2396.3 1690.16
#Mann= 5 ,-1 , 0
       0      .1       0   249.8     .04       0    1491     .08       0
  1612.1    .045       0  1991.6      .1       0
#XS Ineff= 2 , 0
         1225.35 1461.43
Permanent Ineff=
       F       F
#Block Obstruct= 5 ,-1
  355.74  414.16 1474.23  498.62  550.48 1472.16 1028.81 1053.89 1468.69
 1266.18 1286.04 1466.42 1293.51 1324.66 1466.58
Bank Sta=1612.1,1991.6
XS Rating Curve= 0 ,0
Exp/Cntr=0.3,0.1

Type RM Length L Ch R = 1 ,56529   ,882.9,1226.7,1311
BEGIN DESCRIPTION:
Channel burn based on effective XS BF
END DESCRIPTION:
XS GIS Cut Line= 2
2032081.29631314221756.5112745612031087.37244797 223362.41390264
#Sta/Elev= 30
       0 1506.43    44.6 1501.84    75.5 1493.76   110.2 1480.12   129.5 1466.27
   144.9 1450.05   160.3 1449.64   168.1 1448.17   187.3  1438.3   229.8 1440.64
   353.3 1439.51   717.1 1443.12   881.9 1437.79   916.6 1429.71  1020.8 1428.03
  1024.6 1426.95  1028.5  1420.3  1379.6  1420.3  1382.1  1426.8  1387.3 1428.14
  1445.2 1440.74  1487.6 1463.77  1587.9 1527.41  1626.5 1557.27  1749.1 1643.47
  1777.7 1666.57  1792.4 1669.59  1804.4 1680.84  1834.8 1699.96  1888.6 1727.18
#Mann= 5 ,-1 , 0
       0      .1       0   160.3     .04       0   881.9     .08       0
  1020.8    .045       0  1387.3      .1       0
#Block Obstruct= 1 ,-1
  621.58  648.17 1462.38
Bank Sta=1020.8,1387.3
XS Rating Curve= 0 ,0
Exp/Cntr=0.3,0.1

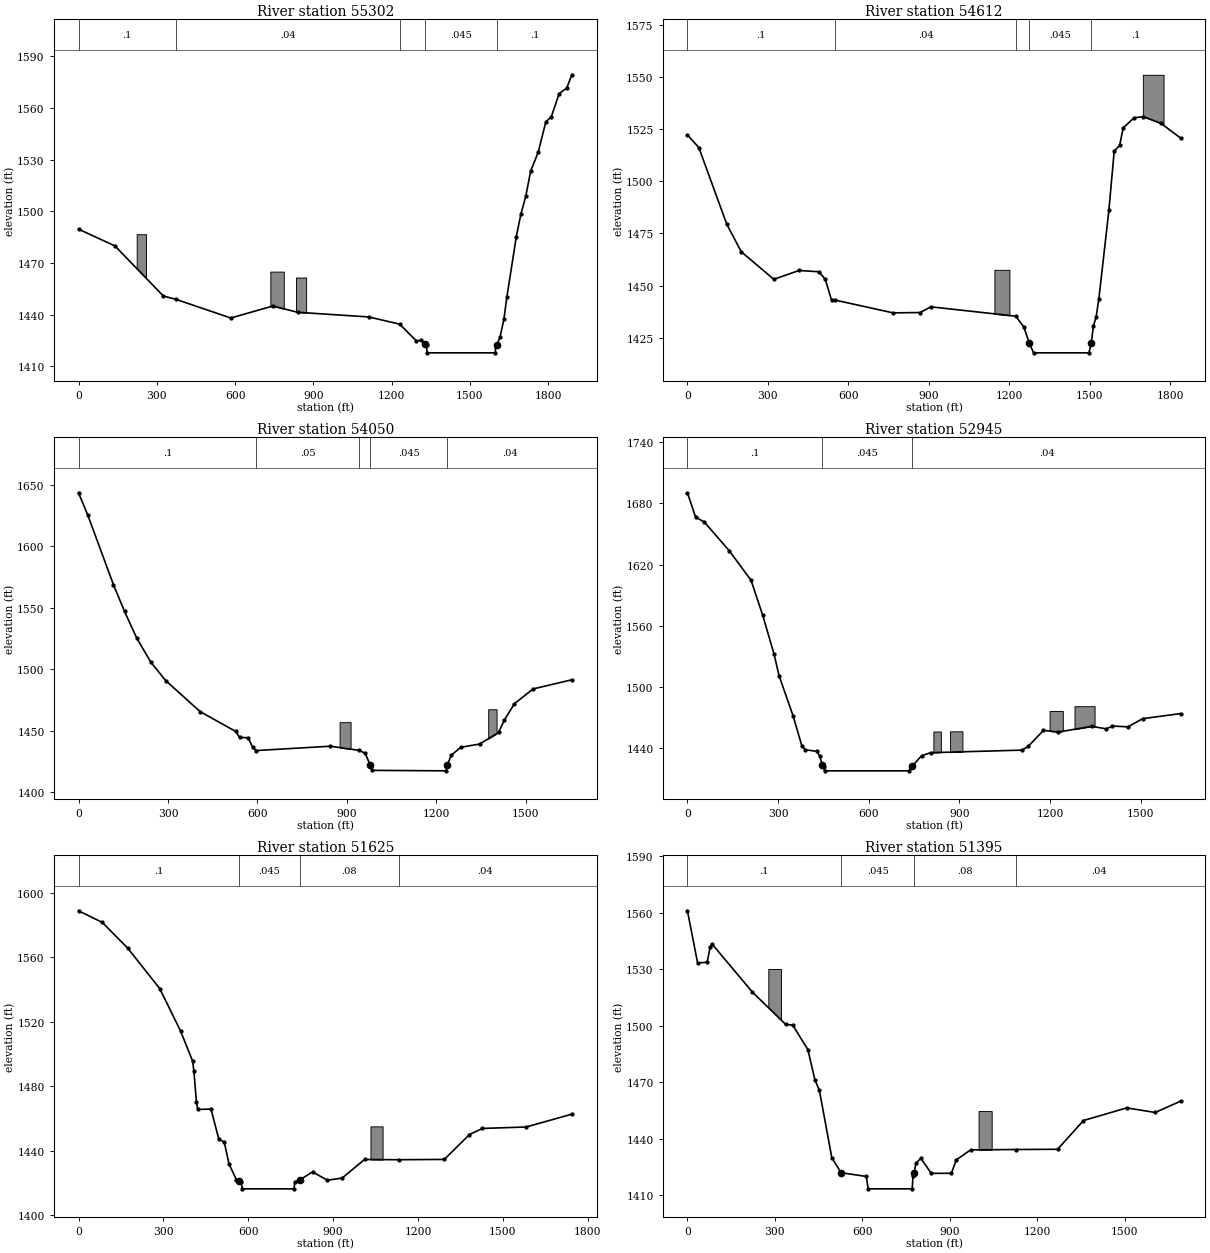
Type RM Length L Ch R = 1 ,55302   ,565,689.8,738.3
BEGIN DESCRIPTION:
Channel burn based on effective XS BE
END DESCRIPTION:
Node Name=P
XS GIS Cut Line= 2
2031851.26134014221365.8860715632030149.87268256222190.538949817
#Sta/Elev= 30
       0 1489.59   139.6 1479.85   325.3 1450.76   372.9 1448.87   583.8 1438.01
   744.6 1444.98   839.4 1441.35  1112.8 1438.62  1230.7 1434.45  1295.1 1424.66
  1313.3 1425.13  1327.9 1422.93  1334.4 1422.15  1335.2  1417.8  1597.7  1417.8
  1598.2 1422.04  1603.1 1422.53  1615.4  1426.9  1630.2 1437.21  1641.5 1450.02
  1677.9 1485.32  1695.2 1498.18  1714.4 1508.83  1732.6 1523.15  1761.8 1534.28
  1790.9 1551.87  1811.9 1554.83    1842 1568.25  1871.2  1571.5  1890.7 1579.18
#Mann= 5 ,-1 , 0
       0      .1       0   372.9     .04       0  1230.7     .08       0
  1327.9    .045       0  1603.1      .1       0
#Block Obstruct= 3 ,-1
  222.92  258.63 1486.66   735.1  786.69 1464.95  833.49  872.37 1461.52
Bank Sta=1327.9,1603.1
XS Rating Curve= 0 ,0
Exp/Cntr=0.3,0.1

Type RM Length L Ch R = 1 ,54612   ,670.1,562.3,527.1
BEGIN DESCRIPTION:
Channel burn based on linear interpolation between effective XS BD and BE
END DESCRIPTION:
XS GIS Cut Line= 2
2031803.51832539221005.6430256372030010.98385271221417.969628811
#Sta/Elev= 30
       0 1522.11    42.6 1516.09     147  1479.3   200.9 1466.19   322.1 1453.02
   416.3 1457.23   490.4 1456.62     514 1453.02   537.5 1442.94     551 1443.05
   766.6 1436.94   867.4  1437.1   907.8 1439.83  1224.3 1435.35  1254.6 1430.11
  1274.8 1422.32  1290.9  1417.8    1497  1417.8  1505.6 1422.49  1513.8 1430.69
  1523.9 1435.06    1534 1443.66  1571.3 1485.98  1591.2 1514.39  1611.4 1517.13
  1624.9 1525.56  1665.3 1530.32  1699.9 1530.92  1766.3 1527.62  1839.3 1520.57
#Mann= 5 ,-1 , 0
       0      .1       0     551     .04       0  1224.3     .08       0
  1274.8    .045       0  1505.6      .1       0
#Block Obstruct= 2 ,-1
 1144.47 1200.53 1457.56 1697.99 1775.18 1550.94
Bank Sta=1274.8,1505.6
XS Rating Curve= 0 ,0
Exp/Cntr=0.3,0.1

Type RM Length L Ch R = 1 ,54050   ,1208.4,1104.8,936.1
BEGIN DESCRIPTION:
Channel burn based on effective XS BD
END DESCRIPTION:
XS GIS Cut Line= 2
2031247.96300605220246.0943478942029793.96985105221036.025182724
#Sta/Elev= 30
       0 1643.69    31.1  1625.5     117 1568.98   154.3 1547.13   195.4 1525.39
   242.6  1505.8   292.5 1490.84   408.2 1465.54   527.7 1449.42   540.2 1444.57
   569.2 1444.34   583.7 1436.61   595.8 1433.91     845 1437.44   942.2 1434.02
   961.7 1431.64   978.1 1422.16   982.3 1421.59   982.9  1417.8  1233.4  1417.4
  1234.5 1421.58  1236.6 1421.98  1250.3 1430.07  1281.9 1436.54  1345.4 1439.22
  1408.9 1448.63  1427.5 1458.42  1461.9    1472  1524.8 1484.07  1654.7 1491.51
#Mann= 5 ,-1 , 0
       0      .1       0   595.8     .05       0   942.2     .08       0
   978.1    .045       0  1236.6     .04       0
#Block Obstruct= 2 ,-1
  875.72  912.53 1457.01 1374.01 1402.17 1467.51
Bank Sta=978.1,1236.6
XS Rating Curve= 0 ,0
Exp/Cntr=0.3,0.1

Type RM Length L Ch R = 1 ,52945   ,1417,1320.4,1109.8
BEGIN DESCRIPTION:
Channel burn based on effective XS BB
END DESCRIPTION:
XS GIS Cut Line= 2
2030094.31701939219321.2248065622029167.23357172220664.974743724
#Sta/Elev= 30
       0 1690.51    27.2 1666.53    56.1 1661.77   138.8 1633.44   210.6 1604.56
   248.9  1570.4   286.7 1532.08   303.2 1510.88   350.1 1471.04   378.6 1442.08
   390.4 1438.05   428.2 1436.57   437.4 1432.15     447 1422.87   451.6 1421.18
   453.7  1417.4   732.7  1417.4  743.381421.767   774.9 1432.27   805.6 1435.25
  1107.5 1437.75  1127.3 1441.31  1178.2 1457.13  1227.7 1455.54  1338.6 1461.13
  1385.8 1458.64  1406.4 1461.38  1458.2 1460.63    1506 1468.62  1632.5 1473.66
#Mann= 3 ,-1 , 0
       0      .1       0     447    .045       0  743.38     .04       0
#Block Obstruct= 4 ,-1
  813.93  838.75 1456.04  869.14  909.99 1456.23 1198.35 1242.22 1476.15
 1280.94 1347.34  1480.9
Bank Sta=447,743.38
XS Rating Curve= 0 ,0
Exp/Cntr=0.3,0.1

Type RM Length L Ch R = 1 ,51625   ,236.9,229.4,211.2
BEGIN DESCRIPTION:
Channel burn based on effective XS BA
END DESCRIPTION:
XS GIS Cut Line= 3
2028825.42285121218902.8921253212028508.93014877219270.847055801
2028467.76036634220529.098531358
#Sta/Elev= 30
       0 1588.98    84.4 1581.71   174.6 1565.63   287.1 1540.64   360.7  1514.3
   403.1 1495.74   407.8 1489.59   416.9 1470.17   421.7 1465.54   468.3 1465.78
   495.8 1447.24   515.5 1445.12   531.9 1431.79   558.2 1421.86     568 1421.04
   574.6 1420.48   579.4  1416.2   761.7  1416.2     765 1420.39   781.4 1421.65
   827.3 1426.72   879.9 1421.54   932.4 1422.93  1011.2 1434.45  1132.5 1434.28
  1293.5 1434.49  1382.1 1449.92  1428.1 1453.74  1582.3 1454.62  1744.3  1462.6
#Mann= 4 ,-1 , 0
       0      .1       0     568    .045       0   781.4     .08       0
  1132.5     .04       0
#Block Obstruct= 1 ,-1
 1032.22 1075.13 1455.03
Bank Sta=568,781.4
XS Rating Curve= 0 ,0
Exp/Cntr(USF)=0,0
Exp/Cntr=0.3,0.1

Type RM Length L Ch R = 1 ,51395   ,1347.6,1309.9,1217
BEGIN DESCRIPTION:
Channel burn based on effective XS AZ
END DESCRIPTION:
XS GIS Cut Line= 3
2028038.05076221218920.9039051352028269.63078838219237.396607576
 2028287.6425682220536.817865564
#Sta/Elev= 30
       0 1560.96      35 1533.22    67.8 1533.68    78.1 1541.83    84.8 1543.26
     223 1517.74   336.8 1500.63   361.2 1500.22   413.1 1487.23     437 1471.31
   452.5 1465.63   495.1 1429.88   527.11421.846   613.3 1419.89   619.8  1413.3
   770.8  1413.3   773.6 1419.97   777.3 1421.93   783.9 1427.01   800.3 1429.49
   836.4 1421.51   905.3 1421.56   921.7 1428.62   970.9 1433.97  1128.4 1434.19
  1269.5 1434.31  1358.1 1449.58  1506.5 1456.29  1604.2 1453.85  1691.7  1459.9
#Mann= 4 ,-1 , 0
       0      .1       0   527.1    .045       0   777.3     .08       0
  1128.4     .04       0
#Block Obstruct= 2 ,-1
   277.4  320.87 1530.05  998.42 1043.35 1454.61
Bank Sta=527.1,777.3
XS Rating Curve= 0 ,0
Exp/Cntr(USF)=0,0
Exp/Cntr=0.3,0.1

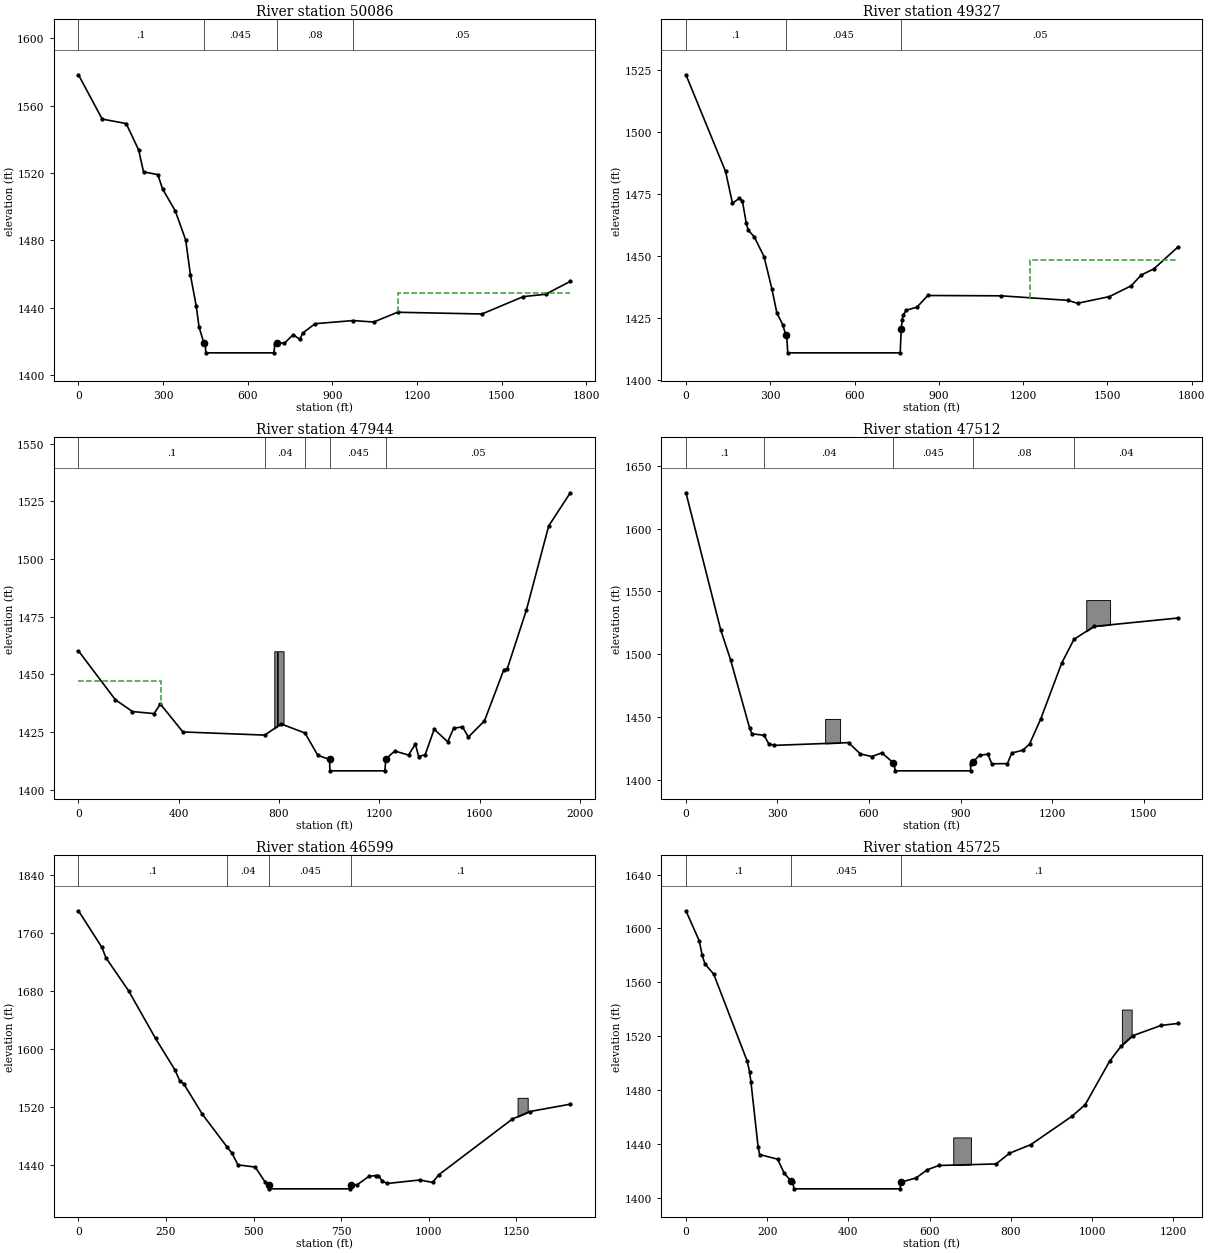
Type RM Length L Ch R = 1 ,50086   ,776.3,758.1,725.6
BEGIN DESCRIPTION:
Channel burn based on effective XS AY
END DESCRIPTION:
Node Name=O
XS GIS Cut Line= 2
 2026839.1086348219206.6413743052027297.44203572220888.932957232
#Sta/Elev= 30
       0  1578.3    84.2 1551.98   169.2 1549.33   213.4 1533.64   230.7 1520.63
   281.4 1518.98   298.4  1510.4   343.1 1497.48   380.1  1480.2     397 1459.38
   417.4    1441   427.6 1428.42   444.3 1419.12   449.9 1418.24   451.4  1413.1
   692.9  1413.1   696.3 1418.36   702.3 1419.21   730.3 1418.78   760.9 1423.92
   784.7 1421.16   794.9 1424.86   839.1 1430.42   973.4 1432.27  1046.5 1431.41
  1131.1 1437.21  1430.4 1436.18  1577.3 1446.52  1655.8 1447.89  1743.6 1455.55
#Mann= 4 ,-1 , 0
       0      .1       0   444.3    .045       0   702.3     .08       0
   973.4     .05       0
#XS Ineff= 2 , 0
                         1133.75         1448.39
Permanent Ineff=
       F       F
Bank Sta=444.3,702.3
XS Rating Curve= 0 ,0
Exp/Cntr=0.3,0.1

Type RM Length L Ch R = 1 ,49327   ,1674.2,1383.4,1176.9
BEGIN DESCRIPTION:
Channel burn based on effective XS AX
END DESCRIPTION:
XS GIS Cut Line= 2
 2026068.2755308219451.4328794782026693.27526505221086.849556148
#Sta/Elev= 30
       0 1523.06     141 1484.05   165.6 1471.23   189.5 1473.22   200.7 1472.28
   214.9  1463.1   221.8 1460.36   242.9 1457.74     278 1449.72   306.1  1436.6
   323.6 1427.01   344.7  1422.2   355.2 1418.12   358.8 1417.62   362.3  1410.9
   762.7  1410.9   766.2  1420.5   769.7 1424.21   773.2 1426.09   783.7 1428.08
   822.3 1429.34     861 1434.03  1122.1  1433.9  1358.4 1432.08    1394 1430.89
  1507.3 1433.58  1584.8 1437.93  1620.2 1442.24  1665.9 1444.81  1750.8 1453.54
#Mann= 3 , 0 , 0
       0      .1       0   355.2    .045       0   766.2     .05       0
#XS Ineff= 2 , 0
                         1225.92         1448.19
Permanent Ineff=
       F       F
Bank Sta=355.2,766.2
XS Rating Curve= 0 ,0
Exp/Cntr=0.3,0.1

Type RM Length L Ch R = 1 ,47944   ,451.3,432,400.9
XS GIS Cut Line= 4
2024101.31523742220178.447080841 2024903.9035577220535.826031003
2025430.88607743220884.1190756522025721.63505384 221229.38348513
#Sta/Elev= 30
       0 1460.19   147.1 1438.99   215.4 1433.86   301.6 1432.98   326.8 1437.12
   416.5 1425.02   743.3 1423.65   807.9  1428.5   903.5 1424.56   954.6 1414.88
  1001.6  1413.1  1002.9 1408.16    1222 1408.16    1226 1413.28  1261.4 1416.76
  1316.4    1415  1343.9 1419.78  1356.7 1414.35  1382.8 1415.15  1418.7 1426.18
  1472.8 1420.75  1496.4 1426.62  1531.6 1427.24  1555.1 1422.82  1619.4 1429.84
  1696.6 1452.02  1709.5 1452.18  1786.7 1477.93  1875.5 1514.34  1961.6  1528.7
#Mann= 5 ,-1 , 0
       0      .1       0   743.3     .04       0   903.5      .1       0
  1001.6    .045       0    1226     .05       0
#XS Ineff= 2 , 0
          328.39 1446.96
Permanent Ineff=
       F       F
#Block Obstruct= 2 ,-1
     781     792    1460     795     818    1460
Bank Sta=1001.6,1226
XS Rating Curve= 0 ,0
Exp/Cntr(USF)=0,0
Exp/Cntr=0.3,0.1

Type RM Length L Ch R = 1 ,47512   ,1254.5,913.1,642.8
BEGIN DESCRIPTION:
Channel burn based on effective XS AV
END DESCRIPTION:
Node Name=N
XS GIS Cut Line= 2
2024135.98379172220675.3913895642025589.10883822221373.307972729
#Sta/Elev= 30
       0 1628.49   114.3 1519.12   146.2 1495.69   208.9 1441.14   216.2 1436.78
   256.2 1435.56   270.8 1429.01   288.9 1427.56   532.8 1429.74   571.6 1420.75
   609.3 1418.68     642 1421.62   679.8 1413.65   682.1 1413.14   685.7  1407.3
     933  1407.3   933.2 1412.89   940.5 1414.32   962.5 1419.75   989.6 1420.49
  1002.4  1412.9  1053.5 1413.05  1067.9 1421.47  1104.3 1423.74  1126.1 1428.65
  1162.5 1448.41  1231.6 1493.06  1271.7 1511.91  1337.2 1522.18    1612 1528.84
#Mann= 5 ,-1 , 0
       0      .1       0   256.2     .04       0   679.8    .045       0
   940.5     .08       0  1271.7     .04       0
#Block Obstruct= 2 ,-1
  456.12  505.16 1448.61  1311.9    1390 1543.13
Bank Sta=679.8,940.5
XS Rating Curve= 0 ,0
Exp/Cntr=0.3,0.1

Type RM Length L Ch R = 1 ,46599   ,978.9,873.7,707.3
BEGIN DESCRIPTION:
Channel burn based on effective XS AU
END DESCRIPTION:
XS GIS Cut Line= 2
2024339.10871355222232.6828943942025542.23360389221508.724696651
#Sta/Elev= 30
       0 1790.86      67 1740.37    78.4 1726.06   143.5 1680.19   220.1 1614.62
   275.1 1571.54     289 1556.48   300.5 1552.11   354.1 1509.79   423.7 1465.24
   438.4 1456.29   455.5 1440.15   504.6 1437.19   531.9 1417.15   544.6 1412.52
   545.2  1407.1   775.3  1407.1   777.8 1412.48   796.2  1412.9   828.9 1424.16
   848.1 1425.44   856.4 1425.26   867.2  1417.8   881.8 1414.53   974.4 1419.31
  1011.4 1415.94    1028 1426.26  1238.6 1503.39  1288.4 1513.79  1404.1 1523.93
#Mann= 4 ,-1 , 0
       0      .1       0   423.7     .04       0   544.6    .045       0
   777.8      .1       0
#Block Obstruct= 1 ,-1
 1253.56 1282.49 1532.72
Bank Sta=544.6,777.8
XS Rating Curve= 0 ,0
Exp/Cntr=0.3,0.1

Type RM Length L Ch R = 1 ,45725   ,849.6,815.3,775.9
BEGIN DESCRIPTION:
Channel burn based on effective XS AT
END DESCRIPTION:
XS GIS Cut Line= 2
2025469.31708306222753.5164983872025917.23383814221628.516451806
#Sta/Elev= 30
       0 1613.14      33 1590.62      40 1579.98    47.1 1573.58    68.3 1566.17
   150.8 1501.54   156.6 1493.68     160 1486.19   177.7 1437.71   181.3 1432.28
   225.6 1428.81   241.3 1418.75     259 1412.35   262.5 1411.83   266.1  1406.8
   527.3  1406.8   528.7 1411.65   566.2 1414.87   594.4 1420.99   622.7 1424.14
   763.6 1425.27   796.4 1433.21   848.7 1439.56   950.5 1460.68   982.9 1469.26
  1042.9 1501.42  1071.7 1512.85  1099.4 1520.37    1170 1528.08  1210.9 1529.51
#Mann= 3 , 0 , 0
       0      .1       0     259    .045       0   528.7      .1       0
#Block Obstruct= 2 ,-1
  658.02  701.56 1444.96 1073.21 1097.28 1539.84
Bank Sta=259,528.7
XS Rating Curve= 0 ,0
Exp/Cntr=0.3,0.1

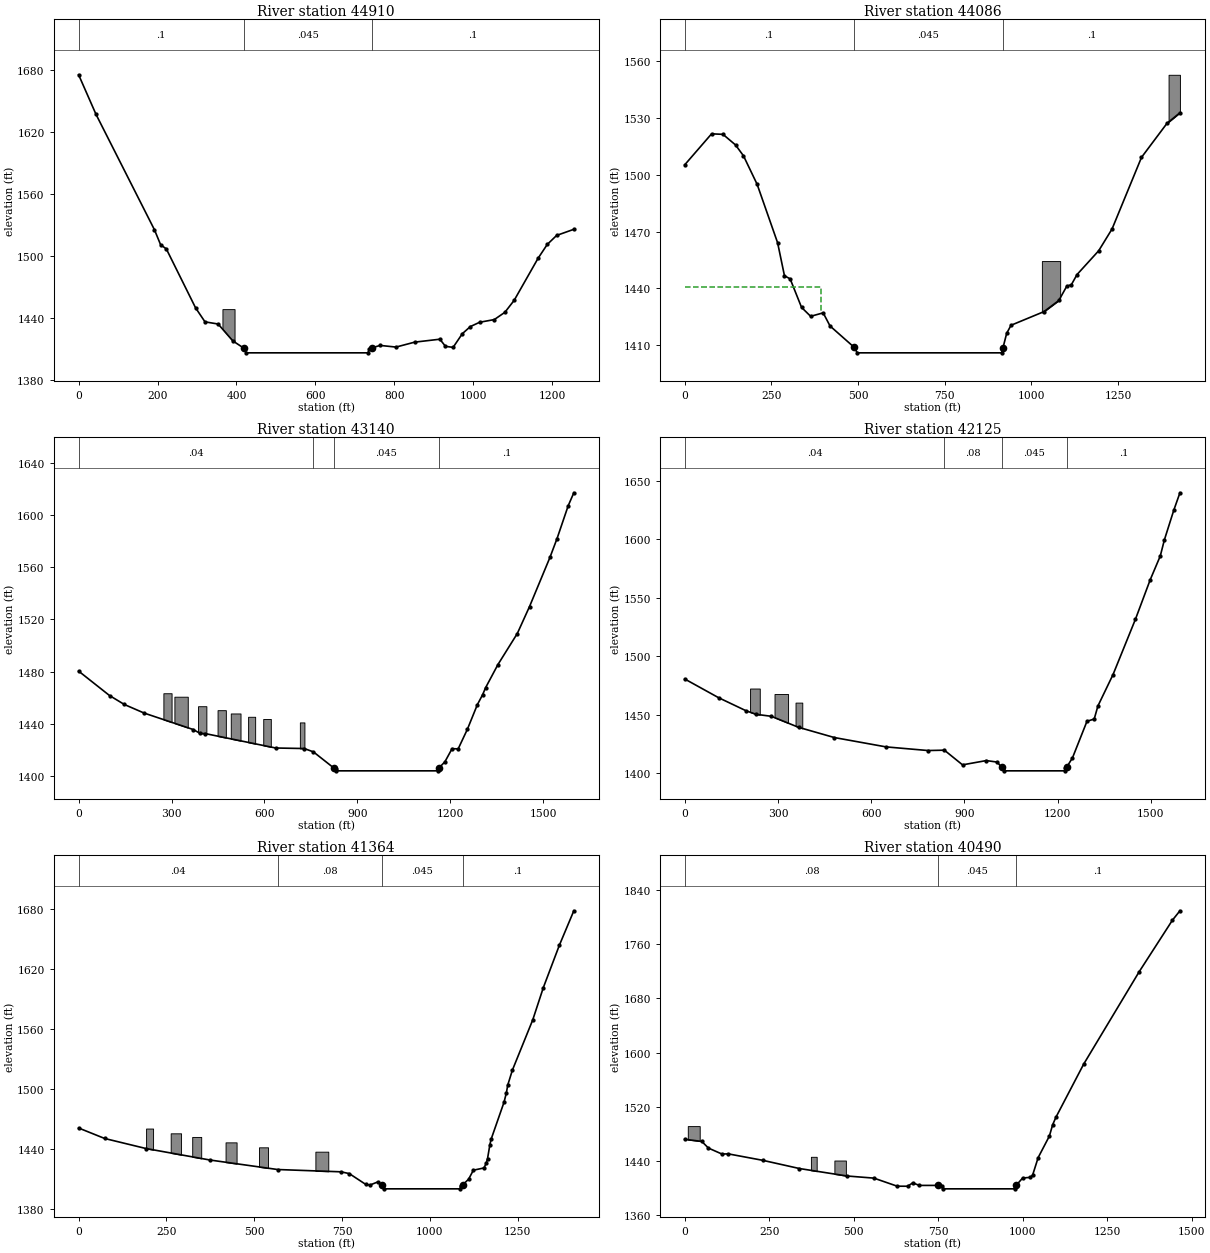
Type RM Length L Ch R = 1 ,44910   ,867.2,824.4,769.4
BEGIN DESCRIPTION:
Channel burn based on effective XS AS
END DESCRIPTION:
XS GIS Cut Line= 2
2026297.44206722223097.2664670652026573.48383798221873.307956979
#Sta/Elev= 30
       0 1675.78    44.1 1637.42   192.1 1525.66   207.7 1511.17   222.3 1507.04
   296.3 1450.01   320.2 1436.41   353.5 1434.32   390.5 1418.02     419 1410.83
   424.1  1406.4   733.5  1406.4   736.2 1410.42   743.6 1411.25   763.8 1413.59
   804.2 1411.98   851.3 1416.75   915.2  1419.6   929.5 1412.71   948.8 1411.69
   972.3 1424.99   992.5 1431.84  1016.1 1436.03  1053.1  1438.6    1080 1445.67
  1103.5 1457.25    1164 1497.95  1187.4 1511.42  1211.1 1520.14  1254.7 1526.08
#Mann= 3 ,-1 , 0
       0      .1       0     419    .045       0   743.6      .1       0
#Block Obstruct= 1 ,-1
  364.41  395.07 1448.76
Bank Sta=419,743.6
XS Rating Curve= 0 ,0
Exp/Cntr=0.3,0.1

Type RM Length L Ch R = 1 ,44086   ,932.6,945.7,953.9
BEGIN DESCRIPTION:
Channel burn based on effective XS AR
END DESCRIPTION:
Node Name=M
XS GIS Cut Line= 2
2027214.10886906223305.5997118062027276.60874406221878.516279891
#Sta/Elev= 30
       0 1505.14    77.5 1521.47   110.4 1521.19   146.5 1515.62   169.5 1509.88
   208.9 1494.86     268 1464.04   287.7 1446.71   304.1 1445.07     337 1430.04
   363.2 1425.34   399.4 1427.16   419.1 1420.26     488 1409.14   497.9  1406.1
   914.9  1406.1     915 1408.54   918.2 1408.88   928.7 1416.37   941.2 1420.62
  1036.4 1427.82  1079.1 1433.68  1102.1 1441.22  1115.3 1441.99  1131.7 1447.35
  1194.1 1459.87  1232.7 1471.36  1317.6 1509.06  1391.1 1526.98  1428.5 1532.57
#Mann= 3 ,-1 , 0
       0      .1       0     488    .045       0   918.2      .1       0
#XS Ineff= 2 , 0
          393.01  1440.8
Permanent Ineff=
       F       F
#Block Obstruct= 2 ,-1
 1030.25 1083.01 1454.44  1395.7 1428.45 1552.57
Bank Sta=488,918.2
XS Rating Curve= 0 ,0
Exp/Cntr=0.3,0.1

Type RM Length L Ch R = 1 ,43140   ,696.2,1014.6,1155.2
BEGIN DESCRIPTION:
Channel burn based on effective XS AQ
END DESCRIPTION:
XS GIS Cut Line= 2
2028109.94205114223586.8498054742028240.15045214221993.099712148
#Sta/Elev= 30
       0 1480.43    99.8 1461.71   147.7 1454.85   211.8 1448.25   369.8 1435.68
   392.8 1432.66   409.3 1432.53   636.4  1421.5   728.7 1421.09   758.2 1418.53
   823.1 1406.37   830.6 1405.64   832.2    1404  1159.8    1404  1160.9 1405.77
  1163.9 1406.29  1182.8 1410.94  1205.9 1420.98  1225.6 1420.83  1255.3 1435.81
  1287.6 1454.72  1304.6 1462.37  1314.5 1467.86    1354 1485.45  1416.6 1509.25
  1456.1 1529.94  1521.9 1567.53  1544.9 1582.01  1581.1 1607.29  1599.1  1617.1
#Mann= 4 ,-1 , 0
       0     .04       0   758.2     .08       0   823.1    .045       0
  1163.9      .1       0
#Block Obstruct= 8 ,-1
  273.74  300.19 1463.47   309.3  352.45 1460.82  385.63  412.55 1453.53
  448.66  475.44 1450.49  491.33  522.84 1447.97   547.3  570.06 1445.43
  596.16  620.63 1443.76  714.43  729.15 1441.11
Bank Sta=823.1,1163.9
XS Rating Curve= 0 ,0
Exp/Cntr=0.3,0.1

Type RM Length L Ch R = 1 ,42125   ,580.3,761.4,848.2
BEGIN DESCRIPTION:
Channel burn based on effective XS AP
END DESCRIPTION:
XS GIS Cut Line= 2
2028250.56709798  223685.80794092029474.52527997222664.974680722
#Sta/Elev= 30
       0 1480.68   108.9  1464.7   197.7 1453.49   230.1 1450.48   278.9 1448.79
   366.2  1439.4   481.6 1430.64   647.9 1422.66     783 1419.55   835.7 1419.85
   894.1 1407.31   970.6 1410.97  1005.8 1409.67  1019.7 1405.23  1024.4 1404.64
  1026.5  1402.2    1223  1402.2  1224.7 1404.55  1229.4 1405.35    1248 1413.33
  1294.6 1444.54  1317.9 1446.47  1329.8 1457.62  1378.5 1484.46  1450.7 1531.81
  1498.2  1565.5  1530.6 1585.82  1543.8  1599.6  1574.1 1624.98  1593.8 1639.77
#Mann= 4 ,-1 , 0
       0     .04       0   835.7     .08       0  1019.7    .045       0
  1229.4      .1       0
#Block Obstruct= 3 ,-1
  210.29  241.53 1472.53  288.99   332.6 1467.83  356.62  378.35  1460.5
Bank Sta=1019.7,1229.4
XS Rating Curve= 0 ,0
Exp/Cntr=0.3,0.1

Type RM Length L Ch R = 1 ,41364   ,781.5,874.2,921.5
BEGIN DESCRIPTION:
Channel burn based on effective XS AO
END DESCRIPTION:
Node Name=L
XS GIS Cut Line= 2
2028500.56692605223873.3078939772029875.56712881223560.807862803
#Sta/Elev= 30
       0 1461.44    74.3 1450.95     192  1440.9   373.7 1429.44   566.7 1419.92
   747.2 1417.62   770.7 1415.84   817.8 1404.99   829.9 1404.44   851.5 1407.47
   862.8 1404.35   868.2  1400.6    1087  1400.6  1087.6 1403.72  1093.1 1404.39
  1110.5 1410.26    1124 1419.24  1154.3  1421.5    1161 1426.52  1164.4 1430.86
  1171.1 1444.81  1174.5 1450.11  1211.5 1487.39  1218.2  1496.9  1221.9 1504.31
    1235 1519.19  1293.2 1569.66  1323.3 1601.89    1369 1644.31  1410.1 1678.68
#Mann= 4 ,-1 , 0
       0     .04       0   566.7     .08       0   862.8    .045       0
  1093.1      .1       0
#Block Obstruct= 6 ,-1
  192.08  212.01  1460.9  262.17  291.69 1456.12  323.47  349.08  1452.5
  418.41  449.81 1447.08  513.65  539.37 1442.12   674.2   710.9 1437.77
Bank Sta=862.8,1093.1
XS Rating Curve= 0 ,0
Exp/Cntr=0.3,0.1

Type RM Length L Ch R = 1 ,40490   ,973.7,983,987.9
BEGIN DESCRIPTION:
Channel burn based on effective XS AN
END DESCRIPTION:
XS GIS Cut Line= 2
2028630.77532706224493.0996333962030094.31701939224566.016482309
#Sta/Elev= 30
       0 1472.14    50.5 1468.99    70.2 1459.17   109.7 1450.49   129.4 1450.59
   231.2  1441.1   339.6 1429.01   480.3 1418.03   559.9 1414.89   628.7    1403
   659.7 1402.94   674.7 1407.91   694.4 1404.14   750.4 1404.16   760.4 1403.13
   762.9  1399.1   976.9  1399.1   978.2 1403.23   981.6 1404.73   999.9 1415.02
  1022.9 1416.04  1029.4 1419.23  1045.9  1445.2    1079  1476.8  1088.8  1493.6
  1098.4 1504.59  1180.5 1582.88  1344.6 1718.95  1443.3 1795.18  1465.4 1808.94
#Mann= 3 ,-1 , 0
       0     .08       0   750.4    .045       0   981.6      .1       0
#Block Obstruct= 3 ,-1
    9.09   44.35 1491.57  373.38  390.48 1446.31  442.89  476.87 1440.84
Bank Sta=750.4,981.6
XS Rating Curve= 0 ,0
Exp/Cntr=0.3,0.1

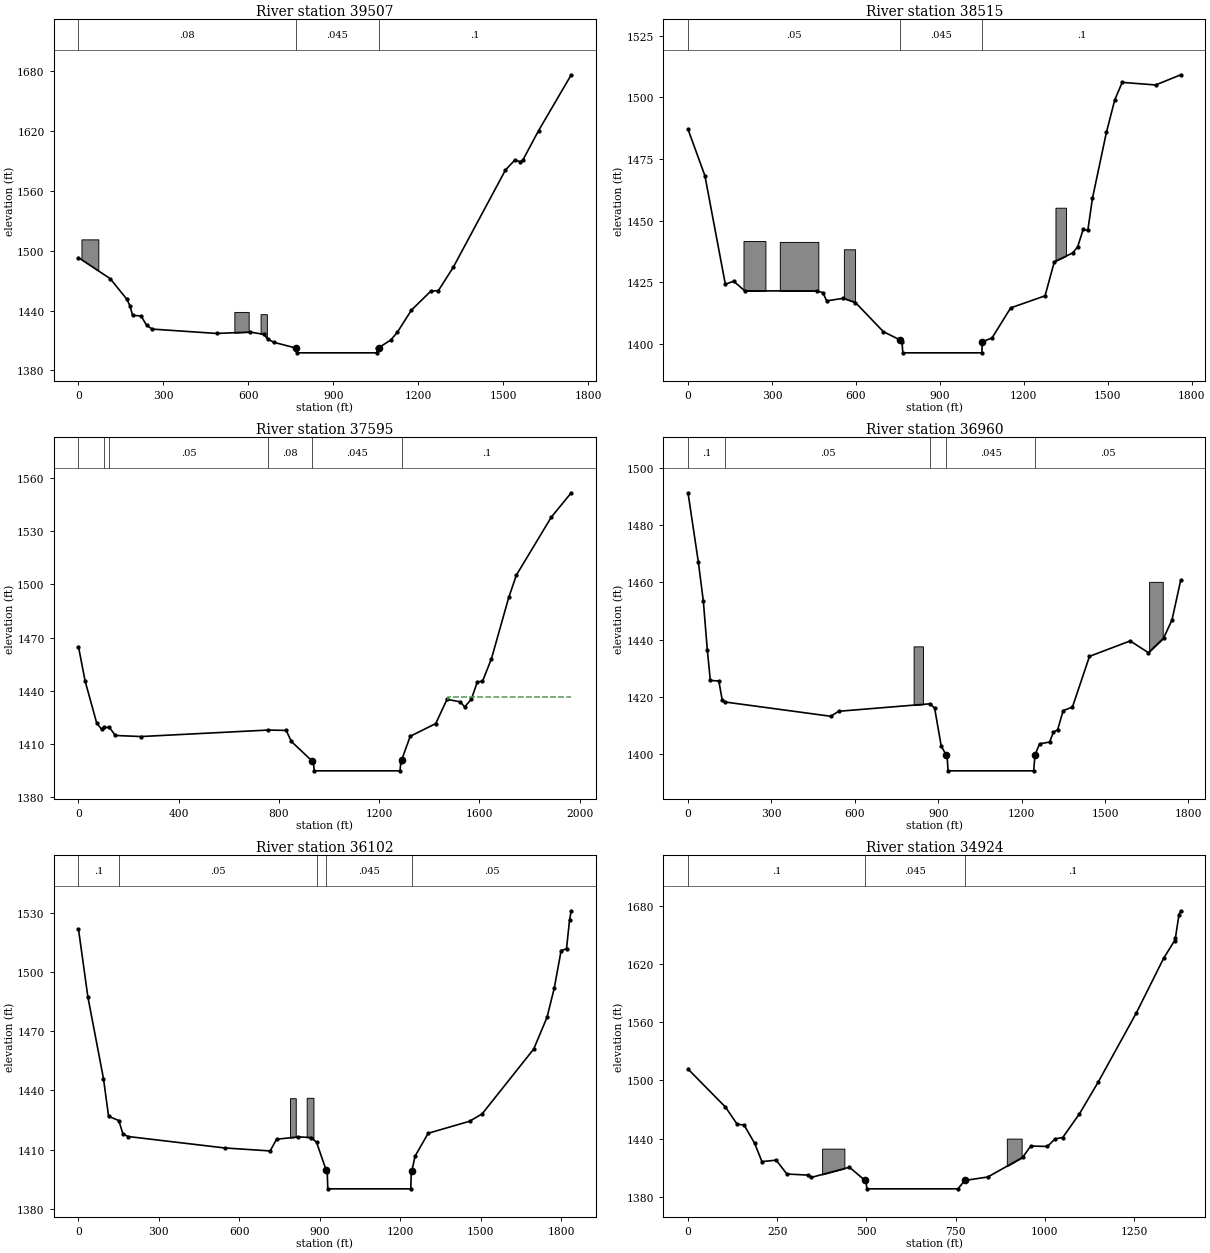
Type RM Length L Ch R = 1 ,39507   ,969.3,992.1,1012.9
BEGIN DESCRIPTION:
Channel burn based on effective XS AM
END DESCRIPTION:
XS GIS Cut Line= 2
2028500.56692605225441.0163727252030234.94206622 225581.64141956
#Sta/Elev= 30
       0 1493.12   112.2 1471.96   171.4 1451.06   181.3  1444.9   191.2 1435.06
   220.8  1434.6   240.5  1425.2   260.3 1421.34   487.4 1416.98   605.9 1418.34
   655.3 1416.02   668.4 1411.19   691.5 1407.97   767.2 1402.31   770.5  1397.5
  1053.6  1397.5  1055.3 1401.94 1059.931402.599  1102.9 1410.43    1126 1418.16
  1175.3 1440.26  1244.5 1459.55  1270.8 1459.91  1323.5 1483.47  1507.8 1581.07
  1540.7 1591.05  1560.7 1589.37  1569.8  1591.4  1624.6 1620.57  1740.1  1676.7
#Mann= 3 ,-1 , 0
       0     .08       0   767.2    .045       0 1059.93      .1       0
#Block Obstruct= 3 ,-1
   10.46      70 1511.44  550.41  600.91 1438.57  643.01  665.24 1436.32
Bank Sta=767.2,1059.93
XS Rating Curve= 0 ,0
Exp/Cntr=0.3,0.1

Type RM Length L Ch R = 1 ,38515   ,876.6,920,947.6
BEGIN DESCRIPTION:
Channel burn based on effective XS AL
END DESCRIPTION:
XS GIS Cut Line= 2
2028375.56717606226352.4745235592030115.15031105226628.516294315
#Sta/Elev= 30
       0 1487.06    60.4 1468.21   133.4 1424.16   163.1 1425.38   203.2 1421.46
   462.3 1421.44   482.2 1420.72   495.5  1417.4   555.3 1418.44   598.5 1416.72
   698.2  1404.9     758 1401.53   764.6 1400.88   767.9  1396.3  1050.3  1396.3
  1052.1 1400.77  1086.8 1402.39  1153.3 1414.55  1276.2 1419.45  1309.4 1433.33
  1375.8  1436.9    1393 1439.45  1412.4 1446.38    1429 1446.03  1445.6 1459.05
  1495.4 1485.78  1525.3    1499  1551.9 1506.12  1671.5 1505.06  1761.3  1509.2
#Mann= 3 , 0 , 0
       0     .05       0     758    .045       0  1052.1      .1       0
#Block Obstruct= 4 ,-1
  198.27  276.73 1441.69  328.06  465.72 1441.34  557.06  597.13 1438.34
  1313.4 1351.17 1455.23
Bank Sta=758,1052.1
XS Rating Curve= 0 ,0
Exp/Cntr=0.3,0.1

Type RM Length L Ch R = 1 ,37595   ,575.9,634.2,671.7
BEGIN DESCRIPTION:
Channel burn based on linear interpolation between effective XS AD and AE
END DESCRIPTION:
Node Name=K
XS GIS Cut Line= 2
2028181.05876974227137.7963329652030083.90037355227633.724585727
#Sta/Elev= 30
       0 1464.88    26.3 1445.64    72.8 1421.82    93.1 1418.29   101.6 1419.55
   123.2 1419.42   147.3 1414.91   249.1 1414.31   757.6 1417.97   828.8 1417.76
   849.3 1411.58     930  1400.8   937.3 1399.83   940.71394.998  1283.11394.998
  1286.5  1400.2  1289.1 1400.95  1323.8 1414.46  1425.5 1421.62  1470.6 1435.25
  1523.9 1433.84  1540.8 1430.99  1567.9 1435.35  1591.7 1445.17    1612 1445.32
  1648.1 1458.21  1717.1 1492.73  1747.6 1505.28  1886.6 1537.83  1966.4 1551.59
#Mann= 6 ,-1 , 0
       0      .1       0   101.6    .016       0   123.2     .05       0
   757.6     .08       0     930    .045       0  1289.1      .1       0
#XS Ineff= 2 , 0
                         1476.06         1436.76
Permanent Ineff=
       F       F
Bank Sta=930,1289.1
XS Rating Curve= 0 ,0
Exp/Cntr=0.3,0.1

Type RM Length L Ch R = 1 ,36960   ,808.1,858.3,888.9
BEGIN DESCRIPTION:
Channel burn based on effective XS AK
END DESCRIPTION:
XS GIS Cut Line= 2
2028063.06714489227581.6413565582029688.06717572228289.974585563
#Sta/Elev= 30
       0 1491.38    37.3 1467.05    55.2 1453.37    69.5 1436.33    80.3 1425.72
   110.9 1425.53   123.2 1418.76   133.9 1418.17   513.3 1413.19   542.1 1414.94
   871.1 1417.56   887.2 1416.03   910.9  1402.8   928.7 1399.63     932 1399.17
   935.6  1394.1  1243.4  1394.1  1248.4 1399.74  1264.9 1403.53  1300.7 1404.18
  1314.7 1407.63  1329.7 1408.48  1349.6 1415.16    1383 1416.43  1444.3 1434.15
  1590.6 1439.55  1656.2 1435.44    1711 1440.56  1741.1 1446.89  1772.7  1460.9
#Mann= 5 ,-1 , 0
       0      .1       0   133.9     .05       0   871.1     .08       0
   928.7    .045       0  1248.4     .05       0
#Block Obstruct= 2 ,-1
  811.58  845.43 1437.65 1658.81 1707.77 1460.22
Bank Sta=928.7,1248.4
XS Rating Curve= 0 ,0
Exp/Cntr=0.3,0.1

Type RM Length L Ch R = 1 ,36102   ,952.3,1177.8,1327.9
BEGIN DESCRIPTION:
Channel burn based on effective XS AJ
END DESCRIPTION:
XS GIS Cut Line= 2
2027797.44201997228243.0996793062029375.56714456229185.808095723
#Sta/Elev= 30
       0 1521.68    34.8 1487.52    93.2 1446.01   112.3 1426.88   150.5 1424.79
   165.8 1417.97   184.9 1416.69   545.1  1410.9   714.9 1409.39     739  1415.3
   820.2 1416.52     868 1416.15   888.1 1413.78   923.1 1399.97   927.9 1398.65
   930.1  1390.2  1239.7  1390.2  1241.3 1398.59  1243.5 1399.17  1255.6 1406.77
  1304.6 1418.34    1459 1424.41  1506.2 1428.21  1698.3 1460.99    1748 1477.06
  1774.8 1491.76  1800.5 1510.81  1820.6 1511.77    1832 1526.38  1838.3 1530.97
#Mann= 5 ,-1 , 0
       0      .1       0   150.5     .05       0   888.1     .08       0
   923.1    .045       0  1243.5     .05       0
#Block Obstruct= 2 ,-1
  788.84   810.5 1436.08  851.32  876.58 1436.29
Bank Sta=923.1,1243.5
XS Rating Curve= 0 ,0
Exp/Cntr=0.3,0.1

Type RM Length L Ch R = 1 ,34924   ,1154.6,1157.8,1162.4
BEGIN DESCRIPTION:
Channel burn based on effective XS AI
END DESCRIPTION:
XS GIS Cut Line= 2
2027537.02521797228873.3080645652028089.10875948 230138.93315798
#Sta/Elev= 30
       0 1511.65     105 1472.47   137.3 1455.06   157.3 1453.86   186.8 1435.11
   207.1 1416.34     247 1417.84     277 1403.58   336.7 1402.42   344.9    1400
   452.3 1410.56   495.2 1397.21   498.7 1396.44   501.2  1388.3   756.5  1388.3
   775.4 1396.91   840.2 1400.51   937.4 1420.63   960.5 1432.38  1007.1 1431.94
  1028.5 1439.77    1050 1441.15  1096.9 1465.59  1149.2 1498.07  1256.4 1569.54
  1332.8 1625.73  1363.5 1643.87    1366 1647.05  1375.7 1670.66  1380.8 1674.61
#Mann= 3 , 0 , 0
       0      .1       0   495.2    .045       0   775.4      .1       0
#Block Obstruct= 2 ,-1
  375.78  438.16 1429.71  893.35  934.91 1440.04
Bank Sta=495.2,775.4
XS Rating Curve= 0 ,0
Exp/Cntr=0.3,0.1