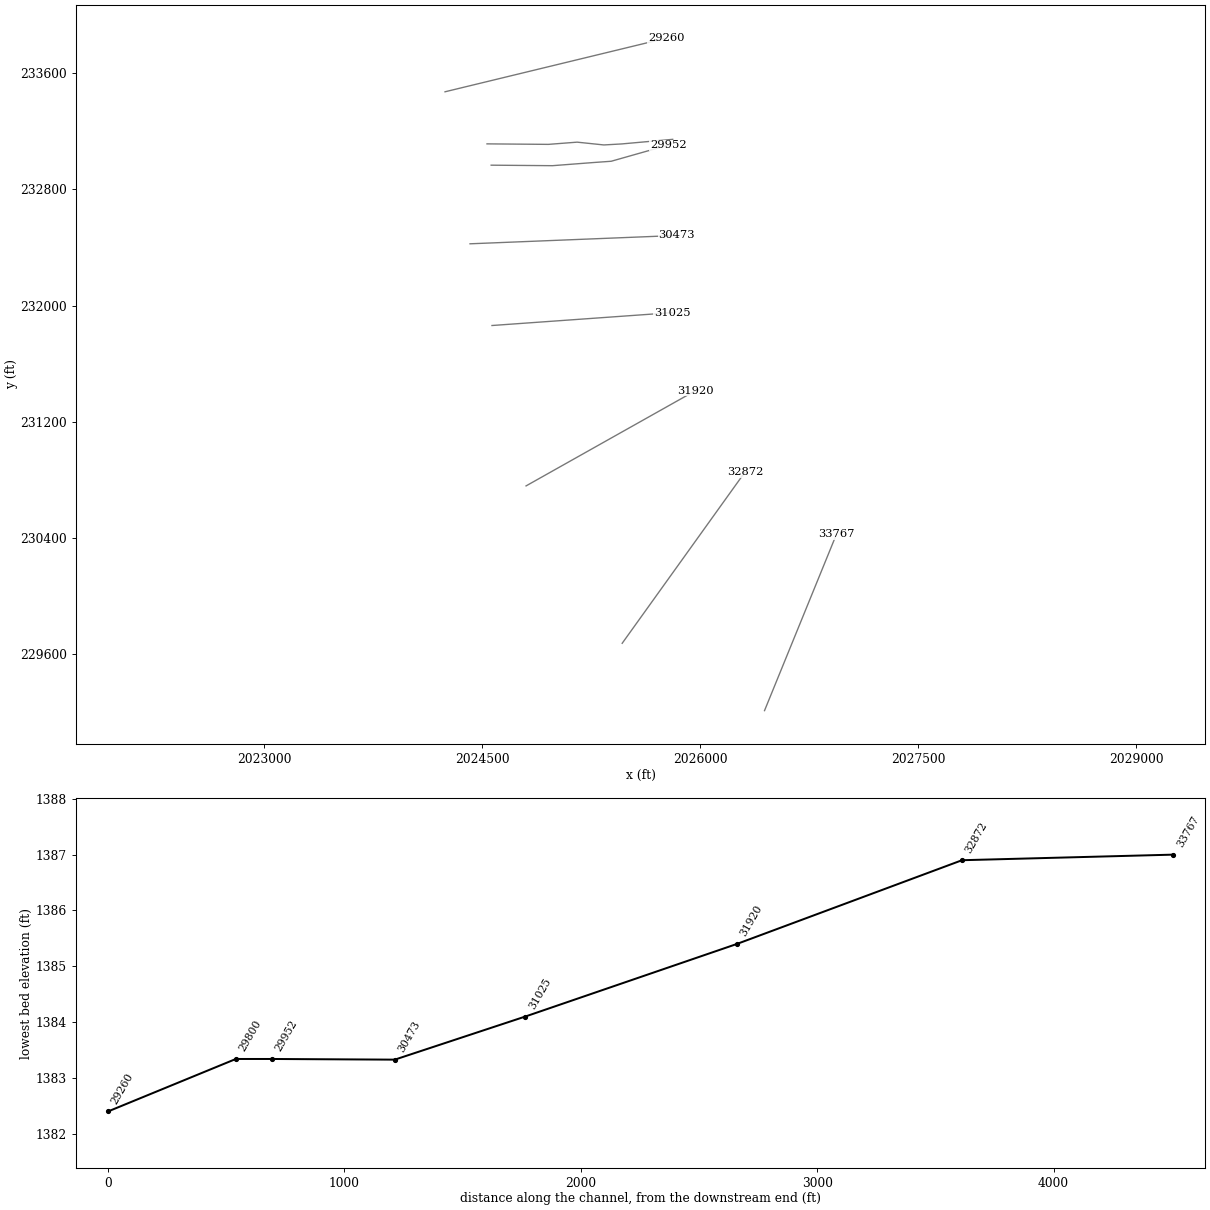
HEC-RAS study GREENBRRV.prj: GREENBRRV

--- GREENBRRV.g01 (geometry) --- (continued)

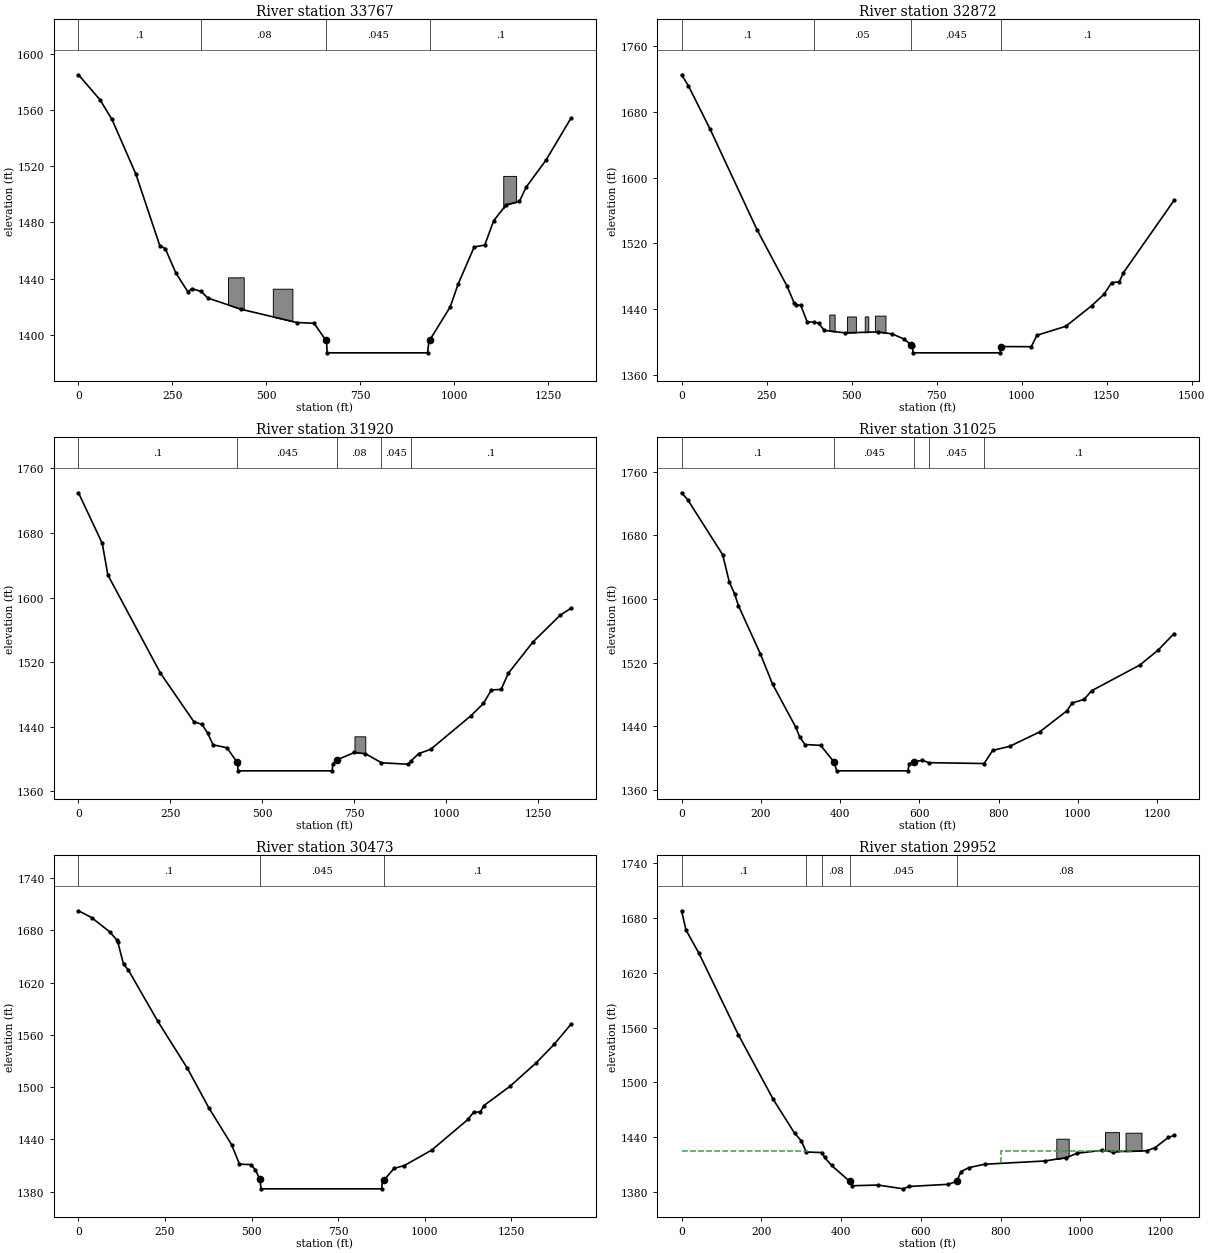
Type RM Length L Ch R = 1 ,33767   ,966.1,894.4,846.8
BEGIN DESCRIPTION:
Channel burn based on effective XS AH
END DESCRIPTION:
Node Name=J
XS GIS Cut Line= 2
2026443.27543697229211.849710315 2026938.0670983230425.391246483
#Sta/Elev= 30
       0 1585.31    57.3 1567.47    89.2 1553.42   152.9 1514.35   216.7 1463.18
   230.9 1461.39   259.2 1443.91   291.1 1430.52   301.7 1432.78   326.5 1430.76
   344.3 1426.09   432.8 1418.07   581.6 1408.62   626.9 1408.11   657.7 1396.16
   660.2 1395.42   661.6    1387   928.9    1387   932.4 1395.25   934.5 1395.98
   989.1 1419.75  1010.3 1436.08    1053  1462.5  1081.2 1463.88  1104.8 1481.23
  1138.4 1492.69  1173.3 1494.99  1191.2 1505.14  1244.2  1524.5  1310.5 1554.37
#Mann= 4 ,-1 , 0
       0      .1       0   326.5     .08       0   657.7    .045       0
   934.5      .1       0
#Block Obstruct= 3 ,-1
  397.88  439.67 1440.84  517.16  569.24 1432.74 1130.32 1164.56 1513.19
Bank Sta=657.7,934.5
XS Rating Curve= 0 ,0
Exp/Cntr=0.3,0.1

Type RM Length L Ch R = 1 ,32872   ,1072.7,952.4,833.7
BEGIN DESCRIPTION:
Channel burn based on effective XS AG
END DESCRIPTION:
XS GIS Cut Line= 2
2025464.10876013229675.3914341482026307.85871306230852.474709898
#Sta/Elev= 30
       0 1724.98    19.9 1711.75    84.3 1658.49   221.5 1536.84   310.3 1467.89
   330.5 1448.07     335 1445.57   350.7 1444.51   369.3 1424.62     389 1424.18
   403.2 1422.87   419.6 1414.27   479.9 1411.19   577.7 1412.35   619.5 1409.91
   654.7 1403.56   673.6    1397   679.1 1394.84   680.6  1386.9   936.9  1386.9
   939.2 1394.55  1028.2 1394.37    1045 1408.24  1129.8 1419.18  1206.5 1444.35
  1242.2 1458.09  1264.7  1472.2  1287.3 1473.37  1299.3 1484.32  1448.3 1572.32
#Mann= 4 ,-1 , 0
       0      .1       0     389     .05       0   673.6    .045       0
   939.2      .1       0
#Block Obstruct= 4 ,-1
   434.4  450.02 1433.47  486.42  512.53 1431.11  538.66     549 1431.17
  568.45  599.58 1432.16
Bank Sta=673.6,939.2
XS Rating Curve= 0 ,0
Exp/Cntr=0.3,0.1

Type RM Length L Ch R = 1 ,31920   ,974,895.1,756.3
BEGIN DESCRIPTION:
Channel burn based on effective XS AF
END DESCRIPTION:
XS GIS Cut Line= 2
2024802.65043738230758.7245693062025969.31706731231414.974569142
#Sta/Elev= 30
       0 1729.77    64.7 1667.07    79.8 1627.99   222.8 1506.41   313.2  1446.5
   335.8 1442.83   350.8 1432.34   365.9 1417.59   403.5    1414   430.9 1396.11
   432.8 1394.34   433.6  1385.4   689.6  1385.4   691.1 1393.77   701.4 1398.67
   749.8 1408.15     780 1406.68   823.6 1395.37   895.9 1393.58   903.1 1397.28
   924.8 1406.78   956.9 1411.94  1066.9  1453.7  1100.7 1468.85  1122.4 1485.63
  1148.9 1486.16  1168.1 1506.11  1235.8 1545.31  1309.5 1578.22  1338.6  1586.8
#Mann= 5 ,-1 , 0
       0      .1       0   430.9    .045       0   701.4     .08       0
   823.6    .045       0   903.1      .1       0
#Block Obstruct= 1 ,-1
  750.18  779.53 1428.13
Bank Sta=430.9,701.4
XS Rating Curve= 0 ,0
Exp/Cntr=0.3,0.1

Type RM Length L Ch R = 1 ,31025   ,558.7,552.1,545
BEGIN DESCRIPTION:
Channel burn based on effective XS AE
END DESCRIPTION:
Node Name=I
XS GIS Cut Line= 2
2024568.27524997231862.8913242222025807.85872881231951.433141887
#Sta/Elev= 30
       0 1733.52    15.3  1724.9   103.6 1655.71   120.5  1621.2   133.7 1606.54
   143.5 1591.57   198.8 1531.05   229.5 1493.16   288.3 1438.78   298.1 1426.55
   311.3 1417.16   350.8 1416.11   384.4 1395.36   391.5  1384.1   571.1  1384.1
   574.4  1393.2   585.6 1395.35   607.3  1397.4   623.8 1394.36   763.4  1393.3
   784.9 1409.75   827.7 1414.87   903.3 1432.92   972.4 1459.56   985.6 1469.46
  1015.2 1473.75  1034.9 1484.79  1156.6 1517.14  1202.7 1535.87  1242.7 1556.64
#Mann= 5 ,-1 , 0
       0      .1       0   384.4    .045       0   585.6     .08       0
   623.8    .045       0   763.4      .1       0
Bank Sta=384.4,585.6
XS Rating Curve= 0 ,0
Exp/Cntr=0.3,0.1

Type RM Length L Ch R = 1 ,30473   ,518.2,521,530.3
BEGIN DESCRIPTION:
Channel burn based on linear interpolation between effective XS AD and AE
END DESCRIPTION:
XS GIS Cut Line= 2
 2024417.2335573232425.391511559 2025839.1086663232482.683063641
#Sta/Elev= 30
       0 1702.62    38.3  1694.7    90.9 1678.19   110.6 1669.12   113.9  1666.4
   130.3 1640.98   143.4 1635.09   228.8 1575.95   314.8 1521.64   376.5 1476.43
   442.2 1434.16   465.2 1411.69     498 1411.12   511.2  1405.1   524.3 1394.12
   527.61383.328   875.91383.328   878.6 1392.65   882.2 1392.98   911.7  1406.8
   941.3 1410.05  1020.1 1427.65  1125.2 1462.97  1141.6 1471.28  1161.3 1471.66
  1171.1 1478.84  1246.7    1501  1322.2 1527.91  1374.1  1549.1    1423 1572.31
#Mann= 3 ,-1 , 0
       0      .1       0   524.3    .045       0   882.2      .1       0
Bank Sta=524.3,882.2
XS Rating Curve= 0 ,0
Exp/Cntr=0.5,0.3

Type RM Length L Ch R = 1 ,29952   ,146.8,151.2,115.4
BEGIN DESCRIPTION:
Channel burned from survey: 54089GRB032BU
END DESCRIPTION:
XS GIS Cut Line= 6
2024562.62040564 232966.616478982024984.49554613232963.144373059
2025266.61342022 232984.845773222025388.14139238232993.526202068
2025663.76243124 233071.67425477 2025781.3942614233104.888937491
#Sta/Elev= 30
       0 1688.01      11 1666.95    43.8 1641.24   142.3 1552.25   229.9 1481.38
   283.3 1444.39   299.8 1436.22   312.9  1423.7   352.2 1423.07   358.8  1417.7
  376.26 1408.98  422.03  1391.4  427.68 1386.72  493.15  1387.5   556.2 1383.34
  570.05 1385.91  669.45 1388.33  690.23 1391.62  700.94 1402.31  720.84  1406.6
     760 1410.29   911.1 1413.86   965.1 1417.57   992.9 1422.39  1054.3 1425.47
  1081.6 1424.02  1166.8 1425.04  1187.3 1428.35  1221.3 1439.74  1235.4 1441.85
#Mann= 5 ,-1 , 0
       0      .1       0   312.9    .016       0   352.2     .08       0
  422.03    .045       0  690.23     .08       0
#XS Ineff= 2 ,-1
       0     315 1424.63     801  1128.9 1425.07
Permanent Ineff=
       F       F
#Block Obstruct= 3 ,-1
  940.05     971 1438.27 1062.11 1097.27 1445.46 1113.64 1153.64 1444.84
Bank Sta=422.03,690.23
XS Rating Curve= 0 ,0
Exp/Cntr=0.5,0.3

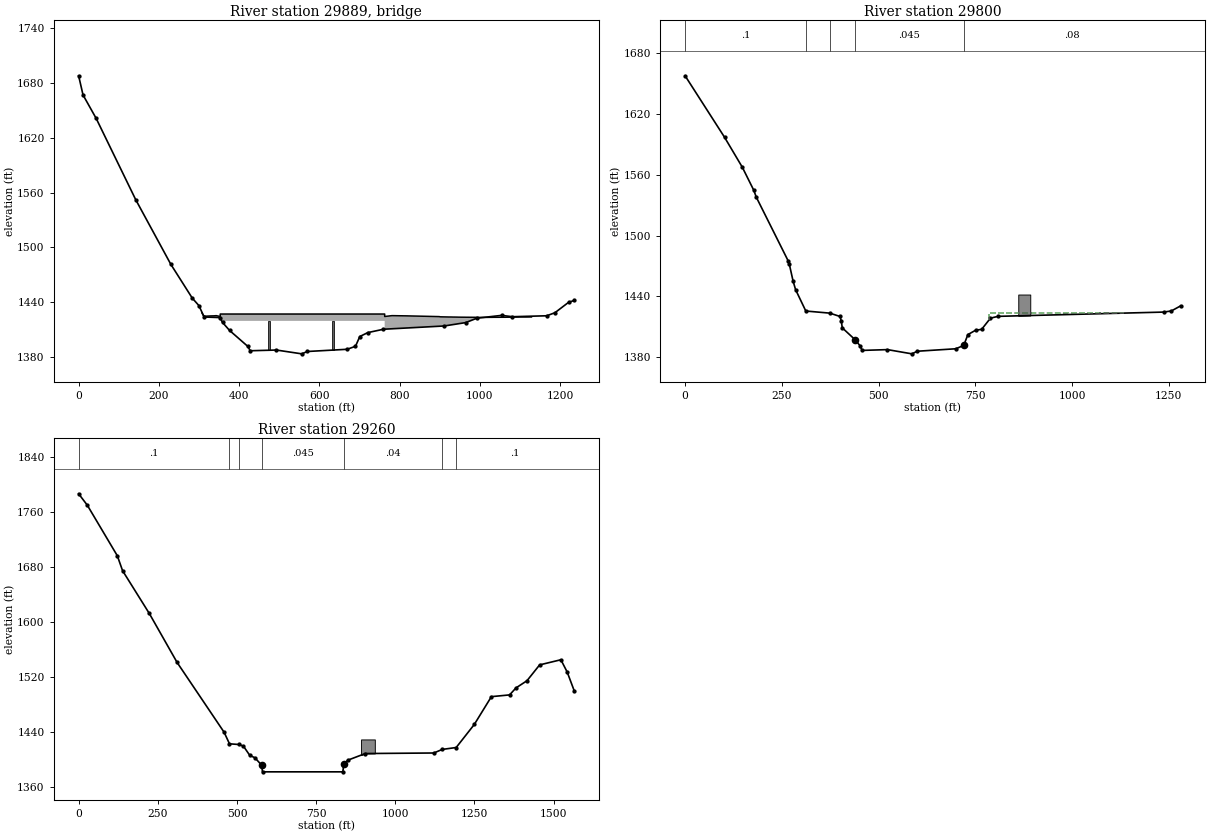
Type RM Length L Ch R = 3 ,29889   ,,,
BEGIN DESCRIPTION:
State Route 3
Survey ID: GRB030
END DESCRIPTION:
Bridge Culvert--1,0,-1,-1, 0
Deck Dist Width WeirC Skew NumUp NumDn MinLoCord MaxHiCord MaxSubmerge Is_Ogee
41,45,2.6,0, 93, 93, , , 0.98, 0, 0,0,,
  307.42  310.69  313.96  317.23  320.51  323.78  327.05  330.32  333.59  336.86
     343     353     353     371     397     557     658     763     763     781
     816     899  901.43  904.68  907.93  911.18  914.43  917.68  920.93  924.18
  927.43  930.68  933.93  937.18  940.43  943.68  946.93  950.18  953.43  956.68
  959.93  963.19  966.44  969.69  972.94  976.19  979.44  982.69  985.94  989.19
  992.44  995.69  998.94 1002.19 1005.44 1008.69 1011.94 1015.19 1018.44 1021.69
 1024.94 1028.19 1031.44 1034.69 1037.94 1041.19 1044.44 1047.69 1050.94 1054.19
 1057.44 1060.69 1063.94 1067.19 1070.44 1073.69 1076.94 1080.19 1083.44 1086.69
 1089.94 1093.19 1096.44 1099.69 1102.94 1106.19 1109.44 1112.69 1115.94 1119.19
 1122.44 1125.69 1128.94
 1428.15 1425.57 1424.64 1424.62  1424.7 1424.75 1424.84 1424.91 1424.93 1424.97
1425.1911424.2651426.9651426.9651426.9651426.9651426.9651426.9651424.2651425.204
1424.9731424.145 1423.92 1423.88 1423.85 1423.82  1423.8 1423.77 1423.73 1423.72
 1423.71 1423.69 1423.64 1423.64 1423.61 1423.59 1423.54 1423.53  1423.5 1423.49
 1423.49 1423.47 1423.44 1423.44 1423.43 1423.43 1423.42  1423.4  1423.4 1423.37
 1423.32 1423.27 1423.27 1423.26 1423.26 1423.26 1423.28 1423.27 1423.28 1423.31
 1423.33 1423.33 1423.35 1423.38 1423.38 1423.38 1423.39  1423.4  1423.4 1423.41
 1423.41 1423.42 1423.42 1423.47 1423.48 1423.49 1423.52 1423.57  1423.6 1423.62
 1423.63 1423.64 1423.67 1423.71 1423.73 1423.72 1423.72  1423.7  1423.7 1423.72
 1423.74 1423.74 1423.74
                                                                                
                1419.4431419.4431419.4431419.4431419.4431419.443
                                                                                
                                                                                
                                                                                
                                                                                
                                                                                
                                                                                
                                                                                
                        
  307.42  310.69  313.96  317.23  320.51  323.78  327.05  330.32  333.59  336.86
     343     353     353     371     397     557     658     763     763     781
     816     899  901.43  904.68  907.93  911.18  914.43  917.68  920.93  924.18
  927.43  930.68  933.93  937.18  940.43  943.68  946.93  950.18  953.43  956.68
  959.93  963.19  966.44  969.69  972.94  976.19  979.44  982.69  985.94  989.19
  992.44  995.69  998.94 1002.19 1005.44 1008.69 1011.94 1015.19 1018.44 1021.69
 1024.94 1028.19 1031.44 1034.69 1037.94 1041.19 1044.44 1047.69 1050.94 1054.19
 1057.44 1060.69 1063.94 1067.19 1070.44 1073.69 1076.94 1080.19 1083.44 1086.69
 1089.94 1093.19 1096.44 1099.69 1102.94 1106.19 1109.44 1112.69 1115.94 1119.19
 1122.44 1125.69 1128.94
 1428.15 1425.57 1424.64 1424.62  1424.7 1424.75 1424.84 1424.91 1424.93 1424.97
1425.191 1424.971426.9651426.9651426.9651426.9651426.9651426.965 1425.191425.204
1424.9731424.145 1423.92 1423.88 1423.85 1423.82  1423.8 1423.77 1423.73 1423.72
 1423.71 1423.69 1423.64 1423.64 1423.61 1423.59 1423.54 1423.53  1423.5 1423.49
 1423.49 1423.47 1423.44 1423.44 1423.43 1423.43 1423.42  1423.4  1423.4 1423.37
 1423.32 1423.27 1423.27 1423.26 1423.26 1423.26 1423.28 1423.27 1423.28 1423.31
 1423.33 1423.33 1423.35 1423.38 1423.38 1423.38 1423.39  1423.4  1423.4 1423.41
 1423.41 1423.42 1423.42 1423.47 1423.48 1423.49 1423.52 1423.57  1423.6 1423.62
 1423.63 1423.64 1423.67 1423.71 1423.73 1423.72 1423.72  1423.7  1423.7 1423.72
 1423.74 1423.74 1423.74
                                                                                
                1419.4431419.4431419.4431419.4431419.4431419.443
                                                                                
                                                                                
                                                                                
                                                                                
                                                                                
                                                                                
                                                                                
                        
Pier Skew, UpSta & Num, DnSta & Num=  ,475, 2 ,475, 2 , 0 , 0 , 0 ,,
       5       5
       0    1429
       5       5
       0    1429
Pier Skew, UpSta & Num, DnSta & Num=  ,635, 2 ,635, 2 , 0 , 0 , 0 ,,
       5       5
       0    1429
       5       5
       0    1429
BR Coef=-1 , 1 , 0 ,0.9, 0 ,,,0.8,0,0.29,0,
WSPro=,,,, 1 ,,,, 0 ,,,, 0 ,,,,-1 ,-1 ,-1 , 0 , 0 , 0 , 0 , 0
BR U #Sta/Elev= 30
       0 1688.01      11 1666.95    43.8 1641.24   142.3 1552.25   229.9 1481.38
   283.3 1444.39   299.8 1436.22   312.9  1423.7   352.2 1423.07   358.8  1417.7
  376.26 1408.98  422.03  1391.4  427.68 1386.72  493.15  1387.5   556.2 1383.34
  570.05 1385.91  669.45 1388.33  690.23 1391.62  700.94 1402.31  720.84  1406.6
     760 1410.29   911.1 1413.86   965.1 1417.57   992.9 1422.39  1054.3 1425.47
  1081.6 1424.02  1166.8 1425.04  1187.3 1428.35  1221.3 1439.74  1235.4 1441.85
BR U #Mann= 5
       0      .1   312.9    .016   352.2     .08  422.03     .04  690.23     .08
BR D #Sta/Elev= 30
       0 1657.49     102 1596.85   147.9 1567.33   177.5 1544.63     184 1537.83
   266.1 1475.24   269.3  1471.9   279.2 1454.95   285.7 1446.56     312 1425.55
   374.1 1423.47   400.6 1420.16   403.9  1415.4  406.26 1408.98  438.95 1397.43
  452.03  1391.4  457.68 1386.72  523.15  1387.5   586.2 1383.34  600.05 1385.91
  699.45 1388.33  720.23 1391.62  730.94 1402.31  750.84  1406.6  766.52  1407.5
   789.3 1418.51     809 1420.31    1237 1424.51  1256.8 1425.61  1280.9 1430.63
BR D #Mann= 5
       0      .1     312    .016   374.1     .08  438.95     .04  720.23     .08
BC Design=,, 0 ,, 0 ,,,,,,
BC Use User HTab Curves=0
BC User HTab FreeFlow(D)= 0

Type RM Length L Ch R = 1 ,29800   ,508.8,540.8,622.2
BEGIN DESCRIPTION:
Channel burned from survey: 54089GRB032BU
END DESCRIPTION:
XS GIS Cut Line= 6
2024533.97479364233113.3179572222024955.84993413233109.845851317
2025154.11495756233125.0971331452025338.08243738233105.913444474
2025460.47851805233112.8579843942025811.60803229233144.484882459
#Sta/Elev= 30
       0 1657.49     102 1596.85   147.9 1567.33   177.5 1544.63     184 1537.83
   266.1 1475.24   269.3  1471.9   279.2 1454.95   285.7 1446.56     312 1425.55
   374.1 1423.47   400.6 1420.16   403.9  1415.4  406.26 1408.98  438.95 1397.43
  452.03  1391.4  457.68 1386.72  523.15  1387.5   586.2 1383.34  600.05 1385.91
  699.45 1388.33  720.23 1391.62  730.94 1402.31  750.84  1406.6  766.52  1407.5
   789.3 1418.51     809 1420.31    1237 1424.51  1256.8 1425.61  1280.9 1430.63
#Mann= 5 ,-1 , 0
       0      .1       0     312    .016       0   374.1     .08       0
  438.95    .045       0  720.23     .08       0
#XS Ineff= 2 ,-1
       0 329.667  1420.1 786.333  1133.3    1424
Permanent Ineff=
       F       F
#Block Obstruct= 1 ,-1
  861.17  892.21 1441.82
Bank Sta=438.95,720.23
XS Rating Curve= 0 ,0
Exp/Cntr=0.5,0.3

Type RM Length L Ch R = 1 ,29260   ,646.1,689.9,790.1
BEGIN DESCRIPTION:
Channel burn based on effective XS AB
END DESCRIPTION:
XS GIS Cut Line= 2
2024245.20333165233471.8343699162025766.01743687233840.699818896
#Sta/Elev= 30
       0 1786.85    27.4 1770.23   122.1 1696.74   138.8 1674.95   223.2 1612.73
     311 1541.48   459.5 1439.93   476.4 1423.15   505.4  1422.2   520.3 1419.88
   540.5 1406.33   556.5 1402.92   577.7 1392.26   580.7  1382.4   834.2  1382.4
   837.6 1393.42   849.9 1399.33   905.1 1409.02  1121.6 1409.81  1148.2    1415
  1192.3 1417.79  1249.5 1451.33  1303.5 1491.77  1360.9 1494.31  1381.1 1504.46
  1415.8 1514.89  1455.8 1537.95  1522.9 1545.43  1542.8 1527.61  1564.9 1500.47
#Mann= 7 ,-1 , 0
       0      .1       0   476.4    .016       0   505.4     .08       0
   577.7    .045       0   837.6     .04       0  1148.2    .016       0
  1192.3      .1       0
#Block Obstruct= 1 ,-1
  891.88  935.37 1429.55
Bank Sta=577.7,837.6
XS Rating Curve= 0 ,0
Exp/Cntr(USF)=0,0
Exp/Cntr=0.3,0.1