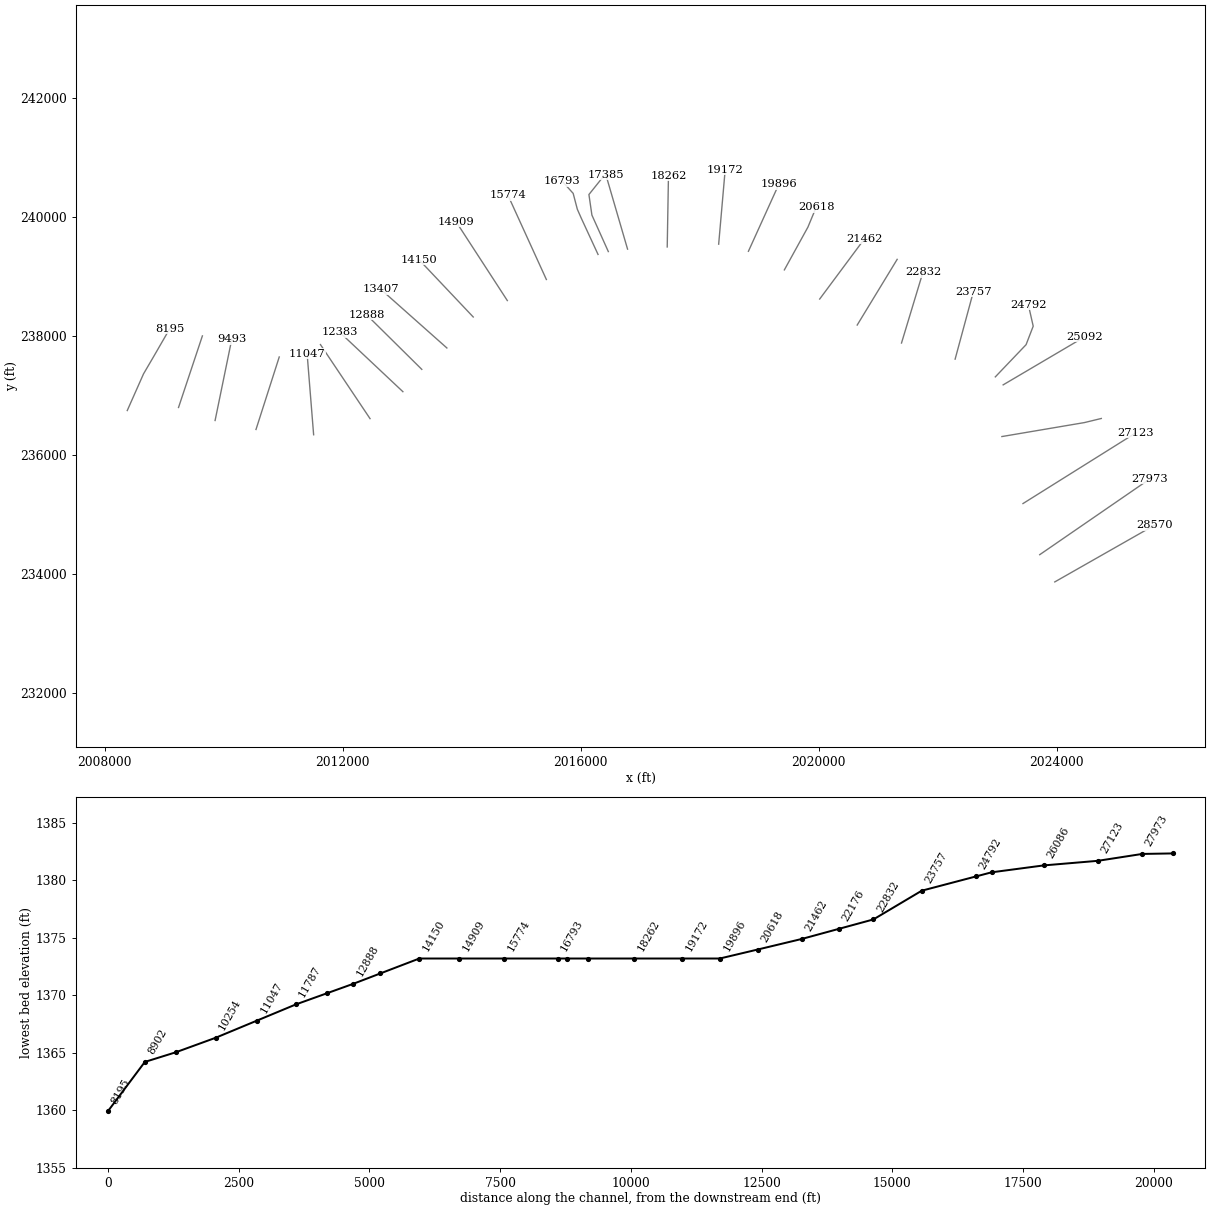
HEC-RAS study GREENBRRV.prj: GREENBRRV

--- GREENBRRV.g01 (geometry) --- (continued)

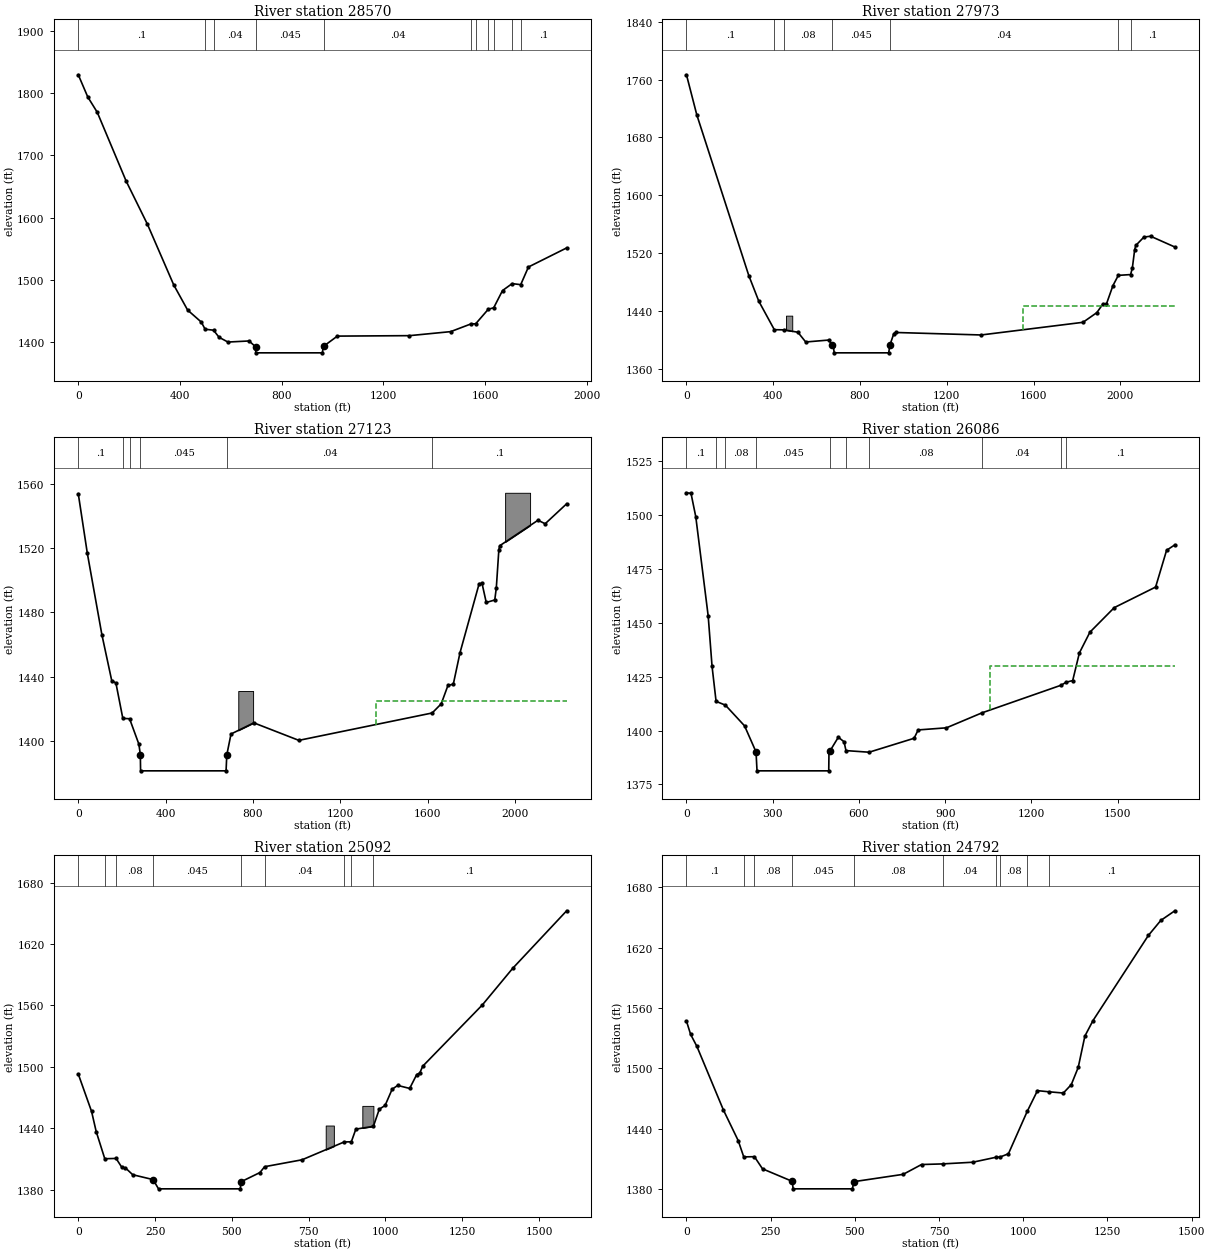
Type RM Length L Ch R = 1 ,28570   ,570,596.6,644.7
BEGIN DESCRIPTION:
Channel burn based on linear interpolation between effective XS AA and AB
END DESCRIPTION:
XS GIS Cut Line= 2
2023967.04250127 233873.958179052025636.00748354 234823.33318708
#Sta/Elev= 30
       0  1829.9    37.3 1794.22    74.7 1769.48   188.3 1658.71     272 1589.19
   375.4 1491.59   429.9  1451.2   483.7 1431.85   498.6 1420.37   531.8 1418.78
   553.5 1407.39   588.4 1399.71   671.5 1401.46   697.7 1391.86   697.81382.346
   960.11382.346   962.5 1392.01   964.9 1393.07  1018.7 1409.28  1302.2 1410.01
  1464.1 1416.48  1544.7 1429.02  1562.2 1428.99  1612.1 1452.55  1633.3 1454.86
  1667.9 1482.57  1705.7 1493.76  1739.5  1492.1  1769.8 1520.51  1920.1 1551.22
#Mann= 11 ,-1 , 0
       0      .1       0   498.6    .016       0   531.8     .04       0
   697.7    .045       0   964.9     .04       0  1544.7    .016       0
  1562.2      .1       0  1612.1    .016       0  1633.3      .1       0
  1705.7    .016       0  1739.5      .1       0
Bank Sta=697.7,964.9
XS Rating Curve= 0 ,0
Exp/Cntr(USF)=0,0
Exp/Cntr=0.3,0.1

Type RM Length L Ch R = 1 ,27973   ,856.9,850.3,821.7
BEGIN DESCRIPTION:
Channel burn based on effective XS AA
END DESCRIPTION:
Node Name=H
XS GIS Cut Line= 2
2023714.10865122 234331.641307982025568.27521847 235607.68304722
#Sta/Elev= 30
       0 1766.66    47.7 1711.22   287.3 1489.09   333.6 1453.53   404.9 1414.31
     450 1414.06   513.4 1410.79   549.6 1397.29     655 1399.96     673 1393.28
     677 1391.82   680.8  1382.3   931.9  1382.3   938.1 1393.54   955.8 1408.97
   963.8 1410.44  1358.1    1407  1827.5  1424.5  1891.2 1437.86  1919.5 1449.86
  1935.5  1449.8  1965.6 1475.32  1990.3 1489.39  2046.9 1490.49    2055 1499.73
  2065.7 1524.91    2071  1530.8  2108.2  1542.3  2138.9 1543.51  2250.8 1528.58
#Mann= 7 ,-1 , 0
       0      .1       0   404.9    .016       0     450     .08       0
     673    .045       0   938.1     .04       0  1990.3    .016       0
  2046.9      .1       0
#XS Ineff= 2 , 0
                            1550         1446.98
Permanent Ineff=
       F       F
#Block Obstruct= 1 ,-1
  458.68  487.53 1433.72
Bank Sta=673,938.1
XS Rating Curve= 0 ,0
Exp/Cntr=0.3,0.1

Type RM Length L Ch R = 1 ,27123   ,1124,1036.7,794.9
BEGIN DESCRIPTION:
Channel burn based on effective XS Z
END DESCRIPTION:
XS GIS Cut Line= 2
2023432.85855755235191.0162296442025328.69203623236378.516479313
#Sta/Elev= 30
       0  1553.7    41.5 1516.69   108.1 1466.22   153.3 1437.66   172.4 1436.21
   204.1 1414.24     235 1414.04   277.6 1398.26   284.3 1391.79   285.4  1381.7
     677  1381.7   680.2  1391.5   699.6 1404.56   804.1 1411.49  1010.3 1400.62
    1621 1417.61  1662.5 1423.29  1693.4 1434.76  1717.8 1435.48  1748.7  1455.1
  1836.2 1497.88  1849.4 1498.02  1868.7  1486.2  1907.7 1487.74  1914.8  1495.2
  1926.5 1519.02  1930.7 1521.44  2105.8 1537.24  2138.5 1535.05    2237 1547.45
#Mann= 6 ,-1 , 0
       0      .1       0   204.1    .016       0     235     .08       0
   284.3    .045       0   680.2     .04       0    1621      .1       0
#XS Ineff= 2 , 0
                         1363.38         1425.23
Permanent Ineff=
       F       F
#Block Obstruct= 2 ,-1
  732.87  800.77 1431.27 1955.13  2069.5 1554.28
Bank Sta=284.3,680.2
XS Rating Curve= 0 ,0
Exp/Cntr=0.3,0.1

Type RM Length L Ch R = 1 ,26086   ,918,994,1109.6
BEGIN DESCRIPTION:
Channel burn based on effective XS Y
END DESCRIPTION:
XS GIS Cut Line= 3
2023078.46261586236317.1020934282024465.67564228236552.017000093
2024749.19363309236620.871369288
#Sta/Elev= 30
       0 1510.45    15.8 1510.19    32.4 1499.32    75.6 1453.18      89 1429.86
     103 1413.57   135.5 1411.81   202.1 1402.19     242 1390.08   245.4  1381.3
   494.9  1381.3   495.7 1390.05   498.2  1390.3   528.2 1396.91   548.2  1394.8
   554.8  1390.7   635.2 1389.95   791.7 1396.42   805.9  1400.3   904.2 1401.28
  1027.3 1408.21  1303.5 1421.09  1320.1 1422.42  1343.4 1423.24  1366.7 1436.08
  1403.3  1445.7  1487.9  1457.1  1631.8 1466.66    1670 1483.74  1698.7 1486.27
#Mann= 10 ,-1 , 0
       0      .1       0     103    .016       0   135.5     .08       0
     242    .045       0   498.2     .08       0   554.8    .045       0
   635.2     .08       0  1027.3     .04       0  1303.5    .016       0
  1320.1      .1       0
#XS Ineff= 2 , 0
                            1055            1430
Permanent Ineff=
       F       F
Bank Sta=242,498.2
XS Rating Curve= 0 ,0
Exp/Cntr(USF)=0,0
Exp/Cntr=0.3,0.1

Type RM Length L Ch R = 1 ,25092   ,257.7,300.3,384.8
BEGIN DESCRIPTION:
Channel burn based on effective XS X
END DESCRIPTION:
XS GIS Cut Line= 2
2023099.52523471237185.8081718092024469.31711455237993.099536225
#Sta/Elev= 30
       0 1492.93    43.3 1456.36    58.3 1436.75    86.3 1410.12   123.1 1410.43
   142.1  1401.6   153.5 1401.15   177.3  1394.5   243.6 1389.74   261.2  1380.7
   527.2  1380.7   530.5  1387.7   591.5 1396.64   606.7 1402.34   728.6  1409.1
   865.7 1426.54     889 1426.69   903.7 1439.09   960.8  1441.8     980 1458.59
   998.9  1462.2  1021.8 1478.05  1039.9  1481.8  1078.9 1478.86  1101.8  1492.4
  1111.8 1493.97  1121.4 1500.58  1315.5 1560.49    1414 1596.16    1590 1652.54
#Mann= 9 ,-1 , 0
       0      .1       0    86.3    .016       0   123.1     .08       0
   243.6    .045       0   530.5     .08       0   606.7     .04       0
   865.7    .016       0     889     .04       0   960.8      .1       0
#Block Obstruct= 2 ,-1
  805.58  832.12 1442.59  924.79   960.8  1461.8
Bank Sta=243.6,530.5
XS Rating Curve= 0 ,0
Exp/Cntr=0.3,0.1

Type RM Length L Ch R = 1 ,24792   ,930.8,1035.3,1124.3
BEGIN DESCRIPTION:
Channel burn based on linear interpolation between effective XS W and X
END DESCRIPTION:
XS GIS Cut Line= 4
2022967.71413658237319.8987520322023484.88762954237861.368986281
2023604.63585443238172.0201783662023523.06822298238531.264853012
#Sta/Elev= 30
       0 1546.99    12.3 1533.82      31 1521.83   109.8 1458.58   153.5 1428.36
   170.1 1412.07   201.8 1412.29   225.8 1400.22     314 1387.81   316.8 1380.34
   492.7 1380.34   497.3 1387.48   643.5 1394.75   697.9 1404.49   760.5 1405.11
     850 1406.77     920 1411.79   931.5 1411.99     956 1415.19  1011.7 1457.24
  1042.2 1477.89    1075 1476.79    1119 1475.51  1142.6 1483.85  1163.2 1500.96
    1183  1532.1  1207.1 1547.51  1371.4 1632.03  1408.4 1646.99  1450.1 1656.57
#Mann= 10 ,-1 , 0
       0      .1       0   170.1    .016       0   201.8     .08       0
     314    .045       0   497.3     .08       0   760.5     .04       0
     920    .016       0   931.5     .08       0  1011.7    .016       0
    1075      .1       0
Bank Sta=314,497.3
XS Rating Curve= 0 ,0
Exp/Cntr(USF)=0,0
Exp/Cntr=0.3,0.1

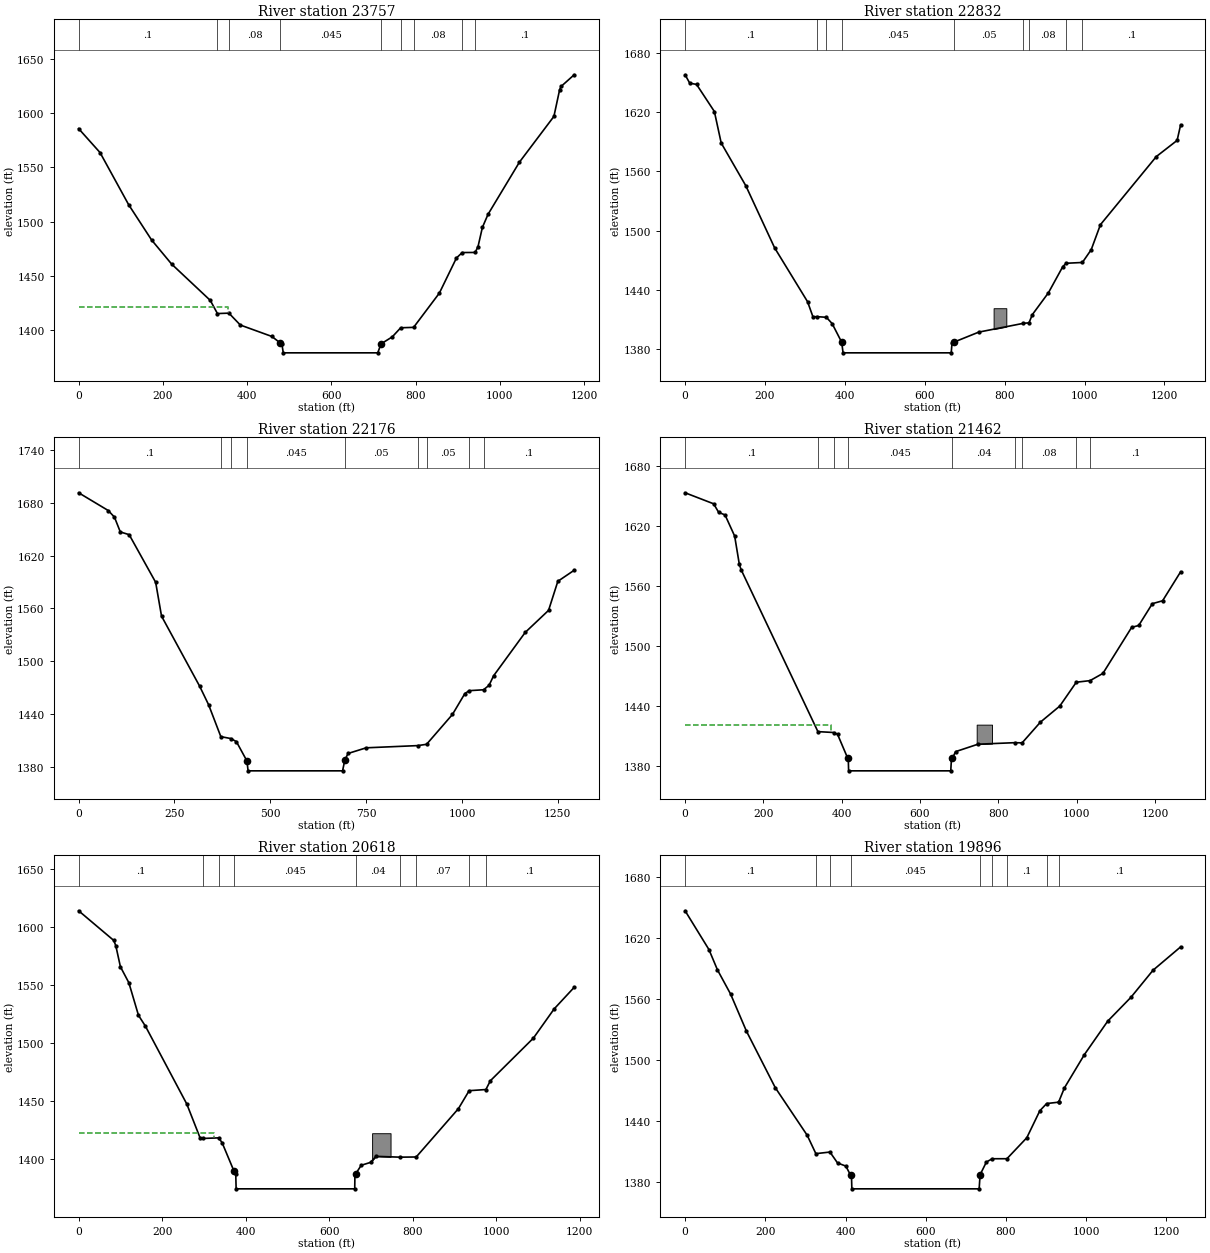
Type RM Length L Ch R = 1 ,23757   ,930.2,924.3,922.2
BEGIN DESCRIPTION:
Channel burn based on effective XS W
END DESCRIPTION:
Node Name=G
XS GIS Cut Line= 2
 2022292.2338703237618.0996300582022599.52525046238753.516322479
#Sta/Elev= 30
       0 1585.72    50.8 1563.68   118.7 1515.65   173.1 1483.17   220.7 1460.92
   312.5 1427.43   329.5 1415.29   356.7 1415.69   383.8 1404.73   458.6 1394.21
     479 1388.09   482.4 1387.41   485.8  1379.1   710.1  1379.1   717.7 1387.35
   744.5 1393.82   764.5  1402.2   795.1 1402.57   856.3 1434.16   896.9 1466.57
   910.7 1471.53   941.3 1471.62   948.1 1477.09   958.4 1494.65   971.8 1506.75
  1046.4 1554.87  1128.2    1597  1141.8 1621.63  1145.2  1624.6  1176.3 1635.37
#Mann= 9 ,-1 , 0
       0      .1       0   329.5    .016       0   356.7     .08       0
     479    .045       0   717.7     .04       0   764.5    .016       0
   795.1     .08       0   910.7    .016       0   941.3      .1       0
#XS Ineff= 2 , 0
          354.25 1421.61
Permanent Ineff=
       F       F
Bank Sta=479,717.7
XS Rating Curve= 0 ,0
Exp/Cntr=0.3,0.1

Type RM Length L Ch R = 1 ,22832   ,711.2,655.8,597.3
BEGIN DESCRIPTION:
Channel burn based on effective XS V
END DESCRIPTION:
XS GIS Cut Line= 2
2021391.19203722237888.9330778872021750.56697464239076.432999477
#Sta/Elev= 30
       0 1657.81    11.6 1649.34    28.7 1648.06    73.3 1620.66    90.4  1588.8
   152.1 1545.52   224.1 1482.81   306.6 1428.32   320.1 1413.06   330.4  1413.2
   353.7 1412.54   368.1 1406.21   392.1 1387.31   395.5  1376.6   666.3  1376.6
   668.4 1387.01   673.2 1387.44   735.2 1397.55   847.2 1406.47     861 1406.92
   869.4 1415.26   909.7 1437.35   945.7 1463.85   954.2 1467.19   994.7 1467.99
  1016.8 1480.91  1039.9 1506.23  1179.9 1575.13  1231.9 1591.44  1240.7 1607.24
#Mann= 9 ,-1 , 0
       0      .1       0   330.4    .016       0   353.7     .08       0
   392.1    .045       0   673.2     .05       0   847.2    .016       0
     861     .08       0   954.2    .016       0   994.7      .1       0
#Block Obstruct= 1 ,-1
  772.41  804.24 1421.73
Bank Sta=392.1,673.2
XS Rating Curve= 0 ,0
Exp/Cntr=0.3,0.1

Type RM Length L Ch R = 1 ,22176   ,731.2,714.8,691.3
BEGIN DESCRIPTION:
Channel burn based on linear interpolation between effective XS U and V
END DESCRIPTION:
XS GIS Cut Line= 2
2020646.40021972 238191.016463222021318.27551639239295.182890058
#Sta/Elev= 30
       0 1691.18    77.2 1671.06    93.4 1663.56   108.7 1646.76   131.8 1643.68
   200.9 1589.65   216.2 1551.29   315.8 1471.65   339.1 1450.65   370.9 1414.57
   396.8 1412.43   411.5 1408.93     439 1386.95     4421375.786   688.41375.786
   694.4 1388.21   702.8  1395.5   750.1 1401.91   884.5 1404.41   907.5 1405.88
     975 1439.73  1007.4 1463.45  1018.9 1466.72  1056.1 1467.74  1070.5 1472.81
  1082.4 1483.63  1164.8 1532.79  1225.7 1557.81  1249.9 1590.77  1292.5  1603.3
#Mann= 9 ,-1 , 0
       0      .1       0   370.9    .016       0   396.8     .08       0
     439    .045       0   694.4     .05       0   884.5    .016       0
   907.5     .05       0  1018.9    .016       0  1056.1      .1       0
Bank Sta=439,694.4
XS Rating Curve= 0 ,0
Exp/Cntr=0.3,0.1

Type RM Length L Ch R = 1 ,21462   ,817.1,843.1,868.7
BEGIN DESCRIPTION:
Channel burn based on effective XS U
END DESCRIPTION:
XS GIS Cut Line= 2
2020016.19216256238628.5162443972020771.40029781239644.141509727
#Sta/Elev= 30
       0 1652.76    72.9 1641.74    85.7 1633.21     102 1630.62   126.6 1609.47
   138.5 1581.28   142.9 1576.03   339.2 1414.09     380 1413.19   389.4 1411.36
   415.2 1387.61   416.8 1386.88   417.6  1374.9   678.5  1374.9   680.2 1386.75
   682.5 1387.34   690.8 1394.09     748 1401.52     842 1403.04   860.7 1402.85
   907.6 1423.61   956.9 1439.61   999.1 1463.46  1034.2 1465.04  1067.1 1472.27
  1140.5 1518.29  1158.5 1520.14  1193.3 1541.94  1219.5 1544.84  1265.6 1573.81
#Mann= 9 ,-1 , 0
       0      .1       0   339.2    .016       0     380     .08       0
   415.2    .045       0   682.5     .04       0     842    .016       0
   860.7     .08       0   999.1    .016       0  1034.2      .1       0
#XS Ineff= 2 , 0
          371.49 1420.79
Permanent Ineff=
       F       F
#Block Obstruct= 1 ,-1
   744.7   783.9 1421.07
Bank Sta=415.2,682.5
XS Rating Curve= 0 ,0
Exp/Cntr=0.3,0.1

Type RM Length L Ch R = 1 ,20618   ,710.3,722.6,740.8
BEGIN DESCRIPTION:
Channel burn based on linear interpolation between effective XS T and U
END DESCRIPTION:
Node Name=F
XS GIS Cut Line= 3
2019422.44203772239118.0995828062019818.27523555 239836.84978573
2019958.90028238240175.391431481
#Sta/Elev= 30
       0 1613.68    84.1 1588.13      89 1583.65   100.1 1565.41   120.3 1551.67
   143.4 1523.52   160.1 1514.16   259.1 1447.11   291.1 1417.79   298.6 1417.43
   335.3 1417.92   343.6 1413.85   372.2 1389.23   376.4 1386.61   377.3 1373.98
   661.4 1373.98   661.9  1386.4   663.8 1386.92   676.9 1394.27   699.4  1396.8
   712.1 1401.99   770.1 1401.28   808.7 1401.44   909.8  1443.1   935.5 1458.59
   975.6 1459.59   986.4 1467.18  1089.4  1503.9  1139.1 1529.07  1187.1 1547.67
#Mann= 9 ,-1 , 0
       0      .1       0   298.6    .016       0   335.3     .08       0
   372.2    .045       0   663.8     .04       0   770.1    .016       0
   808.7     .07       0   935.5    .016       0   975.6      .1       0
#XS Ineff= 2 , 0
          324.51 1421.98
Permanent Ineff=
       F       F
#Block Obstruct= 1 ,-1
  703.03  747.22 1421.93
Bank Sta=372.2,663.8
XS Rating Curve= 0 ,0
Exp/Cntr=0.3,0.1

Type RM Length L Ch R = 1 ,19896   ,637.4,724.1,779.1
BEGIN DESCRIPTION:
Channel burn based on effective XS T
END DESCRIPTION:
XS GIS Cut Line= 2
2018818.27526705239430.5996139792019328.69189714 240555.59966056
#Sta/Elev= 30
       0 1646.98    59.4 1608.82    80.7 1588.77   113.4    1565     153  1528.4
   224.8 1472.81   304.4 1425.94     326 1407.84   361.1 1409.43     380  1398.7
   400.8 1395.58   412.4 1386.73   414.8 1386.23   415.7  1373.2   733.1  1373.2
   735.4 1387.04   751.1 1399.58   765.5 1402.83   802.3 1402.85   851.9 1423.52
   884.4  1450.1   901.4 1457.18   931.2 1458.53   931.2 1458.57   945.6 1472.55
   995.6 1505.45  1053.7 1538.36  1111.4 1561.74  1166.6 1588.45  1235.4 1611.43
#Mann= 9 ,-1 , 0
       0      .1       0     326    .016       0   361.1     .08       0
   412.4    .045       0   735.4     .08       0   765.5    .016       0
   802.3      .1       0   901.4    .016       0   931.2      .1       0
Bank Sta=412.4,735.4
XS Rating Curve= 0 ,0
Exp/Cntr=0.3,0.1

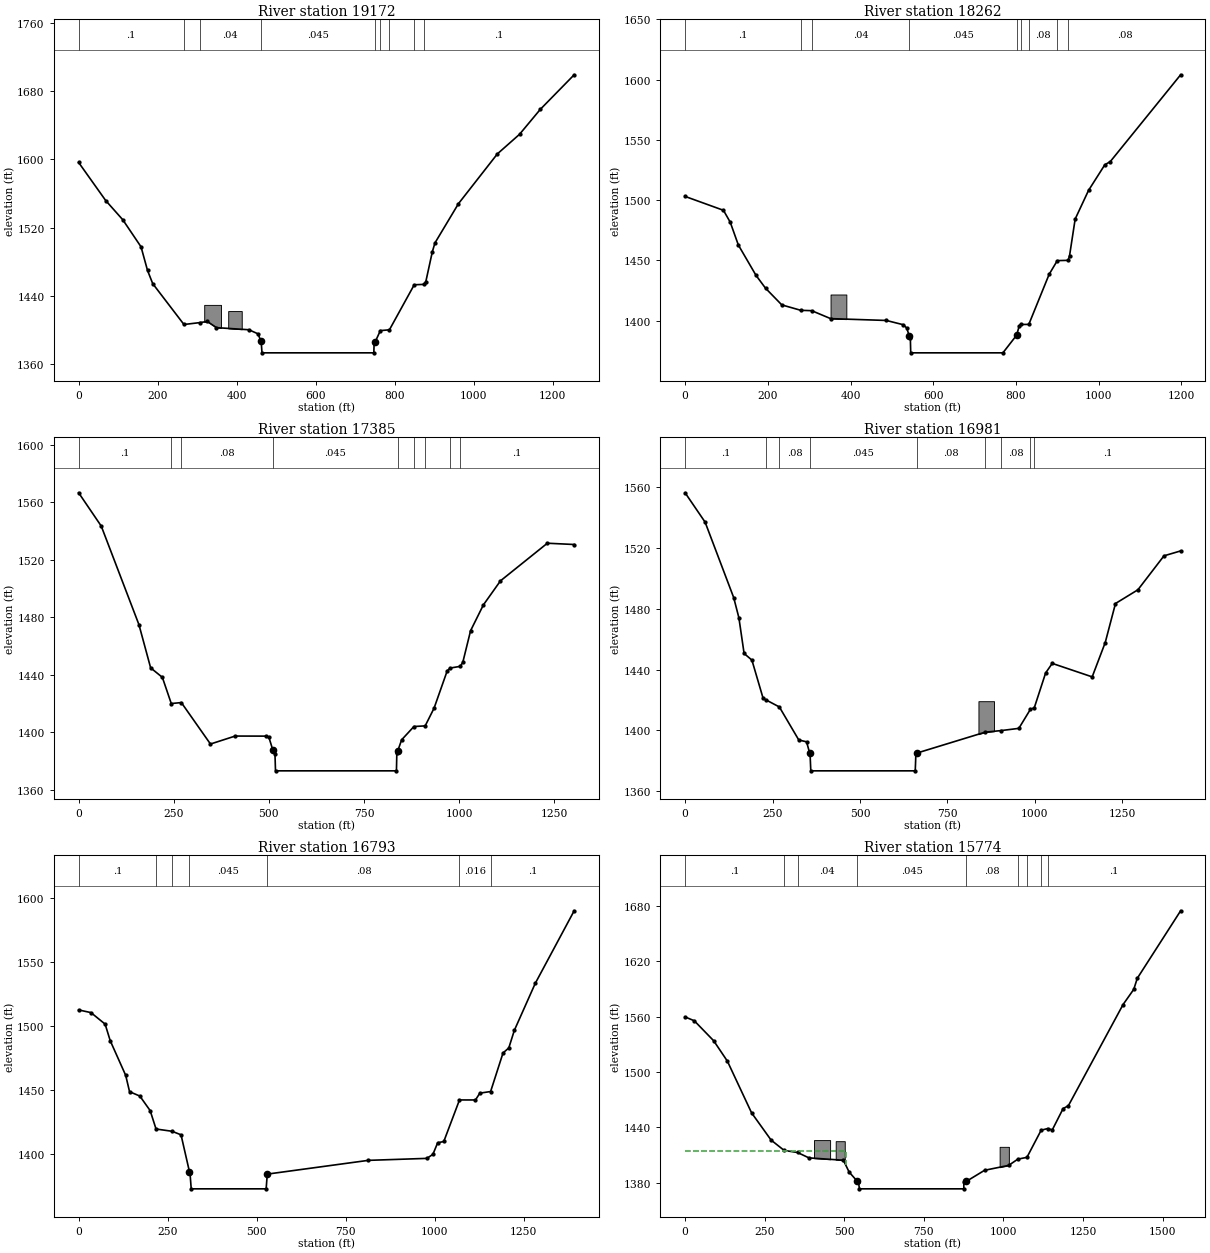
Type RM Length L Ch R = 1 ,19172   ,890.2,909.3,918.2
BEGIN DESCRIPTION:
Channel burn based on linear interpolation between effective XS S and T
END DESCRIPTION:
XS GIS Cut Line= 2
 2018318.2752828239550.3913691492018427.65039213240800.391493812
#Sta/Elev= 30
       0 1596.43    68.5 1551.81   111.9 1529.19     158 1497.52   174.4 1469.88
   187.6 1454.35   266.7 1406.43   306.2 1408.61   325.9 1409.97     349 1402.75
   431.3 1400.26   454.4 1395.43     461 1387.45   462.2 1386.82   464.3  1373.2
   747.5  1373.2   748.3 1385.82   750.8 1385.88     764 1399.24     787 1400.22
   849.8 1453.01     874 1453.47   879.2 1456.79   895.7 1491.85   902.3 1502.09
   961.8 1548.11  1060.4 1606.51  1116.4 1629.41    1169 1658.67  1254.8 1699.24
#Mann= 9 ,-1 , 0
       0      .1       0   266.7    .016       0   306.2     .04       0
     461    .045       0   750.8     .08       0     764    .016       0
     787     .08       0   849.8    .016       0     874      .1       0
#Block Obstruct= 2 ,-1
  317.98  360.44 1429.43  378.74  413.01 1422.18
Bank Sta=461,750.8
XS Rating Curve= 0 ,0
Exp/Cntr=0.3,0.1

Type RM Length L Ch R = 1 ,18262   ,785.8,877.9,934.4
BEGIN DESCRIPTION:
Channel burn based on effective XS S
END DESCRIPTION:
XS GIS Cut Line= 2
2017453.69203822239503.5164628922017474.52532989240701.433030307
#Sta/Elev= 30
       0 1502.99    92.7 1491.48   109.1 1481.63   128.8 1462.63   171.5 1437.47
   194.4 1426.85   233.8 1412.98   279.8 1408.48     306 1408.19   351.9 1401.59
   486.5 1400.07   527.9  1396.5   535.7 1393.81   542.3 1387.01   544.6 1385.74
   545.5  1373.2   768.4  1373.2   801.5 1387.82     808 1395.67   811.3 1396.72
     831  1396.8   880.2 1438.38   899.9 1449.72   926.2 1449.95   929.5 1453.74
   943.1 1484.23   975.4 1507.97  1014.8 1529.26  1027.9 1531.85  1198.1 1603.93
#Mann= 9 ,-1 , 0
       0      .1       0   279.8    .016       0     306     .04       0
   542.3    .045       0   801.5     .08       0   811.3    .016       0
     831     .08       0   899.9    .016       0   926.2     .08       0
#Block Obstruct= 1 ,-1
  351.66  389.84 1421.61
Bank Sta=542.3,801.5
XS Rating Curve= 0 ,0
Exp/Cntr=0.3,0.1

Type RM Length L Ch R = 1 ,17385   ,368.2,403.4,388
BEGIN DESCRIPTION:
Channel burn based on linear interpolation between effective XS R and S
END DESCRIPTION:
Node Name=E
XS GIS Cut Line= 2
2016787.02539255239467.0578743962016422.44213222 240717.05799906
#Sta/Elev= 30
       0 1566.63    59.4 1543.48   158.5 1474.87   189.2 1444.85     220 1438.23
   243.4 1420.02   269.9 1420.69   346.4 1391.85   411.4  1397.4   493.4 1397.35
   500.1  1396.4   510.6 1387.36   515.9 1384.94   517.3  1373.2   835.1  1373.2
   836.1 1385.48   838.2 1386.83   848.8  1394.8   881.1 1404.04   910.6 1404.47
     934 1416.82   968.4 1442.69   976.3  1444.7  1002.6 1445.88  1009.4 1448.63
  1029.9 1470.68  1063.6 1488.66  1108.5 1505.38  1231.6 1531.54  1302.1 1530.65
#Mann= 9 ,-1 , 0
       0      .1       0   243.4    .045       0   269.9     .08       0
   510.6    .045       0   838.2     .08       0   881.1    .016       0
   910.6     .08       0   976.3    .016       0  1002.6      .1       0
Bank Sta=510.6,838.2
XS Rating Curve= 0 ,0
Exp/Cntr=0.3,0.1

Type RM Length L Ch R = 1 ,16981   ,181.2,188.1,234.9
BEGIN DESCRIPTION:
Channel burn based on linear interpolation between effective XS R and S
END DESCRIPTION:
XS GIS Cut Line= 4
2016463.67075408239425.9598800832016187.91958843240038.740248183
 2016137.5840582240384.5234558962016384.88470675240693.102141261
#Sta/Elev= 30
       0  1556.5    57.2 1537.15   138.9 1487.44   153.8 1474.11   168.7 1450.57
     191  1446.2   223.2  1420.9   232.4 1419.83   269.5 1415.31     325 1393.55
   347.3 1392.33   355.8 1385.24   357.2 1384.85   359.4  1373.2     658  1373.2
   659.9 1384.71   662.91384.931   857.6 1398.67   904.4 1399.76   954.2  1401.2
   987.3 1413.76   998.3 1414.73  1030.8 1437.72  1049.7 1444.03  1163.9 1435.14
  1201.2 1457.77  1230.5  1483.5  1294.6 1492.55  1369.2 1514.94  1416.8 1518.17
#Mann= 9 ,-1 , 0
       0      .1       0   232.4    .016       0   269.5     .08       0
   355.8    .045       0   662.9     .08       0   857.6    .016       0
   904.4     .08       0   987.3    .016       0   998.3      .1       0
#Block Obstruct= 1 ,-1
  838.71  883.21 1419.11
Bank Sta=355.8,662.9
XS Rating Curve= 0 ,0
Exp/Cntr(USF)=0,0
Exp/Cntr=0.3,0.1

Type RM Length L Ch R = 1 ,16793   ,982.5,1018.9,972.3
BEGIN DESCRIPTION:
Channel burn based on effective XS R
END DESCRIPTION:
XS GIS Cut Line= 5
2016290.77915022239377.8128511612016008.46248063239988.404717946
 2015942.8074412240137.2228073422015872.77539913240404.219967728
2015684.56428607240612.127592619
#Sta/Elev= 30
       0 1512.68    34.6 1510.59    74.4 1501.61    88.8 1488.63   132.2 1461.67
     143 1448.95   171.9 1445.52   200.9 1434.19   217.4 1419.84   262.3 1418.08
   287.6 1415.31   311.3  1386.5   312.9 1385.32   316.2  1373.2   526.7  1373.2
   529.8 1384.68   813.5  1395.4   978.2 1396.95   995.1 1400.12  1008.4 1409.11
  1025.6 1410.11  1069.7  1442.5  1114.6 1442.49  1126.9 1447.81  1157.1 1449.06
    1192 1479.14  1208.2 1483.04  1223.7 1496.72  1282.6 1533.44  1391.8 1589.97
#Mann= 7 ,-1 , 0
       0      .1       0   217.4    .016       0   262.3     .08       0
   311.3    .045       0   529.8     .08       0  1069.7    .016       0
  1157.1      .1       0
Bank Sta=311.3,529.8
XS Rating Curve= 0 ,0
Exp/Cntr(USF)=0,0
Exp/Cntr=0.3,0.1

Type RM Length L Ch R = 1 ,15774   ,828.1,865.6,891.9
BEGIN DESCRIPTION:
Channel burn based on linear interpolation between effective XS Q and R
END DESCRIPTION:
XS GIS Cut Line= 2
2015422.44216372238956.6412443072014776.60880972240373.308030397
#Sta/Elev= 30
       0 1559.54    28.9 1555.38    89.9 1533.67   132.9 1511.57   208.9 1455.56
   270.2 1426.05   311.2 1414.86   353.2  1412.6   389.2 1406.75   497.4  1404.2
   515.4 1391.35   540.7 1381.54   544.3 1380.88   547.9  1373.2   875.6  1373.2
   875.9 1380.66   883.5 1381.28   940.9  1393.3  1016.6 1398.63  1045.4 1405.39
    1074 1407.33  1118.6 1436.72  1139.2 1438.58  1153.6 1437.07  1187.7 1460.24
  1204.1 1463.24  1376.1 1573.01  1409.6 1589.42  1420.7 1601.42  1556.9 1674.61
#Mann= 9 ,-1 , 0
       0      .1       0   311.2    .016       0   353.2     .04       0
   540.7    .045       0   883.5     .08       0  1045.4    .016       0
    1074     .08       0  1118.6    .016       0  1139.2      .1       0
#XS Ineff= 2 , 0
          504.79 1413.76
Permanent Ineff=
       F       F
#Block Obstruct= 3 ,-1
  404.92  455.59 1426.03  473.15  501.61 1424.86   988.2 1017.19 1418.73
Bank Sta=540.7,883.5
XS Rating Curve= 0 ,0
Exp/Cntr=0.3,0.1

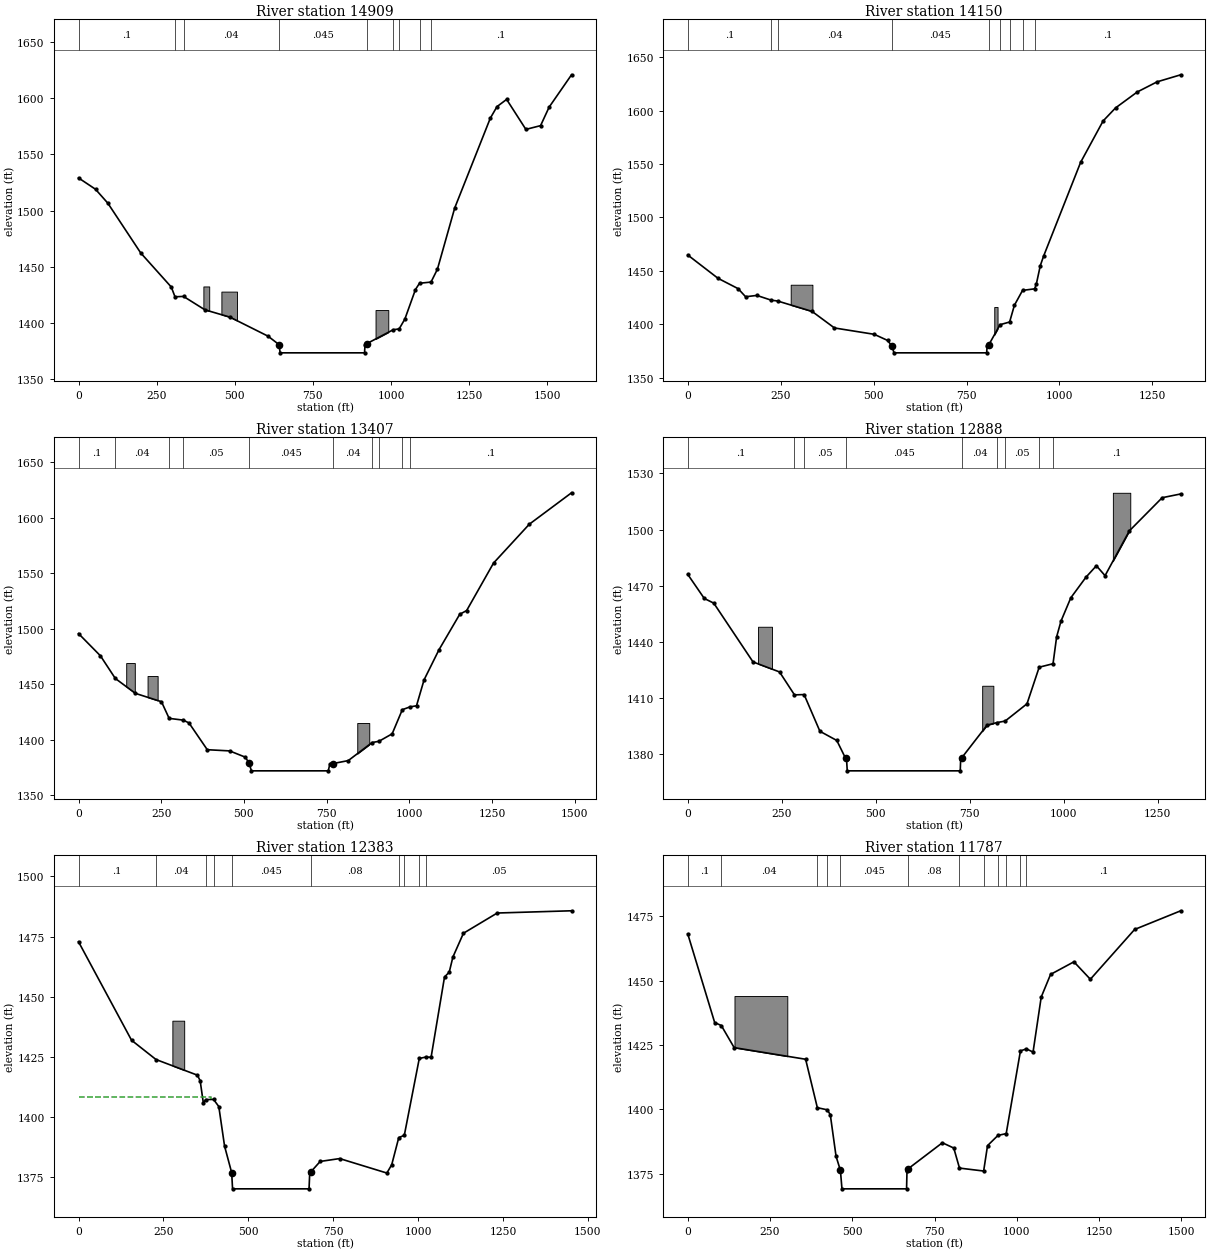
Type RM Length L Ch R = 1 ,14909   ,713.9,758.3,788.6
BEGIN DESCRIPTION:
Channel burn based on effective XS Q
END DESCRIPTION:
XS GIS Cut Line= 2
2014766.19216388238602.4746298042013906.81691414239925.391275316
#Sta/Elev= 30
       0 1529.09    54.4 1518.98    93.9 1506.55   199.1 1462.21   296.9 1431.83
   308.7 1423.15     336 1423.48   404.5 1411.53   484.7 1405.01   606.4 1388.06
   641.7 1380.51   645.1  1373.2   915.1  1373.2   916.8    1380   921.6 1381.27
  1006.9 1393.78  1025.9 1394.52  1044.2 1403.28  1078.1 1429.61  1091.1 1435.22
  1127.9 1436.26  1148.4 1447.74  1203.8 1502.38  1317.6 1582.32    1339 1592.63
  1369.8 1599.06  1431.4 1572.33  1478.4 1575.67  1505.8 1592.18  1577.5    1621
#Mann= 9 ,-1 , 0
       0      .1       0   308.7    .016       0     336     .04       0
   641.7    .045       0   921.6     .08       0  1006.9    .016       0
  1025.9     .08       0  1091.1    .016       0  1127.9      .1       0
#Block Obstruct= 3 ,-1
  399.54   418.2 1432.36  457.17  507.13 1427.78   950.4  991.16 1411.33
Bank Sta=641.7,921.6
XS Rating Curve= 0 ,0
Exp/Cntr=0.3,0.1

Type RM Length L Ch R = 1 ,14150   ,718.6,743.5,757.4
BEGIN DESCRIPTION:
Channel burn based on effective XS P
END DESCRIPTION:
XS GIS Cut Line= 2
2014193.27533072238326.4328590632013281.81717989239289.974567145
#Sta/Elev= 30
       0 1464.79    81.4 1442.97   135.6 1433.26   155.7 1425.69   185.9 1426.94
   224.7 1422.48   241.6 1421.72   334.5 1411.96   394.7 1396.48   501.6 1390.55
   537.6 1384.81   549.3 1379.43   554.9  1373.2     804  1373.2   805.5 1379.16
   810.2 1380.88   840.1 1399.54   865.9 1402.05   878.7 1417.69   900.7 1431.64
   933.2  1433.1   937.8 1437.58   948.5 1454.92   957.6 1463.97  1056.9 1551.48
  1117.4 1590.22  1150.8 1602.41  1209.3 1617.35  1262.7 1626.84  1326.3 1633.44
#Mann= 9 ,-1 , 0
       0      .1       0   224.7    .016       0   241.6     .04       0
   549.3    .045       0   810.2     .08       0   840.1    .016       0
   865.9     .08       0   900.7    .016       0   933.2      .1       0
#Block Obstruct= 2 ,-1
     277  335.41 1436.95  824.58  833.44 1416.09
Bank Sta=549.3,810.2
XS Rating Curve= 0 ,0
Exp/Cntr=0.3,0.1

Type RM Length L Ch R = 1 ,13407   ,528.9,518.6,505.5
BEGIN DESCRIPTION:
Channel burn based on linear interpolation between effective XS O and P
END DESCRIPTION:
Node Name=D
XS GIS Cut Line= 2
2013750.56689855237805.5995831492012635.98382589238795.182905808
#Sta/Elev= 30
       0 1495.72    66.3 1475.64   111.3 1455.21   171.7 1441.81   250.8 1434.25
     274 1419.22   316.4 1417.66     334 1415.11   389.3 1390.96   456.8 1389.89
   504.1 1384.26   515.7 1378.94   522.71371.905   755.11371.905   759.7 1377.91
  769.261378.469   815.5 1381.14   887.5 1397.44   908.2 1398.54   948.2 1405.29
   978.9 1427.05  1001.4 1429.52  1021.8 1430.59  1044.7 1453.99  1089.7 1481.06
  1152.5 1513.11  1173.4 1516.47  1254.7 1559.31  1362.8 1594.33  1490.5 1622.69
#Mann= 10 ,-1 , 0
       0      .1       0   111.3     .04       0     274    .016       0
   316.4     .05       0   515.7    .045       0  769.26     .04       0
   887.5    .016       0   908.2     .05       0   978.9    .016       0
  1001.4      .1       0
#Block Obstruct= 3 ,-1
   144.2  170.21 1469.13  208.77  239.21 1457.44  842.67  878.97 1415.05
Bank Sta=515.7,769.26
XS Rating Curve= 0 ,0
Exp/Cntr=0.3,0.1

Type RM Length L Ch R = 1 ,12888   ,501,505.5,510.9
BEGIN DESCRIPTION:
Channel burn based on effective XS O
END DESCRIPTION:
XS GIS Cut Line= 2
2013328.69208613237446.2246457342012396.40031555238368.099770471
#Sta/Elev= 30
       0 1476.05      44 1463.17    69.3 1460.65   173.6 1429.23   244.1 1423.88
   283.9 1411.61   309.5 1411.78   351.5 1392.15   396.4 1387.24   419.6 1377.76
   422.3 1377.36   424.2    1371   724.7    1371   725.8 1377.33   728.1 1377.82
     796 1395.44   823.2 1396.83   844.1 1397.61   902.2 1406.85   934.6 1426.41
   971.4 1428.27     981 1442.65   992.6 1451.05  1018.7 1463.51    1059 1474.53
  1086.7 1480.65  1109.8 1475.36  1174.4 1499.31  1261.7 1517.04  1311.1 1519.05
#Mann= 9 ,-1 , 0
       0      .1       0   283.9    .016       0   309.5     .05       0
   419.6    .045       0   728.1     .04       0   823.2    .016       0
   844.1     .05       0   934.6    .016       0   971.4      .1       0
#Block Obstruct= 3 ,-1
  187.02  224.03 1448.04     783   812.7 1416.49 1130.57 1176.82 1519.67
Bank Sta=419.6,728.1
XS Rating Curve= 0 ,0
Exp/Cntr=0.3,0.1

Type RM Length L Ch R = 1 ,12383   ,621.1,595.5,525.6
BEGIN DESCRIPTION:
Channel burn based on linear interpolation between effective XS N and O
END DESCRIPTION:
XS GIS Cut Line= 2
2013010.98373206237071.2247395662011953.69188339238066.016385138
#Sta/Elev= 30
       0 1472.85   156.2 1431.92   228.2 1423.91     350 1417.41   358.2 1415.11
   367.4 1405.99   374.4 1407.24   397.6 1407.34   413.1 1404.37   430.1  1387.9
     451 1376.89   453.61370.174   678.81370.174   680.8 1376.79   683.3  1377.1
   711.6 1381.56     769 1382.75   907.9 1376.74   922.2 1380.18     943 1391.48
   959.3 1392.41  1003.4 1424.35    1022 1424.92  1038.2 1424.87  1077.7 1458.22
  1091.6 1460.22  1102.3 1466.47  1133.4 1476.38  1232.9 1484.79  1451.7 1485.72
#Mann= 10 ,-1 , 0
       0      .1       0   228.2     .04       0   374.4    .016       0
   397.6     .08       0     451    .045       0   683.3     .08       0
     943    .016       0   959.3     .08       0  1003.4    .016       0
    1022     .05       0
#XS Ineff= 2 , 0
          389.41 1408.37
Permanent Ineff=
       F       F
#Block Obstruct= 1 ,-1
  276.39   311.2 1440.05
Bank Sta=451,683.3
XS Rating Curve= 0 ,0
Exp/Cntr=0.3,0.1

Type RM Length L Ch R = 1 ,11787   ,815.5,739.9,571.5
BEGIN DESCRIPTION:
Channel burn based on effective XS N
END DESCRIPTION:
XS GIS Cut Line= 2
2012458.90051864236618.0996615592011625.56688347 237862.89146331
#Sta/Elev= 30
       0 1468.13    81.9  1433.7     102 1432.56   141.1 1423.98   358.2 1419.47
   393.8 1400.68   423.7 1399.86   433.1 1398.01   450.7  1381.8   463.9 1376.37
   468.6  1369.2   664.9  1369.2   666.2  1376.2  669.371376.947   773.7 1387.08
   808.3 1385.02   825.7 1377.25   899.1 1376.11   910.9 1385.96   942.6 1389.93
   967.6 1390.62  1010.9 1422.73  1029.1 1423.49  1049.2 1422.26    1074 1443.59
  1102.4 1452.38  1173.4 1457.27  1223.3  1450.5  1357.8 1469.82    1498 1477.07
#Mann= 12 ,-1 , 0
       0      .1       0     102     .04       0   393.8    .016       0
   423.7     .08       0   463.9    .045       0  669.37     .08       0
   825.7    .045       0   899.1     .08       0   942.6    .016       0
   967.6     .08       0  1010.9    .016       0  1029.1      .1       0
#Block Obstruct= 1 ,-1
  142.05  302.51    1444
Bank Sta=463.9,669.37
XS Rating Curve= 0 ,0
Exp/Cntr=0.3,0.1

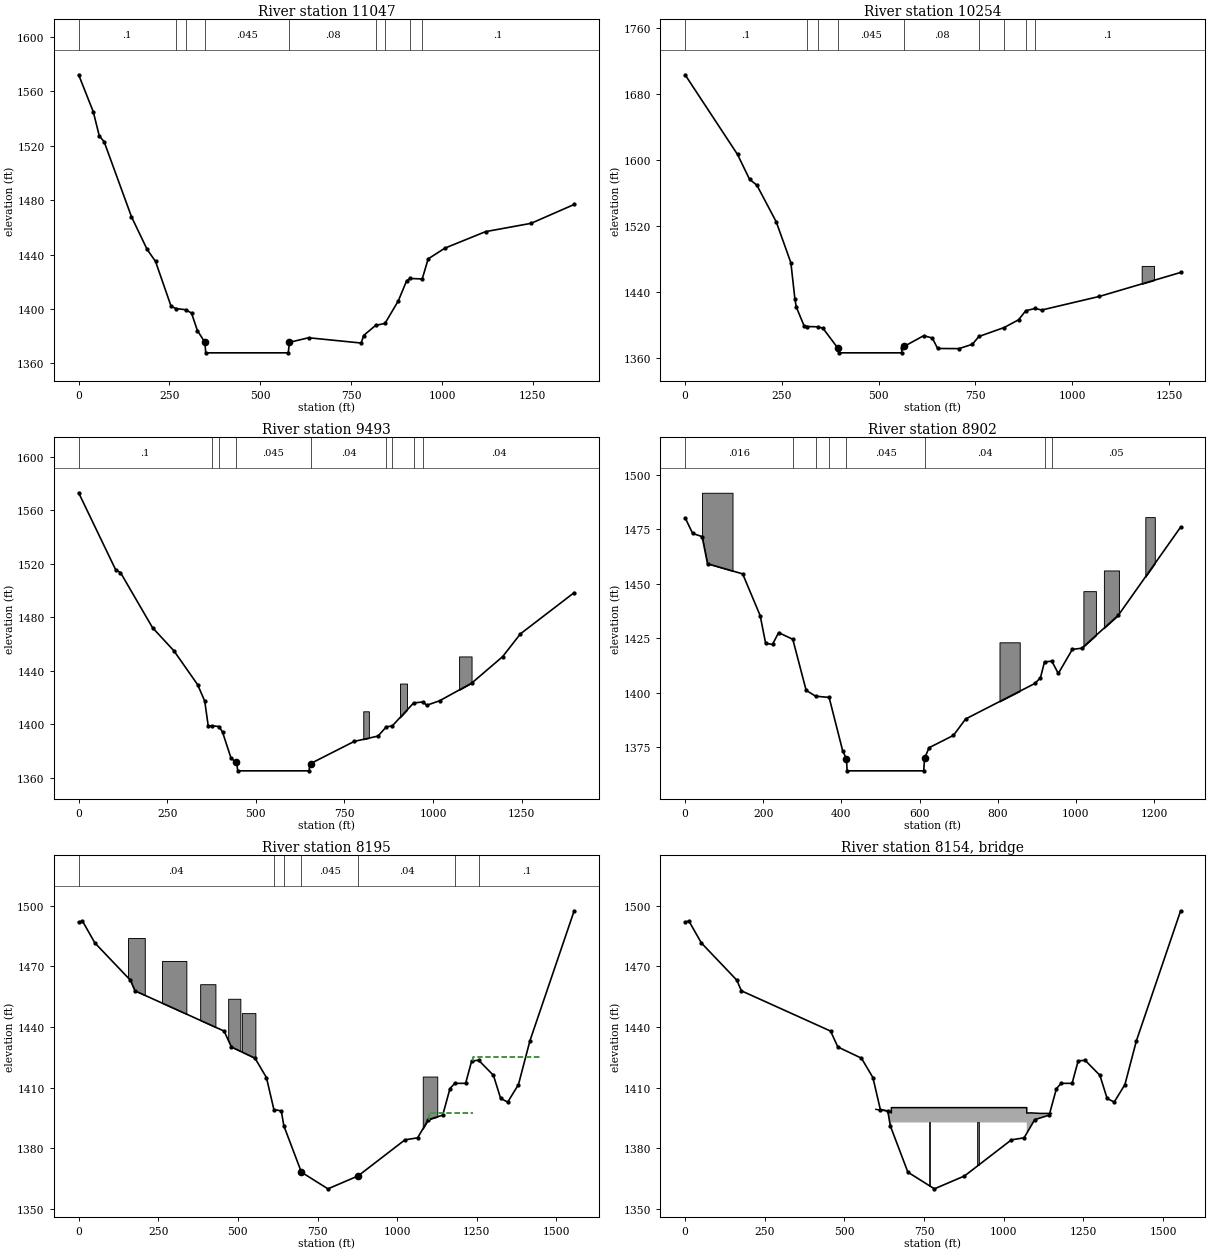
Type RM Length L Ch R = 1 ,11047   ,848.2,793.3,684.8
BEGIN DESCRIPTION:
Channel burn based on linear interpolation between effective XS M and N
END DESCRIPTION:
XS GIS Cut Line= 2
2011510.98377931 236347.266213732011401.60866997237706.641447723
#Sta/Elev= 30
       0 1572.11    40.4 1544.86    56.9 1527.09    70.1 1522.99   145.5 1467.76
   188.5 1443.79   211.6 1434.98   254.4 1402.04   267.5 1400.35   294.8 1399.47
   310.7    1397   326.8  1384.2  347.441375.569   349.8  1367.8   576.9  1367.8
   580.2 1375.53   632.9 1378.88   777.7    1375   784.3 1380.54   817.2 1387.95
   843.1 1389.43   879.7 1405.92   902.8 1420.84   912.7 1422.46   945.6 1422.06
     962 1436.85  1008.1 1444.74    1120 1456.86  1245.3 1462.97  1363.8 1476.82
#Mann= 9 ,-1 , 0
       0      .1       0   267.5    .016       0   294.8     .08       0
  347.44    .045       0   580.2     .08       0   817.2    .016       0
   843.1     .08       0   912.7    .016       0   945.6      .1       0
Bank Sta=347.44,580.2
XS Rating Curve= 0 ,0
Exp/Cntr=0.3,0.1

Type RM Length L Ch R = 1 ,10254   ,744.8,760.5,787.6
BEGIN DESCRIPTION:
Channel burn based on effective XS M
END DESCRIPTION:
Node Name=C
XS GIS Cut Line= 2
 2010542.2337483236435.8080313952010932.85862322237654.557890475
#Sta/Elev= 30
       0 1703.15   135.4 1606.62   166.4 1576.59   185.4 1569.37   235.3  1525.1
   273.2 1475.44   283.5 1431.88   287.2 1421.74   307.6 1398.66   315.9 1398.17
     342 1397.85   355.9 1396.16   394.2 1372.24   396.8  1366.3   559.1  1366.3
   560.3  1371.8   566.4 1374.28   616.1 1387.04   638.4 1384.29   652.2 1371.56
   707.3 1371.41   741.7 1376.63     759 1386.14     824 1396.96   861.2 1406.33
   879.8 1417.33   903.7 1420.04   921.2 1418.18  1069.9 1434.64  1279.8 1463.68
#Mann= 9 ,-1 , 0
       0      .1       0   315.9    .016       0     342     .08       0
   394.2    .045       0   566.4     .08       0     759    .016       0
     824     .08       0   879.8    .016       0   903.7      .1       0
#Block Obstruct= 1 ,-1
  1179.2 1211.08 1471.59
Bank Sta=394.2,566.4
XS Rating Curve= 0 ,0
Exp/Cntr=0.3,0.1

Type RM Length L Ch R = 1 ,9493    ,607.7,591.8,564.1
BEGIN DESCRIPTION:
Channel burn based on linear interpolation between effective XS L and M
END DESCRIPTION:
XS GIS Cut Line= 2
2009854.73381098236586.8497240542010135.98357655237956.641275808
#Sta/Elev= 30
       0 1572.94   104.7 1515.26   118.1  1513.3   208.5 1472.08   268.8 1454.81
   335.8 1429.48   355.9 1417.14   365.9 1398.22     376 1398.76   396.1 1398.16
   406.1 1393.98   429.6 1374.94     443 1371.38   446.2  1370.7     449 1365.04
   650.6 1365.04   651.9 1370.25   654.61370.476   777.9 1387.06   844.9 1391.03
   868.3 1397.96   884.8 1398.58   945.4  1415.8   971.4 1416.53   982.2 1414.05
    1019 1417.48  1109.5 1430.69  1196.6 1450.44  1246.5 1467.41  1398.4 1498.28
#Mann= 9 ,-1 , 0
       0      .1       0     376    .016       0   396.1     .08       0
     443    .045       0   654.6     .04       0   868.3    .016       0
   884.8     .04       0   945.4    .016       0   971.4     .04       0
#Block Obstruct= 3 ,-1
  803.18  819.02 1409.56  906.94  926.57  1430.3 1073.67 1108.84 1450.58
Bank Sta=443,654.6
XS Rating Curve= 0 ,0
Exp/Cntr=0.3,0.1

Type RM Length L Ch R = 1 ,8902    ,741,706.4,670.6
BEGIN DESCRIPTION:
Channel burn based on effective XS L
END DESCRIPTION:
XS GIS Cut Line= 2
2009240.15039447 236805.599614652009641.19191521238008.724833056
#Sta/Elev= 30
       0 1480.34    19.3 1473.12    43.5 1471.67    57.4 1459.21   147.3 1454.56
   192.2 1435.38   206.1 1422.68   223.7 1422.19   239.3 1427.62   275.6 1424.55
   309.8 1401.14     334 1398.45   368.6 1397.88   403.2 1373.44     413 1369.66
   414.6  1364.2   610.7  1364.2   612.8    1370   624.5 1374.82   686.8 1380.47
   717.9 1387.99   895.5 1404.32   909.5 1406.96   919.8 1414.16   938.5 1414.53
   955.1 1408.86   991.1 1419.93  1015.3 1420.46  1108.7 1435.58  1268.2 1476.02
#Mann= 8 ,-1 , 0
       0    .016       0   275.6     .04       0     334    .016       0
   368.6     .08       0     413    .045       0   612.8     .04       0
   919.8    .016       0   938.5     .05       0
#Block Obstruct= 5 ,-1
   43.17  121.34 1491.77  804.61  856.42 1423.17 1019.34 1051.37 1446.64
 1071.82 1110.22 1456.13 1177.79 1202.06 1480.61
Bank Sta=413,612.8
XS Rating Curve= 0 ,0
Exp/Cntr=0.5,0.3

Type RM Length L Ch R = 1 ,8195    ,81.8,80.5,82.6
BEGIN DESCRIPTION:
Channel burned from survey: 54089GRB022BU
END DESCRIPTION:
XS GIS Cut Line= 4
2008378.59306248236754.2325913912008652.03050771237370.551896811
2008835.76898539237684.7881449762009094.44957039238132.704900056
#Sta/Elev= 30
       0 1491.74    11.6 1492.48    51.1 1481.53   162.4 1463.12   176.7 1457.86
   456.7 1437.94   479.4 1430.09   553.6 1424.53   589.5 1414.96   612.9 1399.14
   636.2 1398.45  644.11  1391.1  699.27 1368.15  782.54 1359.91  876.93 1366.27
 1024.26 1384.14    1064 1385.14  1097.4 1394.11  1142.9 1396.37  1165.6  1409.5
  1180.7 1412.09  1214.8 1412.09  1233.8 1423.19  1255.7 1423.49    1302 1416.07
  1324.7 1404.64  1346.9 1402.83  1380.6 1411.48  1416.6 1433.13  1555.5 1497.45
#Mann= 7 ,-1 , 0
       0     .04       0   612.9    .016       0  644.11     .08       0
  699.27    .045       0  876.93     .04       0  1180.7    .016       0
  1255.7      .1       0
#XS Ineff= 3 ,-1
       0   621.5 1398.71  1098.5    1237 1397.38    1237    1450    1425
Permanent Ineff=
       F       F       F
#Block Obstruct= 6 ,-1
  155.12  207.58 1483.96  261.81  338.19 1472.64  381.49  429.36 1461.13
   469.4  507.62 1453.93  512.41  554.84 1446.83 1080.24 1125.73 1415.46
Bank Sta=699.27,876.93
XS Rating Curve= 0 ,0
Exp/Cntr=0.5,0.3

Type RM Length L Ch R = 3 ,8154    ,,,
BEGIN DESCRIPTION:
County Route 13
Survey ID: GRB020
END DESCRIPTION:
Bridge Culvert--1,0,-1,-1, 0
Deck Dist Width WeirC Skew NumUp NumDn MinLoCord MaxHiCord MaxSubmerge Is_Ogee
37,25,2.6,0, 12, 12, , , 0.98, 0, 0,0,,
  598.97  602.25     645   647.5   647.5     674     860  1072.5  1072.5    1085
    1115    1150
 1399.23 1399.121398.229 1397.381400.0811400.0811400.0811400.081 1397.381397.494
1397.2341397.234
                                1392.7321392.7321392.7321392.732
                
  598.97  602.25     645   647.5   647.5     674     860  1072.5  1072.5    1085
    1115    1150
 1399.23 1399.121398.229 1397.381400.0811400.0811400.0811400.081 1397.381397.494
1397.2341397.234
                                1392.7321392.7321392.7321392.732
                
Pier Skew, UpSta & Num, DnSta & Num=  ,767, 2 ,767, 2 , 0 , 0 , 0 ,,
       5       5
       0    1397
       5       5
       0    1397
Pier Skew, UpSta & Num, DnSta & Num=  ,920, 2 ,920, 2 , 0 , 0 , 0 ,,
       5       5
       0    1397
       5       5
       0    1397
BR Coef=-1 , 1 , 0 ,0.9, 0 ,,,0.8,0,1.2,0,
WSPro=,,,, 1 ,,,, 0 ,,,, 0 ,,,,-1 ,-1 ,-1 , 0 , 0 , 0 , 0 , 0
BR U #Sta/Elev= 30
       0 1491.74    11.6 1492.48    51.1 1481.53   162.4 1463.12   176.7 1457.86
   456.7 1437.94   479.4 1430.09   553.6 1424.53   589.5 1414.96   612.9 1399.14
   636.2 1398.45  644.11  1391.1  699.27 1368.15  782.54 1359.91  876.93 1366.27
 1024.26 1384.14    1064 1385.14  1097.4 1394.11  1142.9 1396.37  1165.6  1409.5
  1180.7 1412.09  1214.8 1412.09  1233.8 1423.19  1255.7 1423.49    1302 1416.07
  1324.7 1404.64  1346.9 1402.83  1380.6 1411.48  1416.6 1433.13  1555.5 1497.45
BR U #Mann= 7
       0     .04   612.9    .016  644.11     .08  699.27     .04  876.93     .04
  1180.7    .016  1255.7      .1
BR D #Sta/Elev= 30
       0 1490.61    87.6 1467.92   174.3 1454.83   238.4 1450.11     256 1445.36
   389.1 1437.45   446.6 1426.43   507.6 1422.84   554.3 1410.74     583 1398.19
   618.5 1398.04     644 1392.94  671.89 1377.25  699.27 1368.15  782.54 1359.91
   895.1 1368.48 1024.26 1384.14  1124.6 1389.43  1162.5 1411.44  1196.6 1412.59
  1226.9 1434.85  1249.6 1437.14  1275.7 1451.02  1309.6 1454.51  1344.3 1450.46
  1367.1 1433.65  1393.8 1419.94  1456.1 1407.92  1488.3 1427.76  1555.5 1459.01
BR D #Mann= 7
       0     .04     583    .016   618.5     .04  699.27     .04   895.1     .08
  1162.5    .016  1196.6      .1
BC Design=,, 0 ,, 0 ,,,,,,
BC Use User HTab Curves=0
BC User HTab FreeFlow(D)= 0