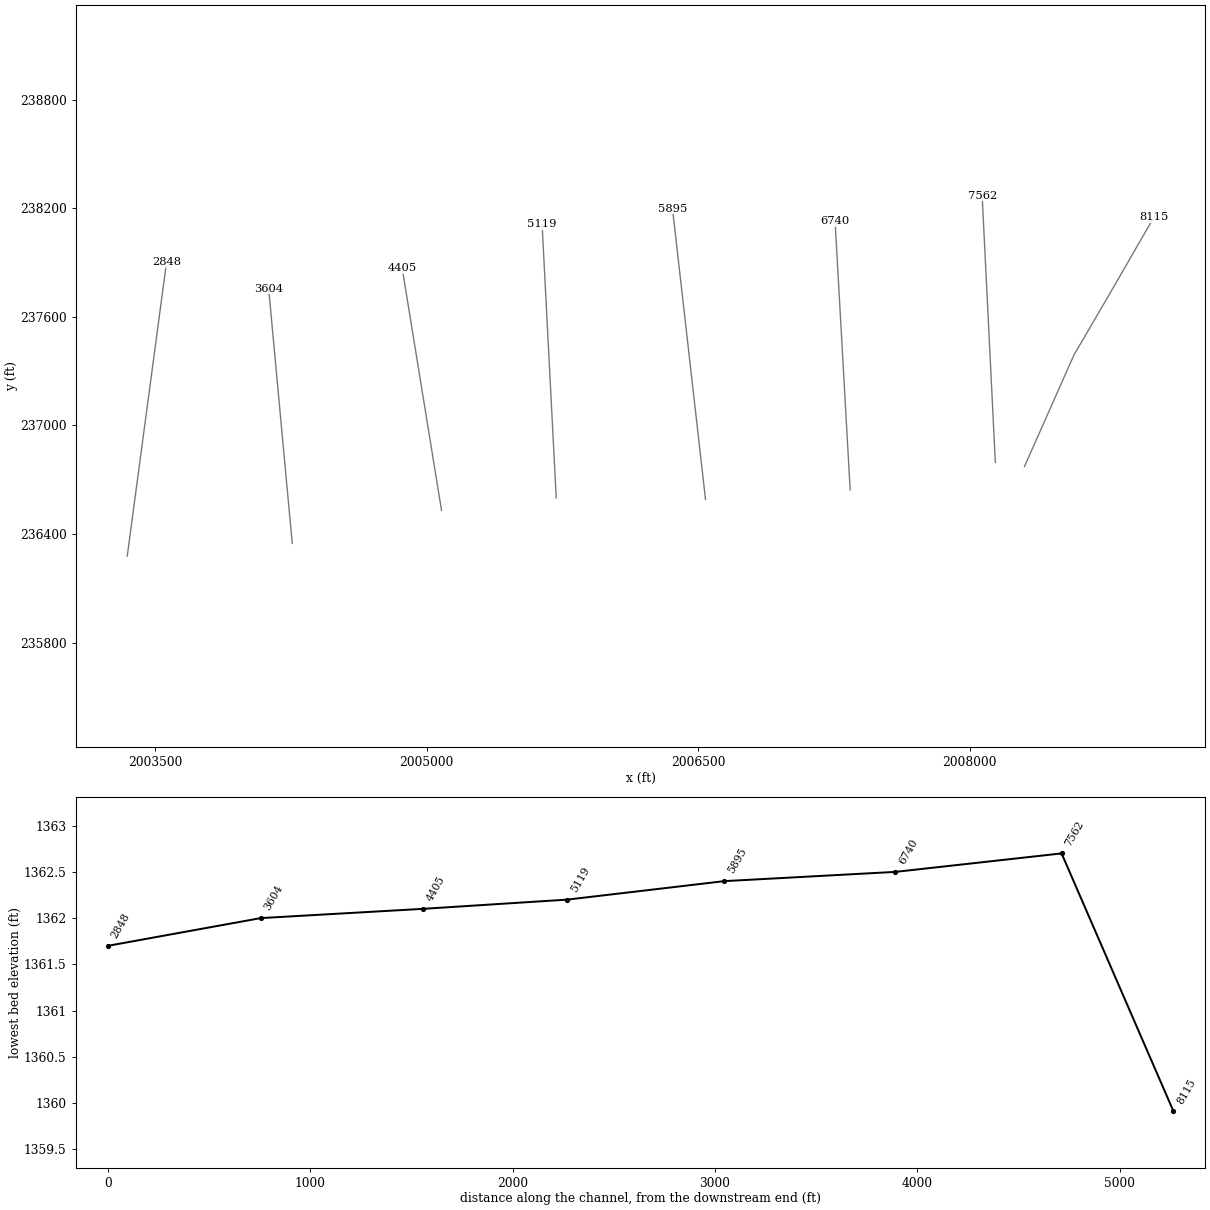
HEC-RAS study GREENBRRV.prj: GREENBRRV

--- GREENBRRV.g01 (geometry) --- (continued)

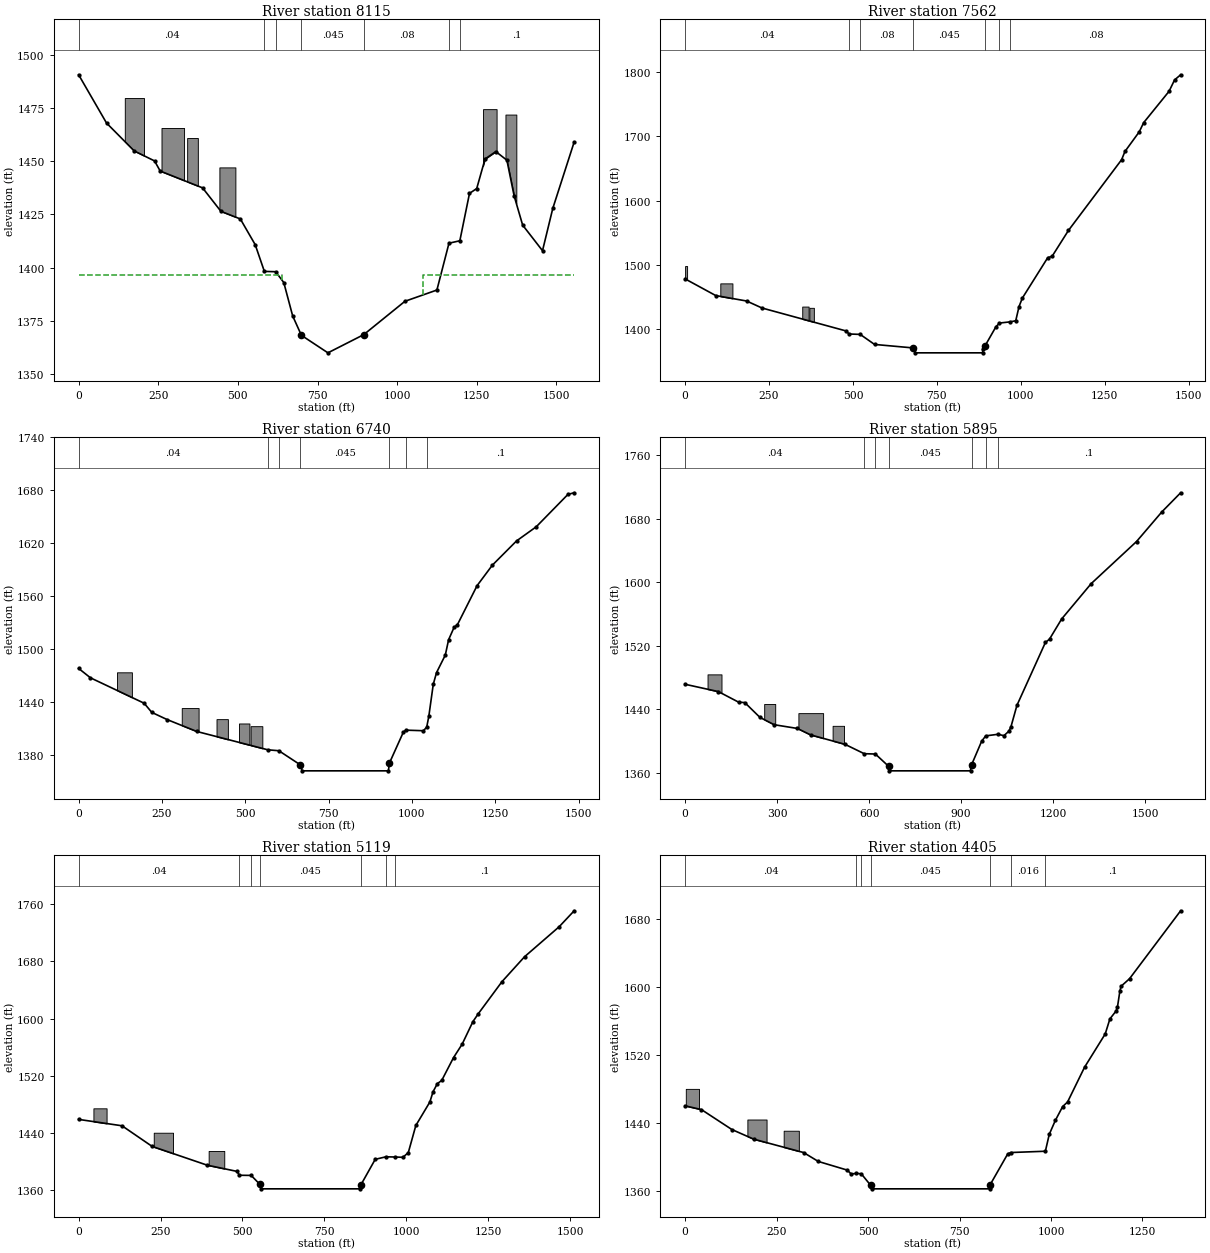
Type RM Length L Ch R = 1 ,8115    ,455,552.9,643.9
BEGIN DESCRIPTION:
Channel burned from survey: 54089GRB022BU
END DESCRIPTION:
XS GIS Cut Line= 4
2008302.20410764236773.3296660632008575.64155288237389.648971483
2008759.38003056237703.8852196482009018.06061555238151.801974729
#Sta/Elev= 30
       0 1490.61    87.6 1467.92   174.3 1454.83   238.4 1450.11     256 1445.36
   389.1 1437.45   446.6 1426.43   507.6 1422.84   554.3 1410.74     583 1398.19
   618.5 1398.04     644 1392.94  671.89 1377.25  699.27 1368.15  782.54 1359.91
   895.1 1368.48 1024.26 1384.14  1124.6 1389.43  1162.5 1411.44  1196.6 1412.59
  1226.9 1434.85  1249.6 1437.14  1275.7 1451.02  1309.6 1454.51  1344.3 1450.46
  1367.1 1433.65  1393.8 1419.94  1456.1 1407.92  1488.3 1427.76  1555.5 1459.01
#Mann= 7 ,-1 , 0
       0     .04       0     583    .016       0   618.5     .04       0
  699.27    .045       0   895.1     .08       0  1162.5    .016       0
  1196.6      .1       0
#XS Ineff= 2 , 0
           637.5  1396.4  1082.5          1396.3
Permanent Ineff=
       F       F
#Block Obstruct= 6 ,-1
  144.89  205.17 1479.67  260.12  330.95  1465.6  340.65  374.19 1460.89
  441.86  492.07 1447.08 1269.44 1311.96 1474.46 1339.82 1373.96 1471.91
Bank Sta=699.27,895.1
XS Rating Curve= 0 ,0
Exp/Cntr=0.5,0.3

Type RM Length L Ch R = 1 ,7562    ,815.2,821.6,819.5
BEGIN DESCRIPTION:
Channel burn based on effective XS I
END DESCRIPTION:
XS GIS Cut Line= 2
2008141.19196247 236795.182968812008068.27544163238269.141306981
#Sta/Elev= 30
       0 1477.93    91.2 1451.97   183.2 1443.46   229.1 1432.55   478.8 1396.89
   488.6 1392.06   521.5 1391.44   564.2 1375.79   679.2 1370.36   682.5 1369.35
   685.7  1362.7   886.1  1362.7   886.2 1368.88   892.5 1372.84   925.5 1403.13
   936.3 1409.11   968.2 1410.98   984.7 1412.69   994.5 1434.82  1004.4 1448.03
  1079.9 1510.91  1093.1  1513.2  1141.7 1553.42    1300 1663.63  1309.9 1676.43
  1352.6 1707.11  1365.7 1721.37  1441.3  1770.2  1457.7 1787.91  1475.8 1795.96
#Mann= 7 ,-1 , 0
       0     .04       0   488.6    .016       0   521.5     .08       0
   679.2    .045       0   892.5     .08       0   936.3    .016       0
   968.2     .08       0
#Block Obstruct= 4 ,-1
       0    5.94 1497.93  104.85  140.93 1470.94  348.85  367.82 1434.81
  370.14  383.48 1432.85
Bank Sta=679.2,892.5
XS Rating Curve= 0 ,0
Exp/Cntr=0.3,0.1

Type RM Length L Ch R = 1 ,6740    ,836,844.9,855
BEGIN DESCRIPTION:
Channel burn based on effective XS H
END DESCRIPTION:
Node Name=B
XS GIS Cut Line= 2
2007339.10859288236644.1412761512007255.77542622238128.516260147
#Sta/Elev= 30
       0 1478.44    35.5 1467.79   196.5 1439.04   219.5 1428.66   265.5 1420.53
   354.2 1407.09   567.8 1386.29   600.7 1385.26   664.9 1369.34     668 1368.76
   669.7  1362.5   929.3  1362.5   932.5 1371.36   974.4 1406.45   982.2 1408.55
  1034.4 1407.91  1044.3 1411.96  1050.7 1424.47    1064 1460.54  1073.9 1473.81
  1100.1 1493.56    1110 1510.97  1126.4 1524.88  1136.3 1527.83  1195.4 1572.12
  1241.4 1595.38  1313.7 1622.72  1372.9 1638.76  1468.2 1675.49  1486.7 1677.25
#Mann= 7 ,-1 , 0
       0     .04       0   567.8    .016       0   600.7     .08       0
   664.9    .045       0   932.5     .08       0   982.2    .016       0
  1044.3      .1       0
#Block Obstruct= 5 ,-1
  115.03  159.83 1474.02  309.37  359.96 1433.56  413.68  447.76 1421.03
  481.05  512.35 1416.11  515.88  551.15 1413.06
Bank Sta=664.9,932.5
XS Rating Curve= 0 ,0
Exp/Cntr=0.3,0.1

Type RM Length L Ch R = 1 ,5895    ,787.1,776.3,764.9
BEGIN DESCRIPTION:
Channel burn based on effective XS G
END DESCRIPTION:
XS GIS Cut Line= 2
2006540.06360306236591.1899384712006357.77197289238197.092894644
#Sta/Elev= 30
       0 1471.49   108.7 1462.24   174.8 1448.88   194.6 1448.46   244.1 1429.75
   290.4 1420.53   366.3 1415.81   409.2 1407.72   521.5 1395.82   584.2    1384
   620.6 1383.59   663.5 1368.23   665.1  1362.4   930.9  1362.4     932 1368.53
   934.2 1369.88   967.2 1399.72   980.5 1406.47  1020.1 1408.44  1039.9 1406.76
  1056.3 1412.44    1063 1418.21  1082.3 1444.95  1175.1 1524.14  1188.5 1528.36
  1228.1 1553.77  1324.4  1598.3  1472.4  1651.4    1555 1688.76  1616.2 1712.81
#Mann= 7 ,-1 , 0
       0     .04       0   584.2    .016       0   620.6     .08       0
   663.5    .045       0   934.2     .08       0   980.5    .016       0
  1020.1      .1       0
#Block Obstruct= 4 ,-1
   73.19  118.71 1483.97  257.97  293.92 1446.67  369.53  450.12 1435.12
  481.12  518.36 1419.12
Bank Sta=663.5,934.2
XS Rating Curve= 0 ,0
Exp/Cntr=0.3,0.1

Type RM Length L Ch R = 1 ,5119    ,692.7,714.5,733.4
BEGIN DESCRIPTION:
Channel burn based on effective XS F
END DESCRIPTION:
XS GIS Cut Line= 2
 2005715.4107248236599.8703673032005637.28588106238110.287293971
#Sta/Elev= 30
       0 1459.14   132.4 1450.23   224.3 1421.45   391.9  1395.3   483.9  1386.5
   490.4 1381.16   526.6 1380.94   552.9 1368.57   556.2  1362.2   858.4  1362.2
   859.9 1367.47   861.7 1367.94   905.2  1403.4     938 1406.93   966.8 1406.62
   989.8 1406.22  1006.2 1412.86  1029.2 1450.68  1071.9 1483.37  1081.8 1497.85
  1094.9 1509.12  1108.1 1513.48  1144.2 1545.41  1170.5 1564.16  1203.3 1595.59
  1219.8 1606.69    1292  1651.4    1361 1686.24  1466.5 1728.07  1512.4 1750.39
#Mann= 7 ,-1 , 0
       0     .04       0   490.4    .016       0   526.6     .08       0
   552.9    .045       0   861.7     .08       0     938    .016       0
   966.8      .1       0
#Block Obstruct= 3 ,-1
   45.14    85.3 1474.61  229.27  288.13 1440.54  396.84  444.47 1415.09
Bank Sta=552.9,861.7
XS Rating Curve= 0 ,0
Exp/Cntr=0.3,0.1

Type RM Length L Ch R = 1 ,4405    ,814,800.7,784.3
BEGIN DESCRIPTION:
Channel burn based on effective XS E
END DESCRIPTION:
XS GIS Cut Line= 2
2005081.73023364 236530.425952392004864.71623197237867.231677726
#Sta/Elev= 30
       0 1459.92    44.7 1455.45   127.8 1431.99   187.6 1420.62     324 1404.84
     364 1394.38   443.6 1384.11   453.6  1379.6   466.8 1380.22   481.3 1379.93
   506.7 1366.49   510.1  1362.1   832.5  1362.1     833 1366.41   881.6 1403.15
   890.2 1404.88   984.6  1406.4   995.3 1426.38  1011.9 1442.74  1031.9 1459.07
  1045.2 1464.36  1091.7 1505.38  1148.2 1544.61    1161 1562.37  1178.1 1571.76
  1181.5 1575.93  1188.1 1594.71  1191.4 1600.71  1214.7 1609.69  1354.3  1689.7
#Mann= 7 ,-1 , 0
       0     .04       0   466.8    .016       0   481.3     .08       0
   506.7    .045       0     833     .08       0   890.2    .016       0
   984.6      .1       0
#Block Obstruct= 3 ,-1
    1.92   37.95 1479.87  170.23  222.66 1443.79  269.41  310.84 1430.57
Bank Sta=506.7,833
XS Rating Curve= 0 ,0
Exp/Cntr=0.3,0.1

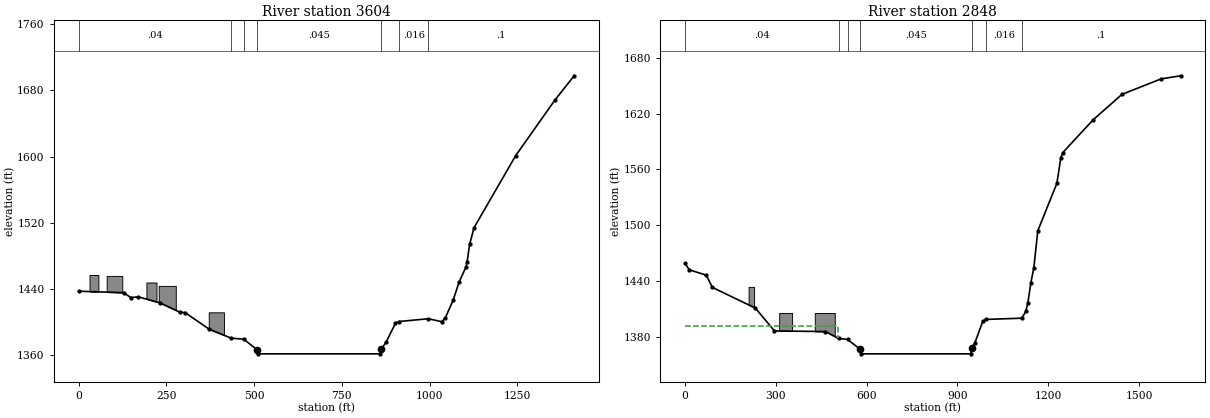
Type RM Length L Ch R = 1 ,3604    ,803,755.5,707.1
BEGIN DESCRIPTION:
Channel burn based on effective XS D
END DESCRIPTION:
Node Name=A
XS GIS Cut Line= 2
2004257.07735538236348.1343222262004126.86928247237754.384462476
#Sta/Elev= 30
       0 1437.56   128.6 1435.84   148.3 1429.95   170.4 1430.71   231.2 1423.65
     290 1411.97   303.2 1411.84   372.4 1391.66     435 1380.91   470.3 1379.73
   508.2 1367.07   510.2 1366.17   511.2    1362     860    1362   862.5 1367.44
   876.5 1376.35   902.9 1398.84   913.3 1401.01   996.8 1404.36  1034.7  1400.8
  1044.5 1404.82  1067.6 1427.03  1084.1 1448.42  1103.8 1466.61  1107.1 1472.79
  1114.3 1494.03  1126.9 1514.21  1245.5 1601.12  1357.5 1668.28  1412.3 1697.53
#Mann= 7 ,-1 , 0
       0     .04       0     435    .016       0   470.3     .08       0
   508.2    .045       0   862.5     .08       0   913.3    .016       0
   996.8      .1       0
#Block Obstruct= 5 ,-1
   31.04   56.26  1457.1   79.91  124.42 1456.04  193.21  221.87 1448.09
  228.21  276.88 1443.98  370.83  414.15  1412.1
Bank Sta=508.2,862.5
XS Rating Curve= 0 ,0
Exp/Cntr=0.3,0.1

Type RM Length L Ch R = 1 ,2848    ,943.8,854.2,765.5
BEGIN DESCRIPTION:
Channel burn based on effective XS C
END DESCRIPTION:
XS GIS Cut Line= 2
2003345.61920455236278.6899073122003562.63287814237901.953721151
#Sta/Elev= 30
       0 1458.99    13.9 1452.09    70.1 1446.31      90 1433.18   232.3 1410.91
   295.2 1386.36     464 1385.66     507 1378.21   536.8 1377.22   576.6 1367.09
   576.6 1367.05   582.5  1361.7     944  1361.7   947.4 1368.41   957.2 1373.07
   983.7 1396.62   993.6 1398.71  1112.8 1400.05    1126  1407.4  1132.6 1416.16
  1142.6 1437.91  1152.5 1454.26  1165.7 1494.15  1228.6 1545.01  1241.9 1572.87
  1248.5 1578.28  1347.8 1613.23  1443.8 1640.81  1572.9 1657.45  1637.7 1660.81
#Mann= 7 ,-1 , 0
       0     .04       0     507    .016       0   536.8     .08       0
   576.6    .045       0   947.4     .08       0   993.6    .016       0
  1112.8      .1       0
#XS Ineff= 2 , 0
          504.38 1391.36
Permanent Ineff=
       F       F
#Block Obstruct= 3 ,-1
  209.85  228.05 1433.76  310.89  353.64 1405.71  428.54  494.69 1405.65
Bank Sta=576.6,947.4
XS Rating Curve= 0 ,0
Exp/Cntr=0.3,0.1