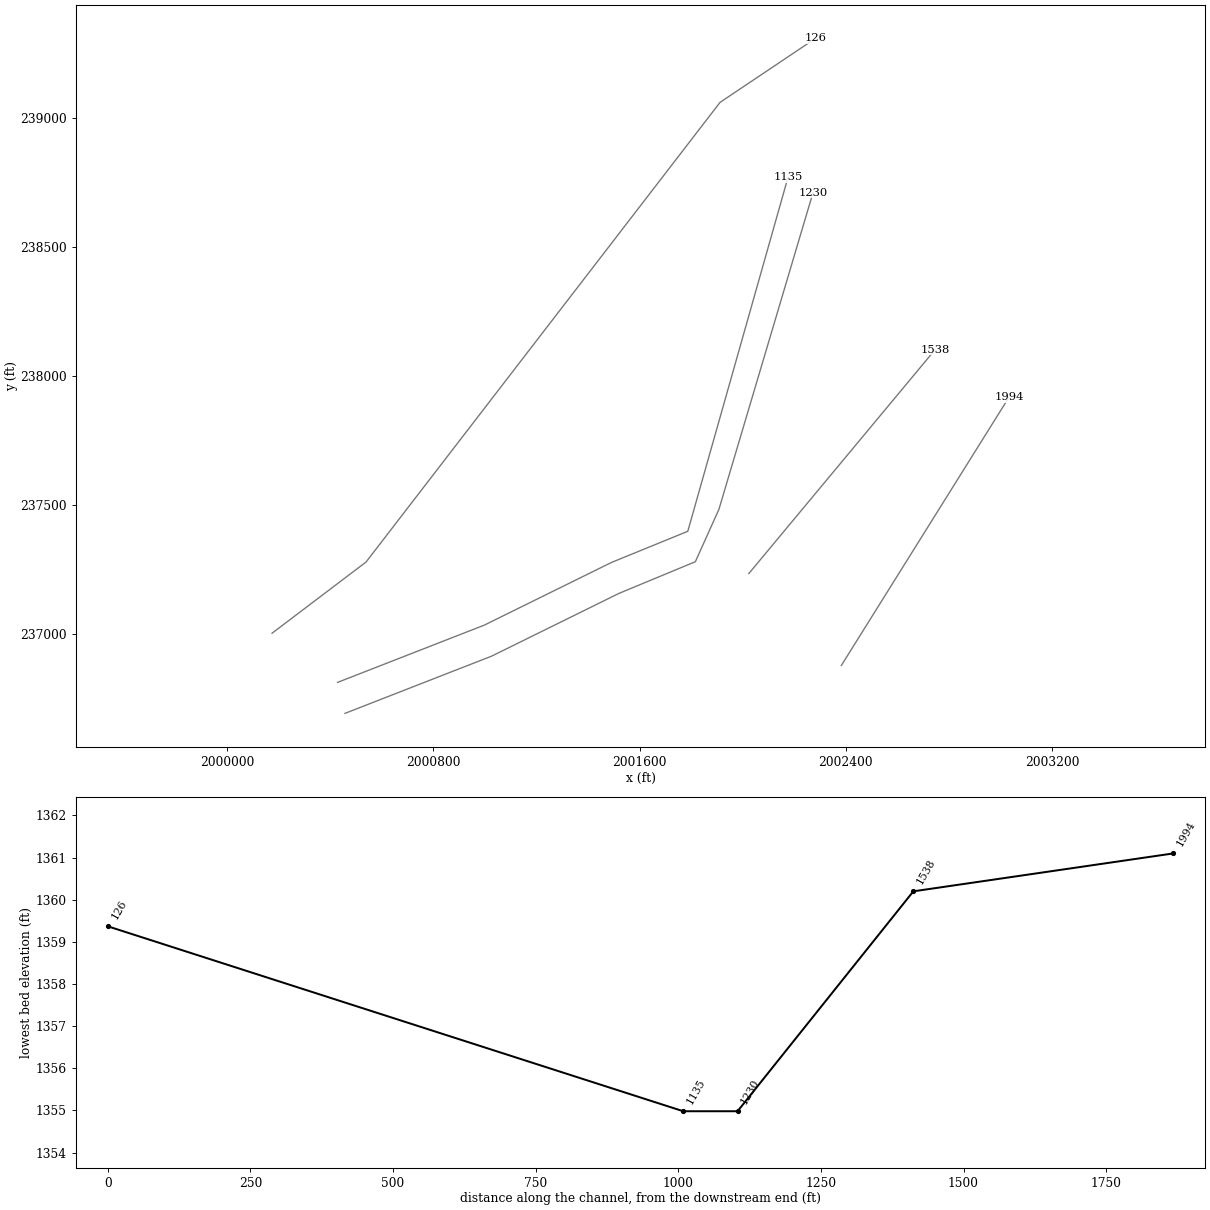
HEC-RAS study GREENBRRV.prj: GREENBRRV

--- GREENBRRV.g01 (geometry) --- (continued)

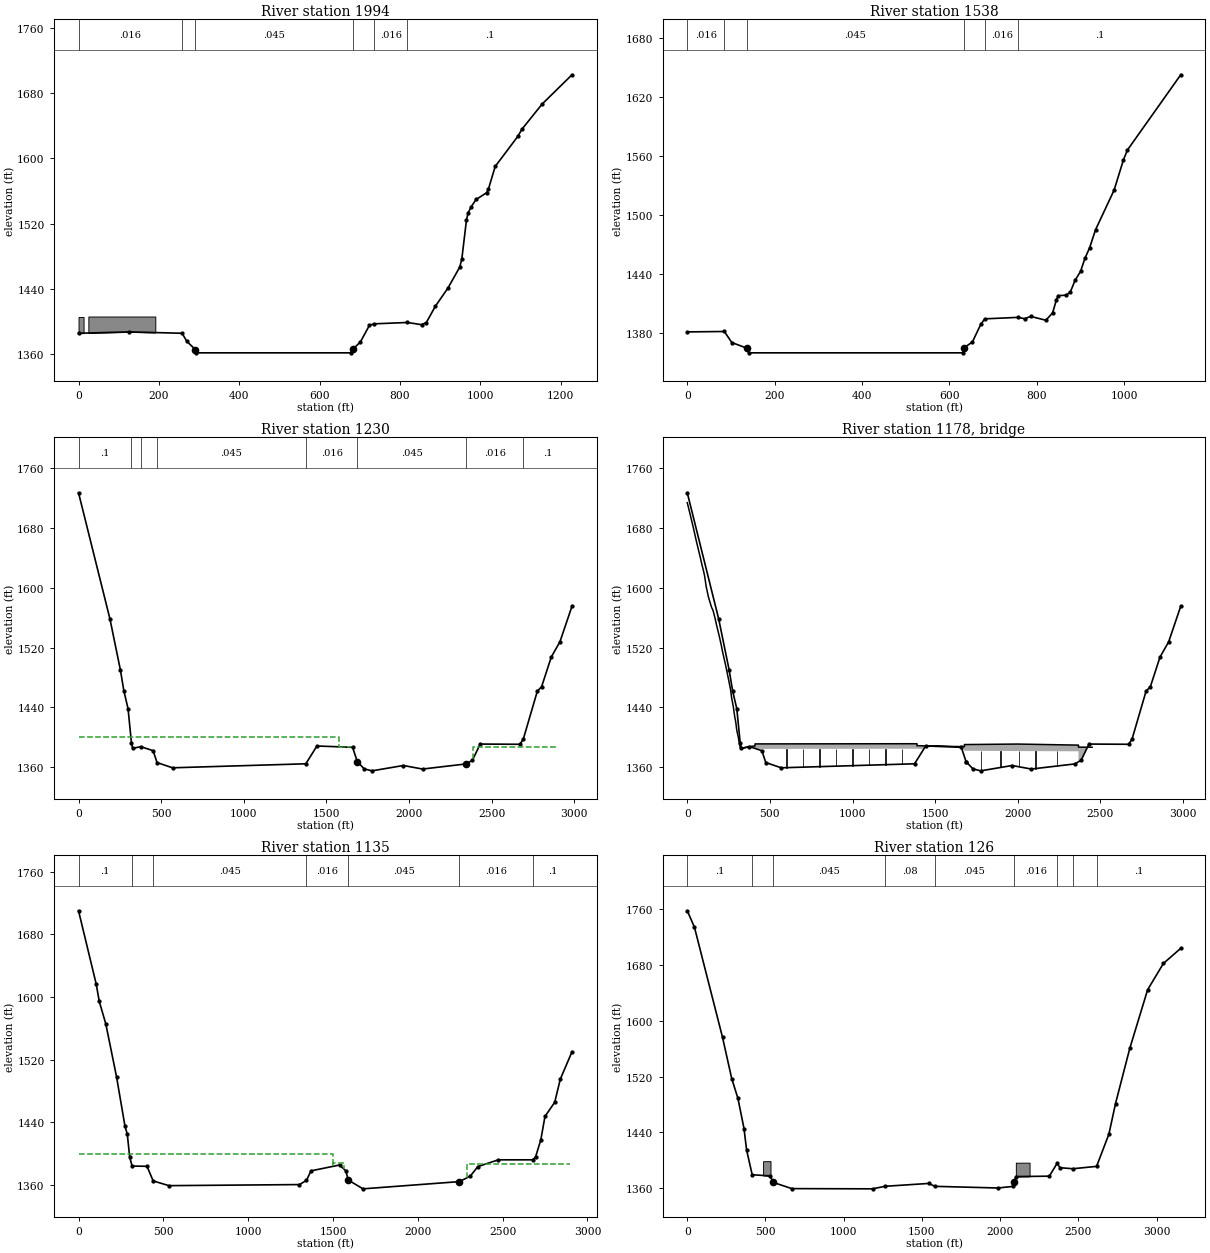
Type RM Length L Ch R = 1 ,1994    ,480.5,455.9,410.3
BEGIN DESCRIPTION:
Channel burn based on effective XS B
END DESCRIPTION:
XS GIS Cut Line= 2
2002382.07749647236877.6483550672003033.11917339237919.314906895
#Sta/Elev= 30
       0 1385.16   126.2 1386.84   257.8 1385.16   269.4 1375.35     291 1364.99
   292.6  1361.1   679.5  1361.1     681 1365.03   682.4 1365.42   701.5 1374.34
   724.3 1395.08   736.7 1396.76   818.8 1398.43   853.8 1395.72   865.8 1398.35
   888.4 1418.51   919.3 1440.51   949.1 1466.63   954.2 1476.75   965.7 1524.39
   969.6 1532.88   977.4 1540.61   989.6 1549.58  1016.1 1557.97  1020.5 1562.64
  1037.2 1590.19  1093.4 1627.07  1103.8 1635.99  1153.8 1666.77  1228.4 1702.88
#Mann= 6 ,-1 , 0
       0    .016       0   257.8     .08       0     291    .045       0
   682.4     .08       0   736.7    .016       0   818.8      .1       0
#Block Obstruct= 2 ,-1
       0   12.55 1405.21   24.48  191.16 1405.76
Bank Sta=291,682.4
XS Rating Curve= 0 ,0
Exp/Cntr=0.3,0.1

Type RM Length L Ch R = 1 ,1538    ,242,308.1,506.5
BEGIN DESCRIPTION:
Channel burn based on effective XS A
END DESCRIPTION:
XS GIS Cut Line= 2
2002023.28129806237234.4189669792002745.50327881238102.474645555
#Sta/Elev= 30
       0 1381.44    84.8 1381.85   101.9 1370.66   135.7 1365.04     138 1364.87
   140.3  1360.2   631.1  1360.2   631.9 1364.87   634.2 1365.56   652.5 1371.28
   671.5 1388.99   680.8 1394.68   757.7 1396.19     772 1394.77   785.7 1397.17
   820.6 1393.27     836 1400.77   844.5 1413.72   848.8 1418.22   867.2 1418.68
   876.8 1422.15   887.2 1433.58     900 1442.84   909.8 1455.91   920.8 1466.88
   934.2 1485.03   976.7 1525.25   998.2 1556.13  1007.3 1565.98  1129.2 1642.25
#Mann= 6 ,-1 , 0
       0    .016       0    84.8     .08       0   135.7    .045       0
   634.2     .08       0   680.8    .016       0   757.7      .1       0
#Block Obstruct= 2 , 0
           28.31 1401.44
Bank Sta=135.7,634.2
XS Rating Curve= 0 ,0
Exp/Cntr=0.5,0.3

Type RM Length L Ch R = 1 ,1230    ,88.4,95.2,119.1
BEGIN DESCRIPTION:
Channel burned from survey: 54089GRB012BU and 54089NER032BU
END DESCRIPTION:
XS GIS Cut Line= 6
     2000456.528      236692.014     2001025.972      236914.236
     2001519.028      237157.2912001815.99141989237280.448637639
2001907.37664112237483.8544526352002272.01345072238711.176973885
#Sta/Elev= 30
       0 1727.05   189.9  1558.4   253.6 1489.64   274.4 1461.89   299.7 1438.07
   320.2 1392.56   327.2    1385   376.5 1387.38  451.37 1381.95  474.93 1366.08
  568.59 1359.05 1375.18 1364.41 1442.61 1388.23  1658.2 1386.46  1686.9 1367.24
  1686.9 1367.22 1728.83 1357.55 1775.78 1354.98 1965.64 1362.12 2081.53 1357.38
 2343.93  1364.2 2382.91    1369  2430.5 1390.81    2670 1390.51  2690.6 1397.02
  2776.2 1461.72  2801.8 1467.46  2860.2 1507.13  2912.8  1527.7  2985.8 1575.29
#Mann= 8 ,-1 , 0
       0      .1       0   320.2    .016       0   376.5     .04       0
  474.93    .045       0 1375.18    .016       0  1686.9    .045       0
 2343.93    .016       0  2690.6      .1       0
#XS Ineff= 3 ,-1
       0    1575    1400    1575    1651 1387.46    2388    2900 1386.64
Permanent Ineff=
       F       F       F
Bank Sta=1686.9,2343.93
XS Rating Curve= 0 ,0
Exp/Cntr(USF)=0,0
Exp/Cntr=0.5,0.3

Type RM Length L Ch R = 3 ,1178    ,,,
BEGIN DESCRIPTION:
Veterans Memorial Bridge
Bridge Survey Information: 54089NER030/ NER032BU for New River portion and 54089GRB010 for Greenbrier River portion
Included railing height of 2.70ft.  54089GRB010 survey report doesn't include a railing height but survey images show a railing. Assumed railing height to be consistent with the railing height from New River
END DESCRIPTION:
Bridge Culvert--1,0,-1,-1, 0
Deck Dist Width WeirC Skew NumUp NumDn MinLoCord MaxHiCord MaxSubmerge Is_Ogee
21,40,2.6,0, 170, 168, , , 0.98, 0, 0,0,,
       0   3.272   6.543   9.815  13.087  16.359   19.63  22.902  26.174  29.446
  32.717  35.989  39.261  42.533  45.804  49.076  52.348  55.619  58.891  62.163
  65.435  68.706  71.978   75.25  78.522  81.793  85.065  88.337  91.609   94.88
  98.152 101.424 104.696 107.967 111.239 114.511 117.783 121.054 124.326 127.598
 130.869 134.141 137.413 140.685 143.956 147.228   150.5 153.772 157.043 160.315
 163.587 166.859  170.13 173.402 176.674 179.945 183.217 186.489 189.761 193.032
 196.304 199.576 202.848 206.119 209.391 212.663 215.935 219.206 222.478  225.75
 229.021 232.293 235.565 238.837 242.108  245.38 248.652 251.924 255.195 258.467
 261.739 265.011 268.282 271.554 274.826 278.098 281.369 284.641 287.913 291.184
 294.456 297.728     301 304.271 307.543 310.815 314.087 317.358  320.63 323.902
 327.174 330.445 333.717 336.989  340.26 343.532 346.804 350.076 353.347 356.619
 359.891 363.163 366.434 369.706 372.978  376.25 379.521 382.793 386.065 389.337
 392.608  395.88 399.152 402.423 405.695 408.967     410     410    1390    1390
1413.294 1416.571419.8471423.1231426.3991429.6751432.9511436.2281439.504 1442.78
1446.0561449.3331452.6091455.8851459.1611462.4371465.714 1468.991472.2661475.542
1478.8181482.0951485.3711488.6471491.923  1495.21498.4761501.7521505.0281508.304
1511.5811514.8571518.133    1615    1677    1677    2000    2367    2367    2450
1713.8041711.0261707.9781704.8341701.9161699.0141696.0891693.1191690.1741687.169
1684.0421681.0261677.7491674.0991670.8271668.1151665.1971661.7571658.8081656.028
1653.3221650.3761647.2161644.1221640.779 1637.461634.1791631.1711628.4181625.597
1622.6121619.5271615.9991611.024 1606.591601.5851598.0951594.6191591.0241587.987
1585.6571583.6371581.1241578.2741575.8121573.6681572.2671570.7241568.7161565.958
1563.236 1560.37 1557.011553.5621550.5761547.6691544.5681541.661 1538.841535.695
1532.4671529.3931526.459  1522.71518.8281515.2021512.1161509.0351505.7391502.451
1499.2381495.9581492.6011488.7751485.472 1481.721478.2811474.867 1471.271467.733
1464.0161458.5931452.9161449.1391445.7031441.4541436.2791430.4921426.278 1423.09
1418.3971412.2741407.6461404.7151401.5141397.1621392.5451388.9021386.4061385.065
1384.7761384.8531385.0741385.2971385.5031385.6751385.869 1386.081386.2941386.504
1386.6741386.7921386.972 1387.171387.2931387.3871387.5311387.6331387.7061387.765
1387.8581387.9421388.0311388.1011388.1911388.324 1388.33 1391.03 1391.27 1388.64
 1388.641388.6111388.5431388.4551388.3761388.2631388.2671388.2581388.2381388.252
 1388.271388.2671388.2681388.2751388.2811388.3181388.3411388.3641388.3891388.416
1388.4261388.437 1388.461388.493  1388.51388.4931388.4791388.4871388.4951388.509
1388.5251388.5021388.4751387.532 1387.46 1390.161390.822  1389.4  1386.71386.603
                                                                                
                                                                                
                                                                                
                                                                                
                                                                                
                                                                                
                                                                                
                                                                                
                                                                                
                                                                                
                                                                                
                                                                                
                                                         1384.33 1384.57
                                                                                
                                                                                
                                                                                
                                         1381.86 1381.45  1381.1
       0   3.272   6.543   9.815  13.087  16.359   19.63  22.902  26.174  29.446
  32.717  35.989  39.261  42.533  45.804  49.076  52.348  55.619  58.891  62.163
  65.435  68.706  71.978   75.25  78.522  81.793  85.065  88.337  91.609   94.88
  98.152 101.424 104.696 107.967 111.239 114.511 117.783 121.054 124.326 127.598
 130.869 134.141 137.413 140.685 143.956 147.228   150.5 153.772 157.043 160.315
 163.587 166.859  170.13 173.402 176.674 179.945 183.217 186.489 189.761 193.032
 196.304 199.576 202.848 206.119 209.391 212.663 215.935 219.206 222.478  225.75
 229.021 232.293 235.565 238.837 242.108  245.38 248.652 251.924 255.195 258.467
 261.739 265.011 268.282 271.554 274.826 278.098 281.369 284.641 287.913 291.184
 294.456 297.728     301 304.271 307.543 310.815 314.087 317.358  320.63 323.902
 327.174 330.445 333.717 336.989  340.26 343.532 346.804 350.076 353.347 356.619
 359.891 363.163 366.434 369.706 372.978  376.25 379.521 382.793 386.065 389.337
 392.608  395.88 399.152 402.423 405.695 408.967     410     410    1390    1390
1413.294 1416.571419.8471423.1231426.3991429.6751432.9511436.2281439.504 1442.78
1446.0561449.3331452.6091455.8851459.1611462.4371465.714 1468.991472.2661475.542
1478.8181482.0951485.3711488.6471491.923  1495.21498.4761501.7521505.0281508.304
1511.5811514.8571518.133    1577    1577    2267    2267    2450
1713.8041711.0261707.9781704.8341701.9161699.0141696.0891693.1191690.1741687.169
1684.0421681.0261677.7491674.0991670.8271668.1151665.1971661.7571658.8081656.028
1653.3221650.3761647.2161644.1221640.779 1637.461634.1791631.1711628.4181625.597
1622.6121619.5271615.9991611.024 1606.591601.5851598.0951594.6191591.0241587.987
1585.6571583.6371581.1241578.2741575.8121573.6681572.2671570.7241568.7161565.958
1563.236 1560.37 1557.011553.5621550.5761547.6691544.5681541.661 1538.841535.695
1532.4671529.3931526.459  1522.71518.8281515.2021512.1161509.0351505.7391502.451
1499.2381495.9581492.6011488.7751485.472 1481.721478.2811474.867 1471.271467.733
1464.0161458.5931452.9161449.1391445.7031441.4541436.2791430.4921426.278 1423.09
1418.3971412.2741407.6461404.7151401.5141397.1621392.5451388.9021386.4061385.065
1384.7761384.8531385.0741385.2971385.5031385.6751385.869 1386.081386.2941386.504
1386.6741386.7921386.972 1387.171387.2931387.3871387.5311387.6331387.7061387.765
1387.8581387.9421388.0311388.1011388.1911388.324 1388.33 1391.03 1391.27 1388.64
 1388.641388.6111388.5431388.4551388.3761388.2631388.2671388.2581388.2381388.252
 1388.271388.2671388.2681388.2751388.2811388.3181388.3411388.3641388.3891388.416
1388.4261388.437 1388.461388.493  1388.51388.4931388.4791388.4871388.4951388.509
1388.5251388.5021388.475 1388.36 1391.06 1389.67 1386.971386.603
                                                                                
                                                                                
                                                                                
                                                                                
                                                                                
                                                                                
                                                                                
                                                                                
                                                                                
                                                                                
                                                                                
                                                                                
                                                         1384.57 1384.57
                                                                                
                                                                                
                                                                                
                                 1382.76 1381.37
Pier Skew, UpSta & Num, DnSta & Num=  ,600, 2 ,600, 2 , 0 , 0 , 0 ,,
       4       4
       0    1390
       4       4
       0    1390
Pier Skew, UpSta & Num, DnSta & Num=  ,700, 2 ,700, 2 , 0 , 0 , 0 ,,
       4       4
       0    1390
       4       4
       0    1390
Pier Skew, UpSta & Num, DnSta & Num=  ,800, 2 ,800, 2 , 0 , 0 , 0 ,,
       4       4
       0    1390
       4       4
       0    1390
Pier Skew, UpSta & Num, DnSta & Num=  ,900, 2 ,900, 2 , 0 , 0 , 0 ,,
       4       4
       0    1390
       4       4
       0    1390
Pier Skew, UpSta & Num, DnSta & Num=  ,1000, 2 ,1000, 2 , 0 , 0 , 0 ,,
       4       4
       0    1390
       4       4
       0    1390
Pier Skew, UpSta & Num, DnSta & Num=  ,1100, 2 ,1100, 2 , 0 , 0 , 0 ,,
       4       4
       0    1390
       4       4
       0    1390
Pier Skew, UpSta & Num, DnSta & Num=  ,1200, 2 ,1200, 2 , 0 , 0 , 0 ,,
       4       4
       0    1390
       4       4
       0    1390
Pier Skew, UpSta & Num, DnSta & Num=  ,1300, 2 ,1300, 2 , 0 , 0 , 0 ,,
       4       4
       0    1390
       4       4
       0    1390
Pier Skew, UpSta & Num, DnSta & Num=  ,1777, 2 ,1677, 2 , 0 , 0 , 0 ,,
       4       4
       0    1385
       4       4
       0    1385
Pier Skew, UpSta & Num, DnSta & Num=  ,1897, 2 ,1797, 2 , 0 , 0 , 0 ,,
       4       4
       0    1385
       4       4
       0    1385
Pier Skew, UpSta & Num, DnSta & Num=  ,2007, 2 ,1907, 2 , 0 , 0 , 0 ,,
       4       4
       0    1385
       4       4
       0    1385
Pier Skew, UpSta & Num, DnSta & Num=  ,2107, 2 ,2007, 2 , 0 , 0 , 0 ,,
       4       4
       0    1385
       4       4
       0    1385
Pier Skew, UpSta & Num, DnSta & Num=  ,2237, 2 ,2137, 2 , 0 , 0 , 0 ,,
       4       4
       0    1385
       4       4
       0    1385
BR Coef=-1 , 1 , 0 ,0.9, 0 ,,,0.8,0,1.33,0,
WSPro=,,,, 1 ,,,, 0 ,,,, 0 ,,,,-1 ,-1 ,-1 , 0 , 0 , 0 , 0 , 0
BR U #Sta/Elev= 30
       0 1727.05   189.9  1558.4   253.6 1489.64   274.4 1461.89   299.7 1438.07
   320.2 1392.56   327.2    1385   376.5 1387.38  451.37 1381.95  474.93 1366.08
  568.59 1359.05 1375.18 1364.41 1442.61 1388.23  1658.2 1386.46  1686.9 1367.24
  1686.9 1367.22 1728.83 1357.55 1775.78 1354.98 1965.64 1362.12 2081.53 1357.38
 2343.93  1364.2 2382.91    1369  2430.5 1390.81    2670 1390.51  2690.6 1397.02
  2776.2 1461.72  2801.8 1467.46  2860.2 1507.13  2912.8  1527.7  2985.8 1575.29
BR U #Mann= 8
       0      .1   320.2    .016   376.5     .04  474.93     .04 1375.18    .016
  1686.9     .04 2343.93    .016  2690.6      .1
BR D #Sta/Elev= 30
       0 1709.99   104.4 1616.24     122  1594.5   160.8 1565.54   224.1 1497.99
   273.5 1435.34   287.5 1424.71   301.6 1395.53   315.7 1384.08   403.8 1383.74
  439.74 1365.14  532.59 1359.05 1302.26 1360.42 1343.66 1365.78 1370.27 1377.94
  1538.5 1385.41    1576 1377.95  1589.6 1366.27 1676.78 1354.98 2244.93  1364.2
  2309.1 1371.19  2354.3 1383.43  2474.8 1392.03  2677.3 1392.02  2693.8  1395.5
  2725.1 1417.55  2749.6 1447.44  2806.9 1465.44  2839.9 1494.98  2908.9 1530.02
BR D #Mann= 7
       0      .1   315.7    .016  439.74     .04 1343.66    .016  1589.6     .04
 2244.93    .016  2677.3      .1
BC Design=,, 0 ,, 0 ,,,,,,
BC Use User HTab Curves=0
BC User HTab FreeFlow(D)= 0

Type RM Length L Ch R = 1 ,1135    ,1268.7,1008.7,612.5
BEGIN DESCRIPTION:
Channel burned from survey: 54089GRB012BU and 54089NER032BU
END DESCRIPTION:
XS GIS Cut Line= 5
     2000427.882      236812.239     2000997.326      237034.462
     2001490.382      237277.5172001786.51231627237398.365052129
2002175.56551238 238772.44476664
#Sta/Elev= 30
       0 1709.99   104.4 1616.24     122  1594.5   160.8 1565.54   224.1 1497.99
   273.5 1435.34   287.5 1424.71   301.6 1395.53   315.7 1384.08   403.8 1383.74
  439.74 1365.14  532.59 1359.05 1302.26 1360.42 1343.66 1365.78 1370.27 1377.94
  1538.5 1385.41    1576 1377.95  1589.6 1366.27 1676.78 1354.98 2244.93  1364.2
  2309.1 1371.19  2354.3 1383.43  2474.8 1392.03  2677.3 1392.02  2693.8  1395.5
  2725.1 1417.55  2749.6 1447.44  2806.9 1465.44  2839.9 1494.98  2908.9 1530.02
#Mann= 7 ,-1 , 0
       0      .1       0   315.7    .016       0  439.74    .045       0
 1343.66    .016       0  1589.6    .045       0 2244.93    .016       0
  2677.3      .1       0
#XS Ineff= 3 ,-1
       0    1500    1400    1500    1566 1388.36    2287    2900 1386.97
Permanent Ineff=
       F       F       F
Bank Sta=1589.6,2244.93
XS Rating Curve= 0 ,0
Exp/Cntr(USF)=0,0
Exp/Cntr=0.5,0.3

Type RM Length L Ch R = 1 ,126     ,,,
BEGIN DESCRIPTION:
Channel burned determined by PMR XS 18893.7
END DESCRIPTION:
XS GIS Cut Line= 4
     2000173.793      237003.034     2000538.415       237279.23
     2001911.616      239062.341     2002282.242      239310.789
#Sta/Elev= 30
       0 1756.98    45.7  1733.6   225.4 1575.94   284.2 1516.97   323.5 1489.03
   362.7 1445.56     379 1415.18     415 1379.53   529.6 1377.87   549.3 1368.58
   668.1  1359.7  1184.4 1359.37  1264.5 1363.01  1543.4 1367.09  1582.7 1362.94
  1985.4 1360.59  2081.4 1362.84 2089.05 1368.62  2101.1  1376.9  2314.3 1377.49
  2363.5 1395.67  2383.2 1389.55  2465.2 1388.13  2616.2 1391.49  2694.9 1437.54
  2737.3 1481.31  2828.5 1560.28  2942.5 1644.04  3043.5  1681.7  3154.2  1703.3
#Mann= 9 ,-1 , 0
       0      .1       0     415    .016       0   549.3    .045       0
  1264.5     .08       0  1582.7    .045       0 2089.05    .016       0
  2363.5     .04       0  2465.2    .016       0  2616.2      .1       0
#Block Obstruct= 2 ,-1
   484.5  532.04 1398.92 2100.12 2187.91  1396.8
Bank Sta=549.3,2089.05
XS Rating Curve= 0 ,0
Exp/Cntr(USF)=0,0
Exp/Cntr=0.3,0.1
LCMann Table=0

Chan Stop Cuts=-1
Use User Specified Reach Order=0
Composite Channel Slope=5